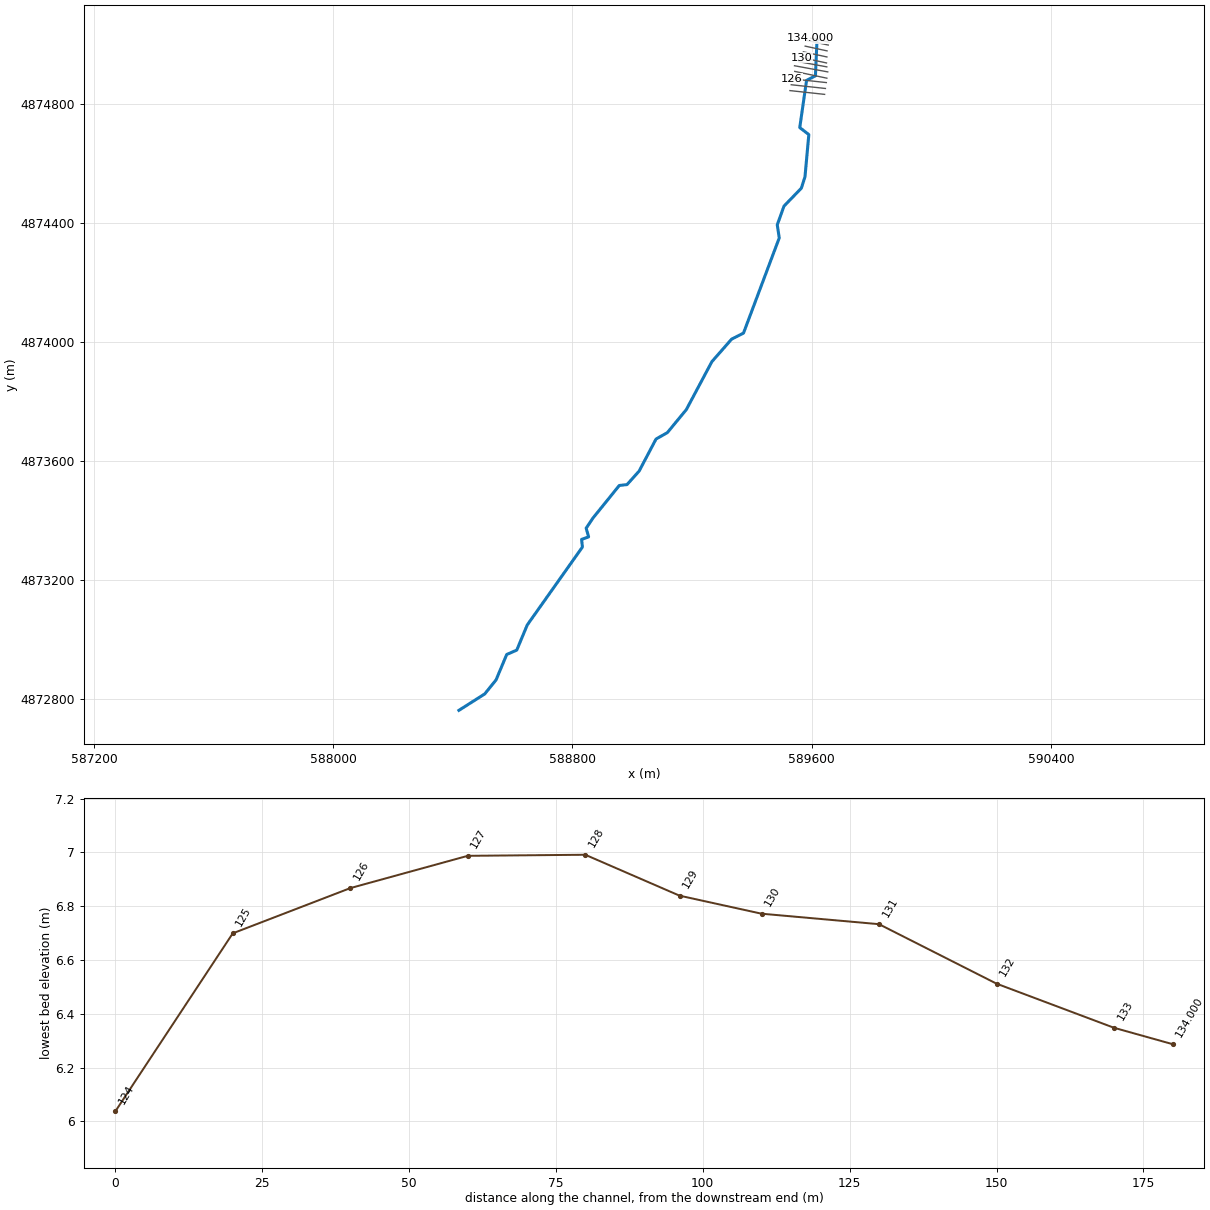
--- massa.prj (project) ---

Proj Title=massa
Current Plan=p70
Current HD=h01
Default Exp/Contr=0.3,0.1
SI Units
Geom File=g01
Geom File=g02
Geom File=g03
Geom File=g04
Geom File=g05
Flow File=f01
Unsteady File=u01
Unsteady File=u02
Unsteady File=u03
Unsteady File=u04
Unsteady File=u05
Unsteady File=u06
Unsteady File=u07
Unsteady File=u08
Unsteady File=u09
Unsteady File=u10
Unsteady File=u11
Unsteady File=u12
Unsteady File=u13
Unsteady File=u14
Unsteady File=u15
Unsteady File=u16
Unsteady File=u17
Unsteady File=u18
Unsteady File=u19
Unsteady File=u20
Unsteady File=u21
Unsteady File=u22
Unsteady File=u23
Unsteady File=u24
Unsteady File=u25
Unsteady File=u26
Unsteady File=u27
Unsteady File=u28
Unsteady File=u29
Unsteady File=u30
Unsteady File=u31
Unsteady File=u32
Unsteady File=u33
Unsteady File=u34
Unsteady File=u35
Unsteady File=u36
Unsteady File=u37
Unsteady File=u38
Unsteady File=u39
Unsteady File=u40
Unsteady File=u41
Unsteady File=u42
Unsteady File=u43
Unsteady File=u44
Unsteady File=u45
Unsteady File=u46
Unsteady File=u47
Unsteady File=u48
Unsteady File=u49
Unsteady File=u50
Unsteady File=u51
Unsteady File=u52
Unsteady File=u53
Unsteady File=u54
Unsteady File=u55
Unsteady File=u56
Unsteady File=u57
Unsteady File=u58
Unsteady File=u59
Unsteady File=u60
Unsteady File=u61
Unsteady File=u62
Unsteady File=u63
Unsteady File=u64
Plan File=p01
Plan File=p02
Plan File=p03
Plan File=p05
Plan File=p04
Plan File=p06
Plan File=p07
Plan File=p08
Plan File=p09
Plan File=p10
Plan File=p11
Plan File=p12
Plan File=p13
Plan File=p14
Plan File=p15
Plan File=p16
Plan File=p17
Plan File=p18
Plan File=p19
Plan File=p20
Plan File=p21
Plan File=p22
Plan File=p23
Plan File=p24
Plan File=p25
Plan File=p26
Plan File=p27
Plan File=p28
Plan File=p29
Plan File=p30
Plan File=p31
Plan File=p32
Plan File=p33
Plan File=p34
Plan File=p35
Plan File=p36
Plan File=p37
Plan File=p38
Plan File=p39
Plan File=p40
Plan File=p41
Plan File=p42
Plan File=p43
Plan File=p44
Plan File=p45
Plan File=p46
Plan File=p47
Plan File=p48
Plan File=p49
Plan File=p50
Plan File=p51
Plan File=p52
Plan File=p53
Plan File=p54
Plan File=p55
Plan File=p56
Plan File=p57
Plan File=p58
Plan File=p59
Plan File=p60
Plan File=p61
Plan File=p62
Plan File=p63
Plan File=p64
Plan File=p65
Plan File=p66
Plan File=p67
Plan File=p68
Plan File=p69
Plan File=p70
HD File=h01
Y Axis Title=Elevation
X Axis Title(PF)=Main Channel Distance
X Axis Title(XS)=Station
BEGIN DESCRIPTION:
END DESCRIPTION:
DSS File=..\..\..\SCORE\materiale\frigido\consegnamarzo2019\hec\FrigidoStCrnN7.dss
DSS File=dss
DSS Export Rating Curves= 0
DSS Export Rating Curve Sorted= 0
DSS Export Volume Flow Curves= 0
DXF Filename=..\..\..\SCORE\materiale\frigido\consegnamarzo2019\Frigido.
DXF OffsetX= 0
DXF OffsetY= 0
DXF ScaleX= 1
DXF ScaleY= 10

--- massa.p47 (plan) ---

Plan Title=SshR2_rc45_2015_2065_TR5
Program Version=6.30
Short Identifier=SshR2_rc45_2015_2065_TR5
Simulation Date=08FEB2019,0000,09FEB2019,2300
Geom File=g05
Flow File=u41
Mixed Flow
K Sum by GR= 0
Std Step Tol= 0.003
Critical Tol= 0.003
Num of Std Step Trials= 20
Max Error Tol= 0.1
Flow Tol Ratio= 0.001
Split Flow NTrial= 30
Split Flow Tol= 0.006
Split Flow Ratio= 0.02
Log Output Level= 0
Friction Slope Method= 1
Unsteady Friction Slope Method= 2
Unsteady Bridges Friction Slope Method= 1
Parabolic Critical Depth
Global Vel Dist= 0 , 0 , 0
Global Log Level= 0
CheckData=False
Encroach Param=-1 ,0,0, 0
Computation Interval=15SEC
Output Interval=1HOUR
Instantaneous Interval=1HOUR
Mapping Interval=1HOUR
Computation Time Step Use Courant=        0
Computation Time Step Use Time Series=    0
Computation Time Step Count To Double=0
Computation Time Step Max Doubling=0
Computation Time Step Max Halving=0
Computation Time Step Residence Courant=0
Computation Time Step TS=, 0
Computation Time Step TS=, 0
Computation Time Step TS=, 0
Computation Time Step TS=, 0
Computation Time Step TS=, 0
Computation Time Step TS=, 0
Computation Time Step TS=, 0
Computation Time Step TS=, 0
Computation Time Step TS=, 0
Computation Time Step TS=, 0
Computation Time Step TS=, 0
Computation Time Step TS=, 0
Computation Time Step TS=, 0
Computation Time Step TS=, 0
Computation Time Step TS=, 0
Computation Time Step TS=, 0
Computation Time Step TS=, 0
Computation Time Step TS=, 0
Computation Time Step TS=, 0
Computation Time Step TS=, 0
Computation Time Step TS=, 0
Computation Time Step TS=, 0
Computation Time Step TS=, 0
Computation Time Step TS=, 0
Computation Time Step TS=, 0
Computation Time Step TS=, 0
Computation Time Step TS=, 0
Computation Time Step TS=, 0
Computation Time Step TS=, 0
Computation Time Step TS=, 0
Computation Time Step TS=, 0
Computation Time Step TS=, 0
Computation Time Step TS=, 0
Computation Time Step TS=, 0
Computation Time Step TS=, 0
Computation Time Step TS=, 0
Computation Time Step TS=, 0
Computation Time Step TS=, 0
Computation Time Step TS=, 0
Computation Time Step TS=, 0
Computation Time Step TS=, 0
Computation Time Step TS=, 0
Computation Time Step TS=, 0
Computation Time Step TS=, 0
Computation Time Step TS=, 0
Computation Time Step TS=, 0
Computation Time Step TS=, 0
Computation Time Step TS=, 0
Computation Time Step TS=, 0
Computation Time Step TS=, 0
Run HTab=-1
Run UNet=-1
Run Sediment= 0
Run PostProcess=-1
Run WQNet= 0
Run RASMapper=-1
UNET Theta= 1
UNET Theta Warmup= 1
UNET ZTol= 0.006
UNET ZSATol= 0.006
UNET MxIter= 20
UNET Max Iter WO Improvement= 0
UNET MaxInSteps= 0
UNET DtIC= 0
UNET DtMin= 0
UNET MaxCRTS= 20
UNET WFStab= 2
UNET SFStab= 1
UNET WFX= 1
UNET SFX= 1
UNET Gravity=9.80665
UNET 1D Methodology=Finite Difference
UNET DSS MLevel= 4
UNET Pardiso=0
UNET DZMax Abort= 30
UNET Use Existing IB Tables=-1
UNET Froude Reduction=True
UNET Froude Limit= 0.8
UNET Froude Power= 4
UNET D1 Cores= 0
UNET WindReference=Eulerian
UNET WindDragFormulation=Hsu (1988)
UNET D2 Coriolis=0
UNET D2 Cores= 0
UNET D2 Theta= 1
UNET D2 Theta Warmup= 1
UNET D2 Z Tol= 0.003
UNET D2 Volume Tol= 0.003
UNET D2 Max Iterations= 20
UNET D2 Equation= 0
UNET D2 RampUpFraction=0.1
UNET D2 TimeSlices= 1
UNET D2 Turbulence Formulation=Non-Conservative (original)
UNET D2 Smagorinsky Mixing=0
UNET D2 BCVolumeCheck=0
UNET D2 Cores=0
UNET D2 SolverType=PARDISO (Direct)
UNET D2 Minimum Iterations= 3
UNET D2 Maximum Iterations= 30
UNET D2 Restart Number= 10
UNET D2 Relaxation Coeff=1.3
UNET D2 SOR Precondition Iterations= 10
UNET D2 ILUT Maximum Fill= 8
UNET D2 ILUT Tolerance=1E-08
UNET D2 Convergence Tolerance=0.00001
UNET D2 Name=north_01
UNET D2 Theta= 1
UNET D2 Theta Warmup= 1
UNET D2 Z Tol= 0.003
UNET D2 Volume Tol= 0.003
UNET D2 Max Iterations= 20
UNET D2 Equation= 1
UNET D2 RampUpFraction=0.1
UNET D2 TimeSlices= 1
UNET D2 Turbulence Formulation=Non-Conservative (original)
UNET D2 Smagorinsky Mixing=0
UNET D2 BCVolumeCheck=0
UNET D2 Cores=2
UNET D2 SolverType=PARDISO (Direct)
UNET D2 Minimum Iterations= 3
UNET D2 Maximum Iterations= 30
UNET D2 Restart Number= 10
UNET D2 Relaxation Coeff=1.3
UNET D2 SOR Precondition Iterations= 10
UNET D2 ILUT Maximum Fill= 0
UNET D2 ILUT Tolerance=0
UNET D2 Convergence Tolerance=0.00001
UNET D2 Name=sea_bc
UNET D2 Theta= 1
UNET D2 Theta Warmup= 1
UNET D2 Z Tol= 0.003
UNET D2 Volume Tol= 0.003
UNET D2 Max Iterations= 20
UNET D2 Equation= 1
UNET D2 RampUpFraction=0.1
UNET D2 TimeSlices= 1
UNET D2 Turbulence Formulation=Non-Conservative (original)
UNET D2 Smagorinsky Mixing=0
UNET D2 BCVolumeCheck=0
UNET D2 Cores=2
UNET D2 SolverType=PARDISO (Direct)
UNET D2 Minimum Iterations= 3
UNET D2 Maximum Iterations= 30
UNET D2 Restart Number= 10
UNET D2 Relaxation Coeff=1.3
UNET D2 SOR Precondition Iterations= 10
UNET D2 ILUT Maximum Fill= 0
UNET D2 ILUT Tolerance=0
UNET D2 Convergence Tolerance=0.00001
UNET D2 Name=south_01
UNET D2 Theta= 1
UNET D2 Theta Warmup= 1
UNET D2 Z Tol= 0.003
UNET D2 Volume Tol= 0.003
UNET D2 Max Iterations= 20
UNET D2 Equation= 1
UNET D2 RampUpFraction=0.1
UNET D2 TimeSlices= 1
UNET D2 Turbulence Formulation=Non-Conservative (original)
UNET D2 Smagorinsky Mixing=0
UNET D2 BCVolumeCheck=0
UNET D2 Cores=2
UNET D2 SolverType=PARDISO (Direct)
UNET D2 Minimum Iterations= 3
UNET D2 Maximum Iterations= 30
UNET D2 Restart Number= 10
UNET D2 Relaxation Coeff=1.3
UNET D2 SOR Precondition Iterations= 10
UNET D2 ILUT Maximum Fill= 0
UNET D2 ILUT Tolerance=0
UNET D2 Convergence Tolerance=0.00001
UNET D1D2 MaxIter= 0
UNET D1D2 ZTol=0.003
UNET D1D2 QTol=0.1
UNET D1D2 MinQTol=0.03
DSS File=dss
Write IC File= 0
Write IC File at Fixed DateTime=0
Write IC File at Sim End=0
Echo Input=False
Echo Parameters=False
Echo Output=False
Write Detailed= 0
HDF Write Warmup=0
HDF Write Time Slices=0
HDF Flush=0
HDF Compression= 1
HDF Chunk Size= 1
HDF Spatial Parts= 1
HDF Use Max Rows=0
HDF Fixed Rows= 1
Stage Flow Hydrograph=Frigido         ,Frigido         ,134
Stage Flow Hydrograph=Frigido         ,Frigido         ,133
Stage Flow Hydrograph=Frigido         ,Frigido         ,132
Stage Flow Hydrograph=Frigido         ,Frigido         ,131
Stage Flow Hydrograph=Frigido         ,Frigido         ,130
Stage Flow Hydrograph=Frigido         ,Frigido         ,129
Stage Flow Hydrograph=Frigido         ,Frigido         ,128
Stage Flow Hydrograph=Frigido         ,Frigido         ,127
Stage Flow Hydrograph=Frigido         ,Frigido         ,126
Stage Flow Hydrograph=Frigido         ,Frigido         ,125
Stage Flow Hydrograph=Frigido         ,Frigido         ,124
Stage Flow Hydrograph=Frigido         ,Frigido         ,123
Stage Flow Hydrograph=Frigido         ,Frigido         ,122
Stage Flow Hydrograph=Frigido         ,Frigido         ,121
Stage Flow Hydrograph=Frigido         ,Frigido         ,120
Stage Flow Hydrograph=Frigido         ,Frigido         ,119
Stage Flow Hydrograph=Frigido         ,Frigido         ,118
Stage Flow Hydrograph=Frigido         ,Frigido         ,117
Stage Flow Hydrograph=Frigido         ,Frigido         ,116
Stage Flow Hydrograph=Frigido         ,Frigido         ,115
Stage Flow Hydrograph=Frigido         ,Frigido         ,114
Stage Flow Hydrograph=Frigido         ,Frigido         ,113
Stage Flow Hydrograph=Frigido         ,Frigido         ,112
Stage Flow Hydrograph=Frigido         ,Frigido         ,111
Stage Flow Hydrograph=Frigido         ,Frigido         ,110
Stage Flow Hydrograph=Frigido         ,Frigido         ,109
Stage Flow Hydrograph=Frigido         ,Frigido         ,108
Stage Flow Hydrograph=Frigido         ,Frigido         ,107
Stage Flow Hydrograph=Frigido         ,Frigido         ,106
Stage Flow Hydrograph=Frigido         ,Frigido         ,105
Stage Flow Hydrograph=Frigido         ,Frigido         ,104
Stage Flow Hydrograph=Frigido         ,Frigido         ,103
Stage Flow Hydrograph=Frigido         ,Frigido         ,102
Stage Flow Hydrograph=Frigido         ,Frigido         ,101
Stage Flow Hydrograph=Frigido         ,Frigido         ,100
Stage Flow Hydrograph=Frigido         ,Frigido         ,99
Stage Flow Hydrograph=Frigido         ,Frigido         ,98
Stage Flow Hydrograph=Frigido         ,Frigido         ,97
Stage Flow Hydrograph=Frigido         ,Frigido         ,96
Stage Flow Hydrograph=Frigido         ,Frigido         ,95
Stage Flow Hydrograph=Frigido         ,Frigido         ,94
Stage Flow Hydrograph=Frigido         ,Frigido         ,93
Stage Flow Hydrograph=Frigido         ,Frigido         ,92
Stage Flow Hydrograph=Frigido         ,Frigido         ,91
Stage Flow Hydrograph=Frigido         ,Frigido         ,90
Stage Flow Hydrograph=Frigido         ,Frigido         ,89
Stage Flow Hydrograph=Frigido         ,Frigido         ,88
Stage Flow Hydrograph=Frigido         ,Frigido         ,87
Stage Flow Hydrograph=Frigido         ,Frigido         ,86
Stage Flow Hydrograph=Frigido         ,Frigido         ,85
Stage Flow Hydrograph=Frigido         ,Frigido         ,84
Stage Flow Hydrograph=Frigido         ,Frigido         ,83
Stage Flow Hydrograph=Frigido         ,Frigido         ,82
Stage Flow Hydrograph=Frigido         ,Frigido         ,81
Stage Flow Hydrograph=Frigido         ,Frigido         ,80
Stage Flow Hydrograph=Frigido         ,Frigido         ,79
Stage Flow Hydrograph=Frigido         ,Frigido         ,78
Stage Flow Hydrograph=Frigido         ,Frigido         ,77
Stage Flow Hydrograph=Frigido         ,Frigido         ,76
Stage Flow Hydrograph=Frigido         ,Frigido         ,75
Stage Flow Hydrograph=Frigido         ,Frigido         ,74
Stage Flow Hydrograph=Frigido         ,Frigido         ,73
Stage Flow Hydrograph=Frigido         ,Frigido         ,72
Stage Flow Hydrograph=Frigido         ,Frigido         ,71
Stage Flow Hydrograph=Frigido         ,Frigido         ,70
Stage Flow Hydrograph=Frigido         ,Frigido         ,69
Stage Flow Hydrograph=Frigido         ,Frigido         ,68
Stage Flow Hydrograph=Frigido         ,Frigido         ,67
Stage Flow Hydrograph=Frigido         ,Frigido         ,66
Stage Flow Hydrograph=Frigido         ,Frigido         ,65
Stage Flow Hydrograph=Frigido         ,Frigido         ,64
Stage Flow Hydrograph=Frigido         ,Frigido         ,63
Stage Flow Hydrograph=Frigido         ,Frigido         ,62
Stage Flow Hydrograph=Frigido         ,Frigido         ,61
Stage Flow Hydrograph=Frigido         ,Frigido         ,60
Stage Flow Hydrograph=Frigido         ,Frigido         ,59
Stage Flow Hydrograph=Frigido         ,Frigido         ,58
Stage Flow Hydrograph=Frigido         ,Frigido         ,57
Stage Flow Hydrograph=Frigido         ,Frigido         ,56
Stage Flow Hydrograph=Frigido         ,Frigido         ,55
Stage Flow Hydrograph=Frigido         ,Frigido         ,54
Stage Flow Hydrograph=Frigido         ,Frigido         ,53
Stage Flow Hydrograph=Frigido         ,Frigido         ,52
Stage Flow Hydrograph=Frigido         ,Frigido         ,51
Stage Flow Hydrograph=Frigido         ,Frigido         ,50
Stage Flow Hydrograph=Frigido         ,Frigido         ,49
Stage Flow Hydrograph=Frigido         ,Frigido         ,48
Stage Flow Hydrograph=Frigido         ,Frigido         ,47
Stage Flow Hydrograph=Frigido         ,Frigido         ,46
Stage Flow Hydrograph=Frigido         ,Frigido         ,45
Stage Flow Hydrograph=Frigido         ,Frigido         ,44
Stage Flow Hydrograph=Frigido         ,Frigido         ,43
Stage Flow Hydrograph=Frigido         ,Frigido         ,42
Stage Flow Hydrograph=Frigido         ,Frigido         ,41
Stage Flow Hydrograph=Frigido         ,Frigido         ,40
Stage Flow Hydrograph=Frigido         ,Frigido         ,39
Stage Flow Hydrograph=Frigido         ,Frigido         ,38
Stage Flow Hydrograph=Frigido         ,Frigido         ,37
Stage Flow Hydrograph=Frigido         ,Frigido         ,36
Stage Flow Hydrograph=Frigido         ,Frigido         ,35
Stage Flow Hydrograph=Frigido         ,Frigido         ,34
Stage Flow Hydrograph=Frigido         ,Frigido         ,33
Stage Flow Hydrograph=Frigido         ,Frigido         ,32
Stage Flow Hydrograph=Frigido         ,Frigido         ,31
Stage Flow Hydrograph=Frigido         ,Frigido         ,30
Stage Flow Hydrograph=Frigido         ,Frigido         ,29
Stage Flow Hydrograph=Frigido         ,Frigido         ,28
Stage Flow Hydrograph=Frigido         ,Frigido         ,27
Stage Flow Hydrograph=Frigido         ,Frigido         ,26
Stage Flow Hydrograph=Frigido         ,Frigido         ,25
Stage Flow Hydrograph=Frigido         ,Frigido         ,24
Stage Flow Hydrograph=Frigido         ,Frigido         ,23
Stage Flow Hydrograph=Frigido         ,Frigido         ,22
Stage Flow Hydrograph=Frigido         ,Frigido         ,21
Stage Flow Hydrograph=Frigido         ,Frigido         ,20
Stage Flow Hydrograph=Frigido         ,Frigido         ,19
Stage Flow Hydrograph=Frigido         ,Frigido         ,18
Stage Flow Hydrograph=Frigido         ,Frigido         ,17
Stage Flow Hydrograph=Frigido         ,Frigido         ,16
Stage Flow Hydrograph=Frigido         ,Frigido         ,15
Stage Flow Hydrograph=Frigido         ,Frigido         ,14
Stage Flow Hydrograph=Frigido         ,Frigido         ,13
Stage Flow Hydrograph=Frigido         ,Frigido         ,12
Stage Flow Hydrograph=Frigido         ,Frigido         ,11
Stage Flow Hydrograph=Frigido         ,Frigido         ,10
Stage Flow Hydrograph=Frigido         ,Frigido         ,9
Stage Flow Hydrograph=Frigido         ,Frigido         ,8
Stage Flow Hydrograph=Frigido         ,Frigido         ,7
Stage Flow Hydrograph=Frigido         ,Frigido         ,6
Stage Flow Hydrograph=Frigido         ,Frigido         ,5
Stage Flow Hydrograph=Frigido         ,Frigido         ,4
Stage Flow Hydrograph=Frigido         ,Frigido         ,3
Stage Flow Hydrograph=Frigido         ,Frigido         ,2
Stage Flow Hydrograph=Frigido         ,Frigido         ,1
Calibration Method= 0
Calibration Iterations= 20
Calibration Max Change=0.05
Calibration Tolerance=0.2
Calibration Maximum=1.5
Calibration Minimum=0.5
Calibration Optimization Method= 1
WQ AD Non Conservative
WQ ULTIMATE=-1
WQ Max Comp Step=1HOUR
WQ Output Interval=15MIN
WQ Output Selected Increments= 0
WQ Output face flow=0
WQ Output face velocity=0
WQ Output face area=0
WQ Output face dispersion=0
WQ Output cell volume=0
WQ Output cell surface area=0
WQ Output cell continuity=0
WQ Output cumulative cell continuity=0
WQ Output face conc=0
WQ Output face dconc_dx=0
WQ Output face courant=0
WQ Output face peclet=0
WQ Output face adv mass=0
WQ Output face disp mass=0
WQ Output cell mass=0
WQ Output cell source sink temp=0
WQ Output nsm pathways=0
WQ Output nsm derived pathways=0
WQ Create Restart=0
WQ Fixed Restart=0
WQ System Summary=0
WQ Write To DSS=0
Sorting and Armoring Iterations= 10
XS Update Threshold= 0.02
Bed Roughness Predictor= 0
Hydraulics Update Threshold= 0.02
Energy Slope Method= 0
Volume Change Method= 1
Sediment Retention Method= 0
Sediment TS Multiplier= 1
Warm Up Method= 0
XS Weighting Method= 0
Number of US Weighted Cross Sections= 1
Number of DS Weighted Cross Sections= 1
Upstream XS Weight=0
Main XS Weight=1
Downstream XS Weight=0
Number of DS XS's Weighted with US Boundary= 1
Upstream Boundary Weight= 1
Weight of XSs Associated with US Boundary= 0
Number of US XS's Weighted with DS Boundary= 1
Downstream Boundary Weight= 0.5
Weight of XSs Associated with DS Boundary= 0.5
Percentile Method= 0
Sediment Output Level= 4
Mass or Volume Output= 0
Output Increment Type= 1
Profile and TS Output Increment= 1
Transport Output Increment 1
XS Output Flag= 0
XS Output Increment= 10
Read HDF5 Sediment Hotstart= 0
Sediment Hotstart Type= 0
Write Gradation File= 0
Read Gradation Hotstart= 0
Write HDF5 File= 1
Write Binary Output= 1
Write DSS Sediment File= 0
DSS Sediment Output Type= 1
SV Curve= 0
Specific Gage Flag= 0
Subcell Erosion Methods= 0
Subcell Deposition Methods= 0
Advection Scheme= 1
Matrix Solver= 0
Implicit Weighting Factor= 1
Maximum Outer Loop Convergence Iterations= 5
Convergence Maximum Absolute= 0.001
Convergence RMSE= 0.0001
Grain Fractions Max Abs Error= 0.001
Max Subgrid Regions= 1
Max Subgrid Length Scale= 3.402823E+38
Initial Layer Thickness= 3.402823E+38
Min Layer Thickness= 3.402823E+38
Max Layer Thickness= 3.402823E+38
Number of Layers= 5

--- massa.u41 (unsteady flow) ---

Flow Title=SshR2_rc45_2015_2065_TR5
Program Version=6.30
BEGIN FILE DESCRIPTION:
SshR2_rc45_2015_2065_TR5
END FILE DESCRIPTION:
Use Restart= 0
Initial Flow Loc=Frigido         ,Frigido         ,134.000 ,15
Initial Flow Loc=Frigido         ,Frigido         ,134     ,15
Initial Storage Elev=north_01        ,0
Initial Storage Elev=sea_bc          ,0
Initial Storage Elev=south_01        ,0
Boundary Location=Frigido         ,Frigido         ,134     ,        ,                ,                ,                ,                                ,
Interval=1HOUR
Flow Hydrograph= 109
      15      15      15      15      15      15      15      15      15      15
      15      15      15      15      15      15      15      15      15      15
      15      15      15      15      15      15      15      15      15      15
      15      15      15      15      15      15      15      15      15      15
      15      15      15      15      15      15      15      15      15      15
      15      15      15      15      15      15      15      15      15      15
      15      15      15      15      15      15      15      15      15      15
      15      15      15      15      15      15      15      15      15      15
      15      15      15      15      15      15      15      15      15      15
      15      15      15      15      15      15      15      15      15      15
      15      15      15      15      15      15      15      15      15
Stage Hydrograph TW Check=0
Flow Hydrograph QMin= 15
Use DSS=False
Use Fixed Start Time=False
Is Critical Boundary=False
Boundary Location=Frigido         ,Frigido         ,1       ,        ,                ,                ,                ,                                ,
Interval=1HOUR
Stage Hydrograph= 181
       0       0       0       0       0       0       0       0       0       0
       0       0       0       0       0       0       0       0       0       0
       0       0       0       0       0       0       0       0       0       0
       0       0       0       0       0       0       0       0       0       0
       0       0       0       0       0       0       0       0       0       0
       0       0       0       0       0       0       0       0       0       0
       0       0       0       0       0       0       0       0       0       0
       0       0       0       0       0       0       0       0       0       0
       0       0       0       0       0       0       0       0       0       0
       0       0       0       0       0       0       0       0       0       0
       0       0       0       0       0       0       0       0       0       0
       0       0       0       0       0       0       0       0       0       0
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Use DSS=False
Use Fixed Start Time=False
Is Critical Boundary=False
Boundary Location=                ,                ,        ,        ,                ,sea_bc          ,                ,down_sea_bc                     ,
Interval=1HOUR
Stage Hydrograph= 99
    .225.3683333.5116667    .655.7983333.9416667   1.0851.2283331.371667   1.515
1.3716671.228333   1.085.9416667.7983333    .655.5116667.3683333    .225       0
       0       0       0       0       0       0       0       0       0       0
       0       0       0       0       0       0       0       0       0       0
       0       0       0       0       0       0       0       0       0       0
       0       0       0       0       0       0       0       0       0       0
       0       0       0       0       0       0       0       0       0       0
       0       0       0       0       0       0       0       0       0       0
       0       0       0       0       0       0       0       0       0       0
       0       0       0       0       0       0       0       0       0
Stage Hydrograph Use Initial Stage=-1
Stage Hydrograph TW Check=0
Use DSS=False
Use Fixed Start Time=False
Is Critical Boundary=False
Boundary Location=                ,                ,        ,        ,                ,north_01        ,                ,bc_sea_north                    ,
Interval=1HOUR
Stage Hydrograph= 99
    .225.3683333.5116667    .655.7983333.9416667   1.0851.2283331.371667   1.515
1.3716671.228333   1.085.9416667.7983333    .655.5116667.3683333    .225       0
       0       0       0       0       0       0       0       0       0       0
       0       0       0       0       0       0       0       0       0       0
       0       0       0       0       0       0       0       0       0       0
       0       0       0       0       0       0       0       0       0       0
       0       0       0       0       0       0       0       0       0       0
       0       0       0       0       0       0       0       0       0       0
       0       0       0       0       0       0       0       0       0       0
       0       0       0       0       0       0       0       0       0
Stage Hydrograph Use Initial Stage=-1
Stage Hydrograph TW Check=0
Use DSS=False
Use Fixed Start Time=False
Is Critical Boundary=False
Boundary Location=                ,                ,        ,        ,                ,south_01        ,                ,bc_sea_south                    ,
Interval=1HOUR
Stage Hydrograph= 99
    .225.3683333.5116667    .655.7983333.9416667   1.0851.2283331.371667   1.515
1.3716671.228333   1.085.9416667.7983333    .655.5116667.3683333    .225       0
       0       0       0       0       0       0       0       0       0       0
       0       0       0       0       0       0       0       0       0       0
       0       0       0       0       0       0       0       0       0       0
       0       0       0       0       0       0       0       0       0       0
       0       0       0       0       0       0       0       0       0       0
       0       0       0       0       0       0       0       0       0       0
       0       0       0       0       0       0       0       0       0       0
       0       0       0       0       0       0       0       0       0
Stage Hydrograph Use Initial Stage=-1
Stage Hydrograph TW Check=0
Use DSS=False
Use Fixed Start Time=False
Is Critical Boundary=False
Precipitation Mode=Disable
Wind Mode=No Wind Forces
Air Density Mode=Specified
Met BC=Precipitation|Expanded View=0
Met BC=Precipitation|Point Interpolation=Nearest
Met BC=Precipitation|Gridded Source=DSS
Met BC=Evapotranspiration|Expanded View=0
Met BC=Evapotranspiration|Point Interpolation=Nearest
Met BC=Evapotranspiration|Gridded Source=DSS
Met BC=Wind Speed|Expanded View=0
Met BC=Wind Speed|Point Interpolation=Nearest
Met BC=Wind Speed|Gridded Source=DSS
Met BC=Wind Direction|Expanded View=0
Met BC=Wind Direction|Point Interpolation=Nearest
Met BC=Wind Direction|Gridded Source=DSS
Met BC=Wind Velocity X|Expanded View=0
Met BC=Wind Velocity X|Point Interpolation=Nearest
Met BC=Wind Velocity X|Gridded Source=DSS
Met BC=Wind Velocity Y|Expanded View=0
Met BC=Wind Velocity Y|Point Interpolation=Nearest
Met BC=Wind Velocity Y|Gridded Source=DSS
Met BC=Air Density|Mode=Constant
Met BC=Air Density|Expanded View=0
Met BC=Air Density|Constant Value=1.225
Met BC=Air Density|Constant Units=kg/m3
Met BC=Air Density|Point Interpolation=Nearest
Met BC=Air Density|Gridded Source=DSS
Met BC=Air Temperature|Expanded View=0
Met BC=Air Temperature|Point Interpolation=Nearest
Met BC=Air Temperature|Gridded Source=DSS
Met BC=Humidity|Expanded View=0
Met BC=Humidity|Point Interpolation=Nearest
Met BC=Humidity|Gridded Source=DSS
Met BC=Air Pressure|Mode=Constant
Met BC=Air Pressure|Expanded View=0
Met BC=Air Pressure|Constant Value=1013.2
Met BC=Air Pressure|Constant Units=mb
Met BC=Air Pressure|Point Interpolation=Inv Distance
Met BC=Air Pressure|Gridded Source=DSS
Non-Newtonian Method= 0 ,
Non-Newtonian Constant Vol Conc=0
Non-Newtonian Yield Method= 0 ,
Non-Newtonian Yield Coef=0, 0
User Yeild=   0
Non-Newtonian Sed Visc= 0 ,
Non-Newtonian Obrian B=0
User Viscosity=0
User Viscosity Ratio=0
Herschel-Bulkley Coef=0, 0
Clastic Method= 0 ,
Coulomb Phi=0
Voellmy X=0
Non-Newtonian Hindered FV= 0
Non-Newtonian FV K=0
Non-Newtonian ds=0
Non-Newtonian Max Cv=0
Non-Newtonian Bulking Method= 0 ,
Non-Newtonian High C Transport= 0 ,
Lava Activation= 0
Temperature=1300,15,,15,14,980
Heat Ballance=1,1200,0.5,1,70,0.95
Viscosity=1000,,,
Profile Coefficient=4,1.3,
Lava Param=,2500,

--- massa.g05 (geometry) ---

Geom Title=FrigidoAttualeSshR2
Program Version=6.30

River Reach=Frigido         ,Frigido
Reach XY= 30
589617.912000464 4875015.9639999589612.6020053194874894.38199887
589582.8740008354874878.72399991 589560.129984174874720.25800174
 589590.448002934874696.81999968589577.5849963454874554.77000086
589565.3579970864874516.56100069589507.4279959954874456.56500161
589484.9559994364874393.70100018589491.5580033244874349.53799893
589371.9749959394874029.99000291589332.2049913914874009.57000646
589266.2690020914873934.02699843589180.8680019134873773.05699856
 589117.367001224873695.68599908589079.4929941834873674.10500437
589023.0169900924873566.48600738588982.4589992384873521.12100072
588956.5960005644873518.06599946588868.0180006614873407.95299957
588845.8539987394873374.65100081588854.1210013814873345.48499911
588830.5750036684873336.89599763  588833.33699964873311.29100026
588648.8489991234873049.53800053588613.7520003284872965.12699979
588580.1109997124872950.29300024588544.658000626 4872865.2239995
 588506.660999354872817.88400055588420.2456189374872762.79469848
Reach Downstream Storage Area=sea_bc

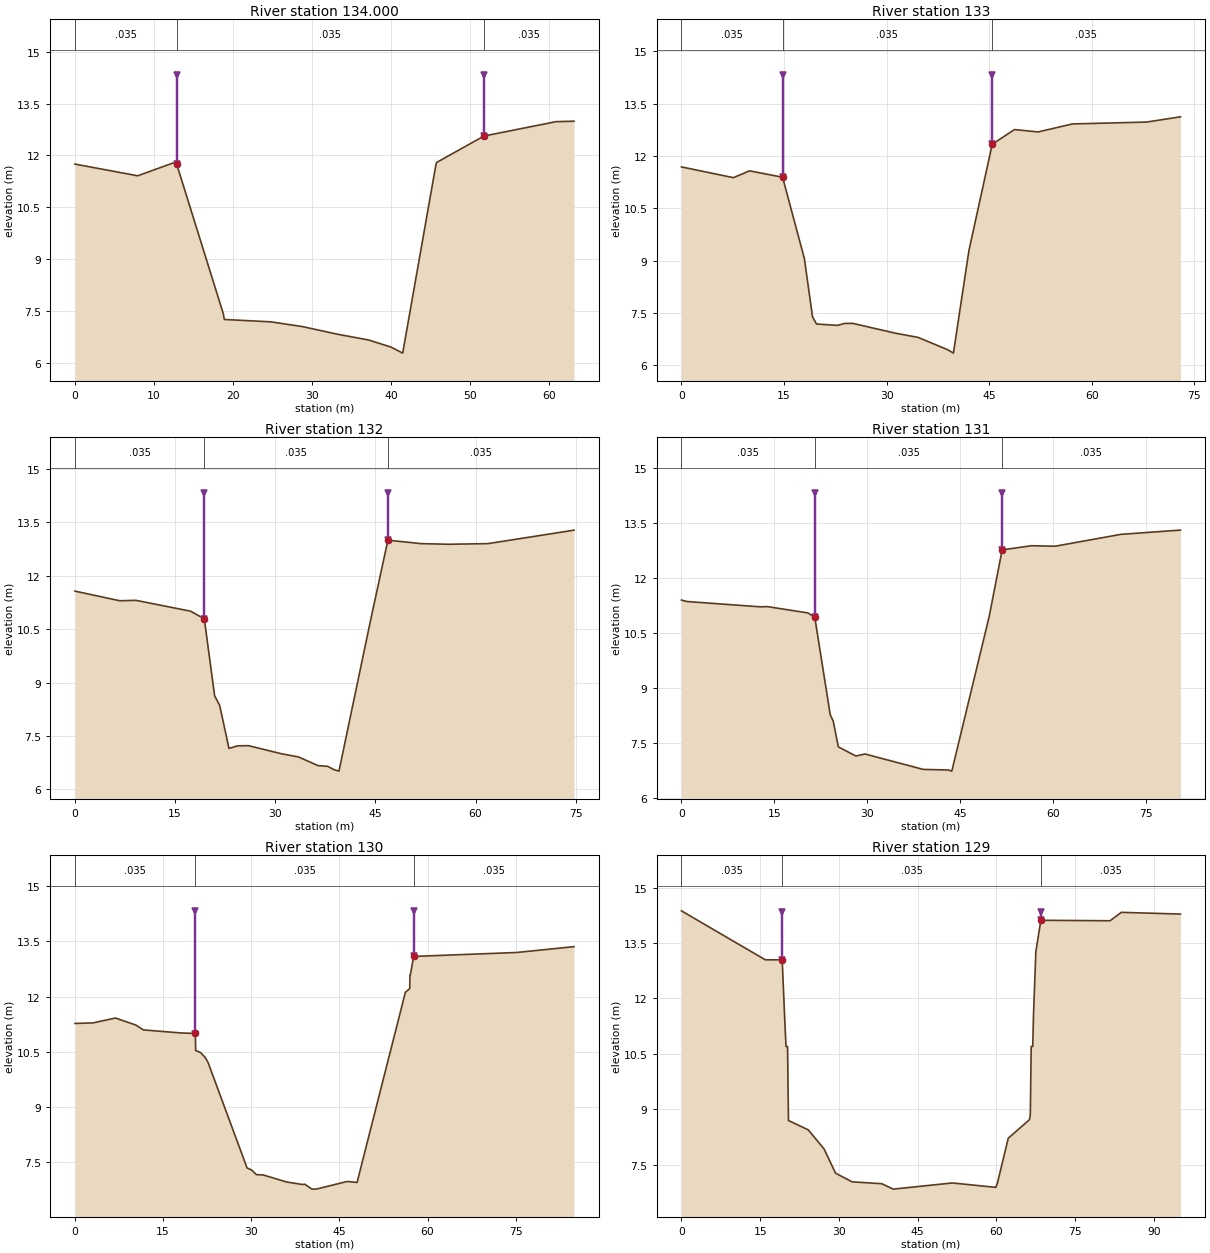
Type RM Length L Ch R = 1 ,134.000 ,10,10,10
XS GIS Cut Line= 6
      589658.439     4875007.126      589645.882     4875009.865
       589639.94      4875011.16      589634.212      4875012.41
      589625.931     4875014.215      589596.727     4875020.584
#Sta/Elev= 18
       0   11.75   7.945  11.412  12.386   11.78  12.852  11.763  18.781    7.42
  18.884   7.277  18.934   7.259  24.797   7.191  28.764   7.055  33.272   6.831
  37.155   6.667  39.985   6.463  41.479   6.287  45.651  11.689  45.772  11.797
  51.766  12.561  60.881  12.976  63.162   12.99
#Mann= 3 ,0,0
       0    .035       0  12.852    .035       0  51.766    .035       0
Levee=-1,12.85225,14.33,-1,51.76576,14.33,,
Bank Sta=12.852,51.766
XS Rating Curve= 0 ,0
Exp/Cntr=0.3,0.1

Type RM Length L Ch R = 1 ,133     ,20,20,20
XS GIS Cut Line= 6
      589655.388     4874997.557      589645.662     4874999.677
      589633.101     4875002.417      589610.987     4875007.239
      589599.541     4875009.736        589584.1     4875013.103
#Sta/Elev= 21
       0  11.689   7.591   11.38   9.954  11.576  14.787  11.393  17.968   9.064
  19.165   7.391  19.746   7.183  22.811   7.144  23.822   7.199  25.041   7.202
  31.311   6.919  34.584     6.8  38.948   6.444  39.764   6.348   42.04   9.296
  45.444   12.34   48.69   12.76  52.138  12.692   57.16  12.921  68.007  12.975
  72.963  13.126
#Mann= 3 ,0,0
       0    .035       0  14.787    .035       0  45.444    .035       0
Levee=-1,14.7874,14.33,-1,45.44436,14.33,,
Bank Sta=14.787,45.444
XS Rating Curve= 0 ,0
Exp/Cntr=0.3,0.1

Type RM Length L Ch R = 1 ,132     ,20,20,20
XS GIS Cut Line= 6
      589651.371     4874977.962      589632.446     4874982.089
      589628.837     4874982.877       589621.23     4874984.535
      589618.657     4874985.097      589578.346     4874993.888
#Sta/Elev= 22
       0  11.568   6.709  11.298   9.114   11.31  17.323  11.005   19.37   10.79
  20.915   8.628  21.673   8.356  23.064   7.151  24.386   7.223  25.995   7.227
  30.849   7.003  33.483    6.91  36.419   6.666  37.846   6.647  38.799   6.553
  39.539   6.512  44.315  10.787  46.868      13  51.833  12.903  55.984  12.885
  61.862  12.903  74.741  13.281
#Mann= 3 ,0,0
       0    .035       0   19.37    .035       0  46.868    .035       0
Levee=-1,19.36976,14.33,-1,46.8684,14.33,,
Bank Sta=19.37,46.868
XS Rating Curve= 0 ,0
Exp/Cntr=0.3,0.1

Type RM Length L Ch R = 1 ,131     ,20,20,20
XS GIS Cut Line= 6
      589650.932     4874957.588      589650.063     4874957.778
       589637.38     4874960.543      589627.466     4874962.706
       589623.41      4874963.59      589572.218     4874974.754
#Sta/Elev= 20
       0  11.402     .89  11.363   12.72  11.218   13.87  11.224  20.391  11.052
  21.527  10.932  24.018   8.275  24.503     8.1  25.328   7.395  28.169   7.145
  29.632   7.201  39.036    6.78  43.087   6.764  43.649   6.733  49.679  10.951
  51.779  12.773   56.53  12.886  60.321  12.872  70.934  13.196  80.564  13.313
#Mann= 3 ,0,0
       0    .035       0  21.527    .035       0  51.779    .035       0
Levee=-1,21.52737,14.33,-1,51.7791,14.33,,
Bank Sta=21.527,51.779
XS Rating Curve= 0 ,0
Exp/Cntr=0.3,0.1

Type RM Length L Ch R = 1 ,130     ,13.959,13.959,13.959
XS GIS Cut Line= 6
      589649.535     4874937.423      589629.511     4874941.789
      589629.469     4874941.799      589620.152     4874943.831
      589604.241       4874947.3      589566.551      4874955.52
#Sta/Elev= 29
       0  11.272   3.067  11.286   6.891  11.419  10.344  11.229  11.636  11.096
  17.932  11.015  20.494  10.999  20.538  10.537  21.375  10.481  22.135  10.353
  22.651  10.212  29.287   7.347  30.074   7.289  30.878   7.166  32.047   7.156
  36.045   6.965  38.729   6.897  39.116   6.906  40.327   6.772  41.106   6.774
  46.358   6.981  48.012   6.953  56.233  12.116  56.978  12.218  57.011  12.579
  57.066   12.58  57.639  13.091  75.215  13.199  84.934  13.357
#Mann= 3 ,0,0
       0    .035       0  20.494    .035       0  57.639    .035       0
Levee=-1,20.49445,14.33,-1,57.63856,14.33,,
Bank Sta=20.494,57.639
XS Rating Curve= 0 ,0
Exp/Cntr=0.3,0.1

Type RM Length L Ch R = 1 ,129     ,16.041,16.041,16.041
XS GIS Cut Line= 6
      589650.642     4874924.288      589631.055     4874927.918
      589630.596     4874928.004      589615.302     4874930.838
      589610.975     4874931.641      589557.169     4874941.614
#Sta/Elev= 28
       0  14.373  15.973  13.047  19.192  13.046  19.697  11.368  19.921    10.7
  20.214    10.7  20.388   8.696  24.175   8.442  27.186   7.923  29.355   7.271
  32.512   7.036  38.158   6.986  40.343   6.839  51.598   7.006  59.879   6.887
  60.217   7.015  62.255   8.217   66.26   8.714  66.416   8.797  66.465   8.899
   66.63  10.702  66.926  10.702  67.059  11.518  67.517   13.27   68.47  14.117
  81.655  14.104  83.801  14.332  95.065  14.285
#Mann= 3 ,0,0
       0    .035       0  19.192    .035       0   68.47    .035       0
Levee=-1,19.19246,14.33,-1,68.46979,14.33,,
Bank Sta=19.192,68.47
XS Rating Curve= 0 ,0
Exp/Cntr=0.3,0.1

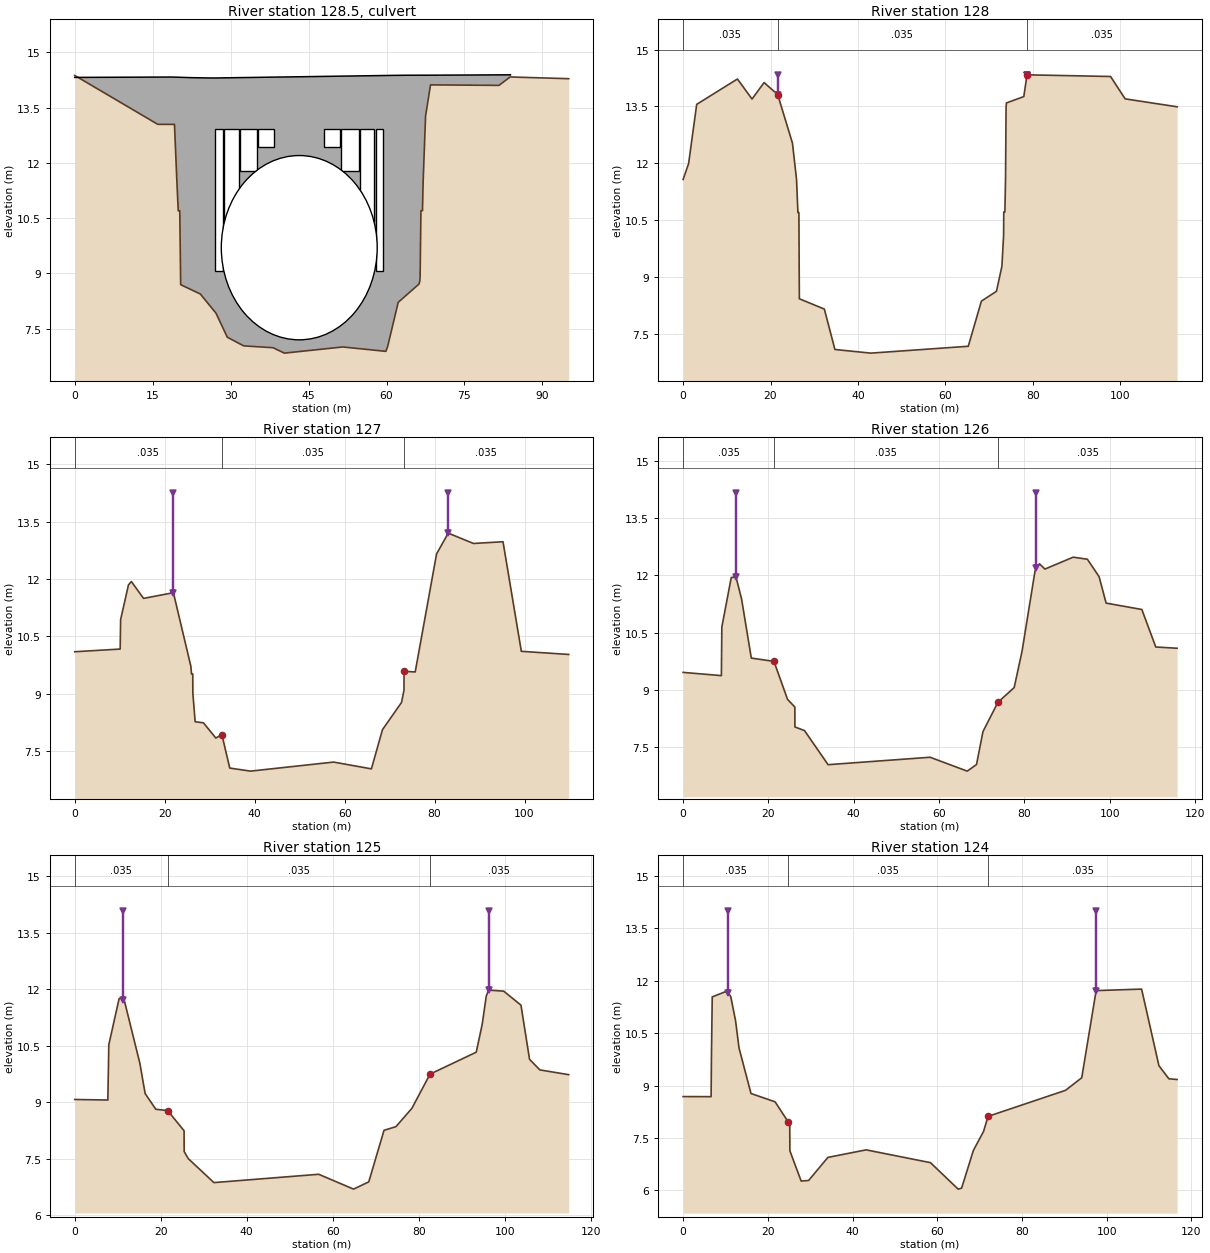
Type RM Length L Ch R = 2 ,128.5   ,,,
BEGIN DESCRIPTION:
Ponte Obelisco
END DESCRIPTION:
Bridge Culvert--1,0,-1,-1, 0
Deck Dist Width WeirC Skew NumUp NumDn MinLoCord MaxHiCord MaxSubmerge Is_Ogee
1,14.2,1.4,0, 34, 33, , , 0.98, 0, 0,0,,
       0  18.776  19.791  22.277  22.915    25.4   26.79  27.057  27.235  30.307
  30.486  33.557  33.735  36.807  39.879  40.057  42.781   42.98  46.399  46.557
  46.736  49.807  49.985  53.057  53.236  56.307  56.485  59.556  60.776  63.261
  64.276   65.29  67.777   83.86
   14.32   14.33  14.325  14.314  14.312  14.306  14.304  14.305  14.305  14.311
  14.312  14.318  14.318  14.325  14.331  14.331  14.337  14.337  14.344  14.345
  14.345  14.351  14.352  14.358  14.358  14.365  14.365  14.371  14.374  14.378
  14.379  14.379   14.38   14.39
                                                                                
                                                                                
                                                                                
                                
       0  18.776  19.791  22.277  22.915    25.4   26.79  29.276  30.291  32.777
  33.197   36.24  36.447  39.489  39.697   42.74  42.946  43.153  46.196   46.38
  49.768  49.999  52.697   55.74  55.946   58.99  59.196   62.24  62.447   65.49
  65.696  67.777   83.86
   14.32   14.33  14.325  14.314  14.312  14.306  14.304  14.301  14.301  14.302
  14.303   14.31   14.31  14.317  14.317  14.324  14.325  14.325  14.332  14.332
   14.34   14.34  14.346  14.353  14.354   14.36  14.361  14.368  14.368  14.375
  14.375   14.38   14.39
                                                                                
                                                                                
                                                                                
                        
BR Coef=-1 , 0 , 0 ,, 0 ,,,0.8,-1,,0,
WSPro=,,,, 1 ,,,, 0 ,,,, 0 ,,,,-1 ,-1 ,-1 , 0 , 0 , 0 , 0 , 0
Multiple Barrel Culv=2,3.85,1.47,14.2,0.025,0.35,1,58,1,9.072,9.072, 2,Culvert #1  , 2 ,1
  27.792  33.932  58.622  64.762
BC Culvert Barrel=1,Barrel #1,0
BC Culvert Barrel=2,Barrel #2,0
Culvert Bottom n=0.025
Multiple Barrel Culv=2,2.5,2.85,14.2,0.025,0.35,1,58,2,10.422,10.422, 2,Culvert #2  , 0 ,1
  30.152  36.292  56.262  62.402
BC Culvert Barrel=1,Barrel #1,0
BC Culvert Barrel=2,Barrel #2,0
Culvert Bottom n=0.025
Multiple Barrel Culv=2,1.15,3.32,14.2,0.025,0.35,1,58,2,11.772,11.772, 2,Culvert #3  , 0 ,1
  33.432  39.572  52.982  59.122
BC Culvert Barrel=1,Barrel #1,0
BC Culvert Barrel=2,Barrel #2,0
Culvert Bottom n=0.025
Multiple Barrel Culv=2,0.5,3.1,14.2,0.025,0.35,1,58,2,12.422,12.422, 2,Culvert #4  , 0 ,1
  36.832  42.972  49.582  55.722
BC Culvert Barrel=1,Barrel #1,0
BC Culvert Barrel=2,Barrel #2,0
Culvert Bottom n=0.025
Culvert=5,5,30,14.2,0.035,0.35,1,41,1,7.2,43.207,7.2,49.347,Culvert #5  , 0 ,1
  43.207  49.347
BC Culvert Barrel=1,,0
Culvert Bottom n=0.035
BC Design=,, 0 ,, 0 ,,,,,,
BC Use User HTab Curves=0
BC User HTab FreeFlow(D)= 0

Type RM Length L Ch R = 1 ,128     ,20,20,20
XS GIS Cut Line= 6
      589653.755     4874907.396      589581.025     4874920.877
      589575.446     4874921.912      589571.298      4874922.68
      589563.049      4874924.21       589542.63     4874927.994
#Sta/Elev= 30
       0  11.572   1.258  11.992   3.108  13.553  12.425  14.222  15.769  13.693
  18.528  14.128  21.631  13.813  25.017   12.53  25.946  11.577  26.266  10.698
  26.488  10.698  26.595   8.425  32.311   8.153  34.731   7.087  42.964   6.991
  65.243   7.172  68.246   8.363   71.69   8.622  72.936   9.281  73.324  10.094
  73.362  10.715  73.622  10.715  73.769  11.606  73.889  13.469  73.969   13.59
  77.946  13.758  78.686  14.332  97.796  14.288 101.132  13.698 113.018  13.489
#Mann= 3 ,0,0
       0    .035       0  21.631    .035       0  78.686    .035       0
Levee=-1,21.63123,14.33,-1,78.68591,14.33,,
Bank Sta=21.631,78.686
XS Rating Curve= 0 ,0
Exp/Cntr=0.3,0.1

Type RM Length L Ch R = 1 ,127     ,20,20,20
XS GIS Cut Line= 6
      589650.812     4874886.285       589637.01     4874889.209
      589621.659     4874892.463      589618.814     4874893.065
      589545.328     4874908.638      589543.383     4874909.051
#Sta/Elev= 30
       0  10.102  10.101  10.172    10.2   10.94   11.94  11.845  12.588  11.934
  15.299  11.494  21.933  11.643   25.83   9.715  25.954   9.522  26.237   9.523
  26.258    9.02  26.768   8.276  28.619   8.247  31.369    7.85  32.708   7.941
  34.464   7.067  39.058   6.987  57.554   7.223  65.953   7.046  68.413   8.069
  72.653   8.779  73.192   9.099  73.214   9.592  75.691   9.574  80.442  12.655
  83.032  13.197  88.646  12.927   95.21  12.972  99.282  10.113 109.815  10.031
#Mann= 3 ,0,0
       0    .035       0  32.708    .035       0  73.214    .035       0
Levee=-1,21.93349,14.24834,-1,83.03181,14.24834,,
Bank Sta=32.708,73.214
XS Rating Curve= 0 ,0
Exp/Cntr=0.3,0.1

Type RM Length L Ch R = 1 ,126     ,20,20,20
XS GIS Cut Line= 6
      589649.053     4874871.481      589591.506      4874877.78
      589582.874     4874878.724      589576.403     4874879.433
        589570.1     4874880.122      589533.973     4874884.077
#Sta/Elev= 30
       0   9.457   8.967   9.372   9.073  10.646  11.282  11.946  12.404  11.957
  13.706  11.378  15.981   9.832  21.289   9.746  24.467    8.75  26.179   8.549
  26.202   8.026  28.452    7.93  33.976   7.036  57.891   7.231  66.574   6.867
  68.757   7.038  70.275   7.905  73.798   8.676  77.582   9.057  79.424  10.006
  82.503  12.136  83.509  12.305   84.79  12.167   91.42  12.479  94.745  12.425
  97.493  11.966  99.135  11.274 107.502  11.107 110.771  10.123 115.767   10.09
#Mann= 3 ,0,0
       0    .035       0  21.289    .035       0  73.798    .035       0
Levee=-1,12.40358,14.16668,-1,82.80653,14.16668,,
Bank Sta=21.289,73.798
XS Rating Curve= 0 ,0
Exp/Cntr=0.3,0.1

Type RM Length L Ch R = 1 ,125     ,20,20,20
XS GIS Cut Line= 6
       589645.93     4874851.703      589608.569     4874855.792
      589583.562      4874858.53       589563.92     4874860.679
      589548.424     4874862.376      589531.706     4874864.205
#Sta/Elev= 30
       0   9.078   7.699   9.064   7.929  10.534  10.321  11.753   10.86  11.764
  11.524  11.709  15.153  10.038  16.377   9.235  18.863   8.818  21.617   8.784
  25.432   8.248  25.456   7.696  26.413   7.508  32.374   6.872  56.749   7.093
  64.867   6.699  68.399   6.892  71.941   8.259  74.727   8.358  78.426   8.843
  82.647   9.751  93.395  10.333  94.781  11.071  95.728  11.822  96.265  11.981
  99.789  11.953 103.805  11.581 105.794  10.145 108.201   9.863 114.906   9.737
#Mann= 3 ,0,0
       0    .035       0  21.617    .035       0  82.647    .035       0
Levee=-1,11.33427,14.08502,-1,96.26452,14.08502,,
Bank Sta=21.617,82.647
XS Rating Curve= 0 ,0
Exp/Cntr=0.3,0.1

Type RM Length L Ch R = 1 ,124     ,20,20,20
XS GIS Cut Line= 6
      589643.284     4874831.873      589630.976     4874833.221
      589630.164     4874833.309      589628.162     4874833.529
      589618.268     4874834.611      589527.364     4874844.561
#Sta/Elev= 30
       0   8.686   6.607   8.684   6.686   9.819   6.875   11.54  10.344  11.705
  11.253  11.546  12.382  10.856  13.198  10.078  16.026   8.774  21.715   8.536
  24.871   7.948  25.165   7.948  25.201   7.135  27.862   6.269  29.622   6.284
  34.172   6.945  43.207   7.161  58.389   6.795  64.927   6.037  65.744   6.065
  68.522   7.144  70.931    7.69  71.983   8.119  90.272   8.865  94.103   9.225
  97.505   11.72 108.236  11.763 112.324    9.57  114.68   9.195 116.612   9.175
#Mann= 3 ,0,0
       0    .035       0  24.871    .035       0  71.983    .035       0
Levee=-1,10.65125,14.00337,-1,97.50489,14.00337,,
Bank Sta=24.871,71.983
XS Rating Curve= 0 ,0
Exp/Cntr=0.3,0.1