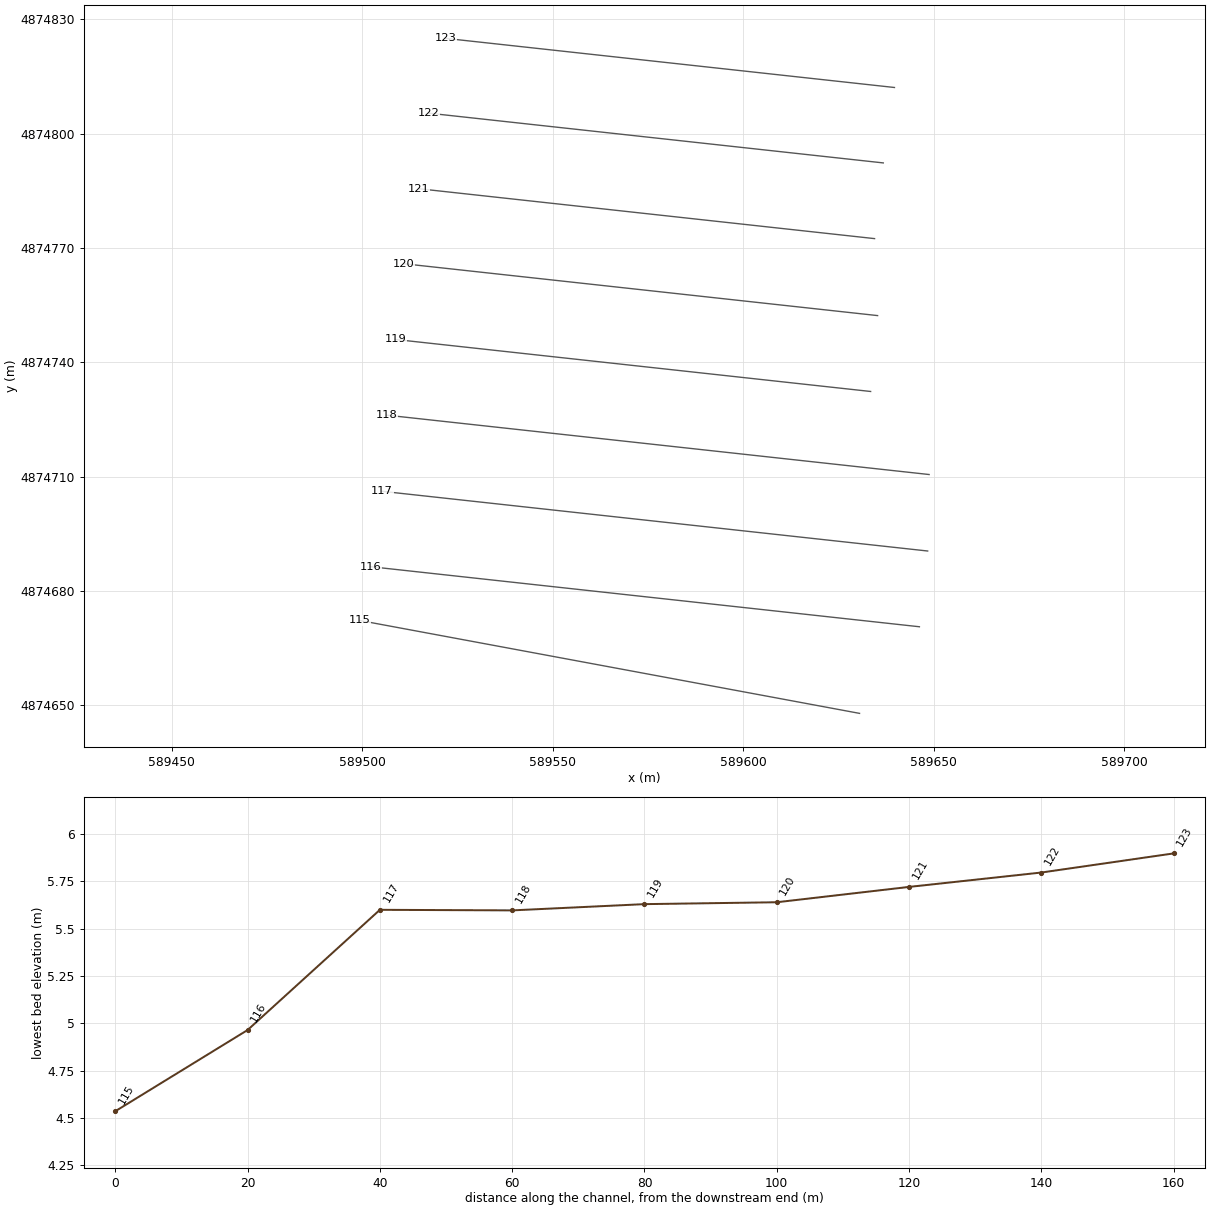
HEC-RAS study massa.prj: massa

--- massa.g05 (geometry) --- (continued)

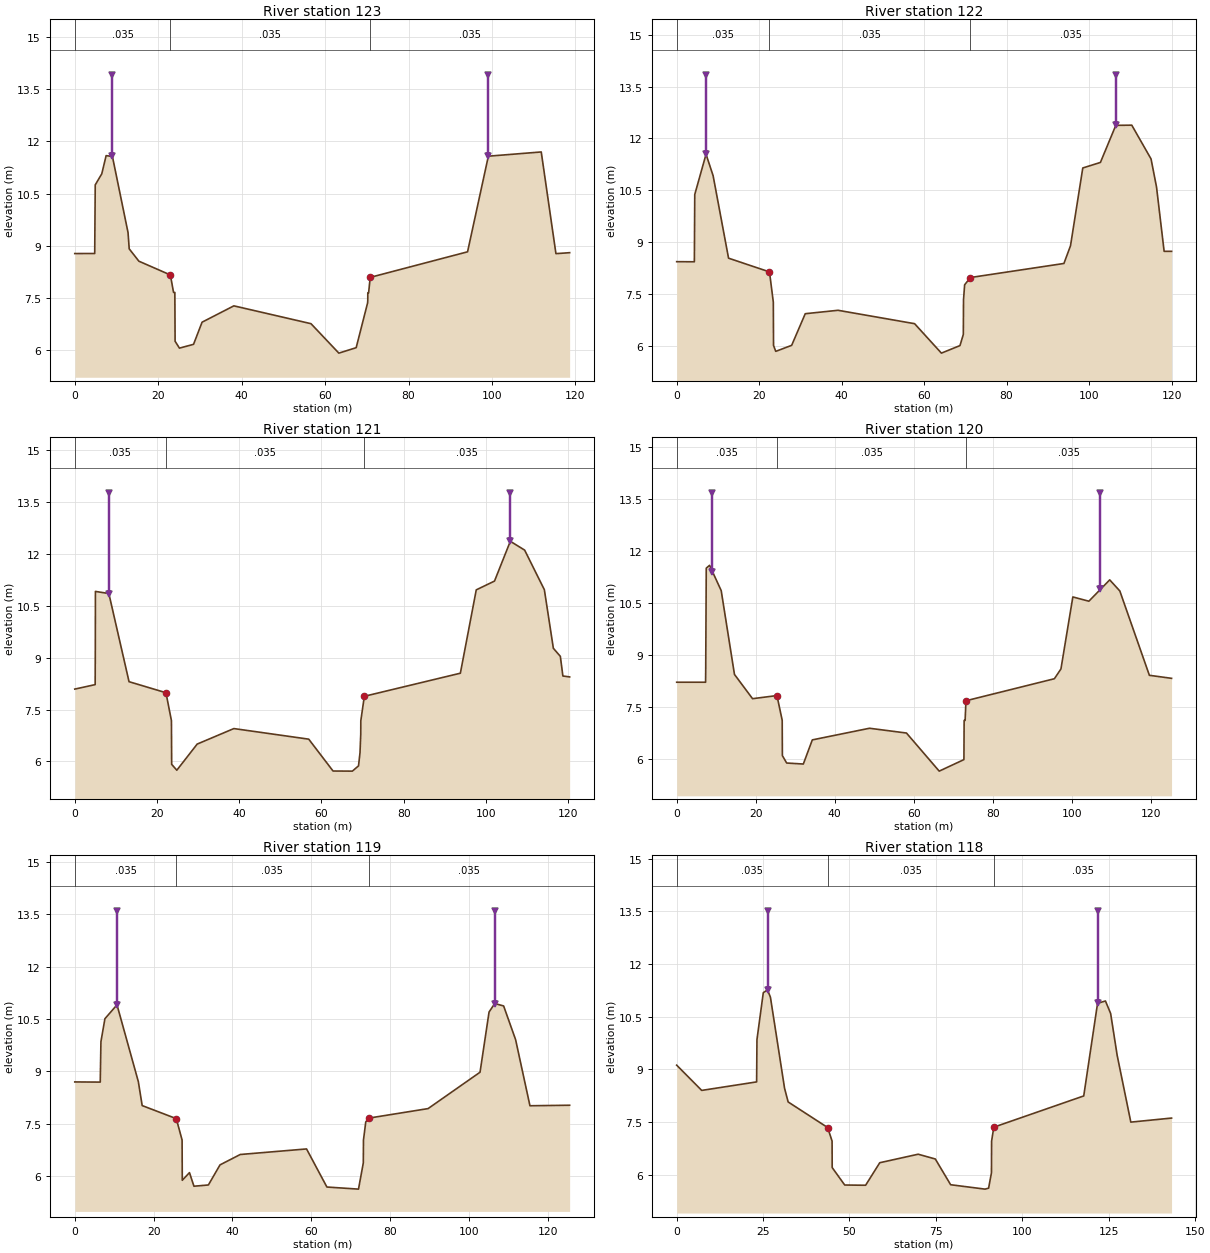
Type RM Length L Ch R = 1 ,123     ,20,20,20
XS GIS Cut Line= 6
      589639.726     4874812.143      589625.107     4874813.744
      589615.888     4874814.753      589614.792     4874814.872
       589611.43     4874815.241      589521.833     4874825.047
#Sta/Elev= 30
       0   8.769   4.777    8.77   4.903  10.749   6.468  11.067   7.512  11.592
   9.019  11.568  12.762   9.374  13.047   8.904  15.369   8.548  22.911   8.152
  23.671   7.648   23.98   7.648  24.042    6.24  25.083   6.042  28.465   6.152
  30.506    6.79  38.128   7.261  56.607   6.747  63.287   5.898  67.438   6.055
  70.174   7.345  70.216   7.411  70.225   7.634  70.419   7.635  70.803   8.082
  94.132   8.819  99.118  11.576  111.79  11.698 115.313   8.766 118.597   8.794
#Mann= 3 ,0,0
       0    .035       0  22.911    .035       0  70.803    .035       0
Levee=-1,8.917026,13.92171,-1,99.11751,13.92171,,
Bank Sta=22.911,70.803
XS Rating Curve= 0 ,0
Exp/Cntr=0.3,0.1

Type RM Length L Ch R = 1 ,122     ,20,20,20
XS GIS Cut Line= 6
      589636.797     4874792.345        589591.6     4874797.291
      589549.664     4874801.882      589544.621     4874802.433
       589543.45     4874802.562      589517.504     4874805.402
#Sta/Elev= 30
       0    8.44   4.285   8.437   4.382  10.381   7.119  11.545   8.837  10.923
  12.578   8.541  22.506   8.144  23.432   7.272  23.486    6.02  24.026   5.848
  27.883   6.022  31.178   6.936  39.127   7.035  57.692   6.648  64.195   5.797
  68.702   6.015  69.513   6.338  69.555   7.334  69.829   7.772  71.244   7.982
  93.905   8.388  95.504     8.9  98.481  11.148 102.758  11.308 106.488   12.38
 110.361  12.385 115.036  11.409 116.363  10.598 118.208   8.739 120.006   8.739
#Mann= 3 ,0,0
       0    .035       0  22.506    .035       0  71.244    .035       0
Levee=-1,7.119201,13.84005,-1,106.4882,13.84005,,
Bank Sta=22.506,71.244
XS Rating Curve= 0 ,0
Exp/Cntr=0.3,0.1

Type RM Length L Ch R = 1 ,121     ,20,20,20
XS GIS Cut Line= 6
      589634.502     4874772.476      589607.192     4874775.465
      589604.907     4874775.716      589542.351     4874782.562
      589518.386     4874785.186      589514.851     4874785.572
#Sta/Elev= 30
       0    8.09   4.957   8.219   4.995   9.292   5.021  10.911   8.287   10.85
  13.198   8.304  22.178   7.985   23.51   7.179  23.564   5.918  24.815   5.747
  29.772   6.502  38.692    6.95  56.909   6.644  62.819   5.724  67.521   5.721
  69.013   5.873  69.375    6.25  69.557   6.792  69.573   7.176  70.429   7.882
  93.786   8.549  97.652  10.956 102.093   11.21 105.938  12.359 109.421  12.104
 114.218   10.96 116.406   9.268 118.103   9.036 118.724   8.468 120.366   8.442
#Mann= 3 ,0,0
       0    .035       0  22.178    .035       0  70.429    .035       0
Levee=-1,8.287235,13.75839,-1,105.938,13.75839,,
Bank Sta=22.178,70.429
XS Rating Curve= 0 ,0
Exp/Cntr=0.3,0.1

Type RM Length L Ch R = 1 ,120     ,20,20,20
XS GIS Cut Line= 6
      589635.299      4874752.27      589626.301     4874753.254
      589620.837     4874753.853      589602.045     4874755.909
      589586.804     4874757.578      589510.838     4874765.892
#Sta/Elev= 30
       0   8.207    7.31   8.207   7.345   8.562   7.481  11.502   8.323  11.583
  11.265  10.852  14.618   8.433  19.193   7.732   25.37   7.822  26.696   7.107
   26.74   6.089  27.825   5.874  32.043   5.845  34.314   6.542  48.785   6.878
  58.138    6.74   66.42    5.64  72.649   5.971  72.676   6.012  72.725   7.105
  72.977   7.104  73.188   7.672  95.562   8.308  97.222   8.591  100.23   10.67
 104.286  10.547 109.561  11.163 112.116  10.843 119.596   8.407 125.204    8.32
#Mann= 3 ,0,0
       0    .035       0   25.37    .035       0  73.188    .035       0
Levee=-1,9.051645,13.67673,-1,107.2125,13.67673,,
Bank Sta=25.37,73.188
XS Rating Curve= 0 ,0
Exp/Cntr=0.3,0.1

Type RM Length L Ch R = 1 ,119     ,20,20,20
XS GIS Cut Line= 6
      589633.471      4874732.35      589611.039     4874734.805
      589608.353       4874735.1      589604.543     4874735.516
      589596.841      4874736.36      589508.662     4874746.011
#Sta/Elev= 30
       0   8.698    6.46   8.693   6.635    9.85   7.645  10.507  10.709  10.904
  16.128   8.705  17.098   8.021  25.748   7.648  27.226   7.036  27.275   5.883
  29.101   6.102  30.233   5.713  33.899   5.749  36.849   6.324  41.975   6.621
  58.803    6.78  63.967    5.69  71.984    5.63  73.204   6.381  73.243   7.033
  73.822    7.55  74.532   7.661   89.64   7.935  102.82   8.976  105.11  10.699
  106.55  10.942 108.805  10.873 111.846   9.907 115.484   8.016 125.554   8.031
#Mann= 3 ,0,0
       0    .035       0  25.748    .035       0  74.532    .035       0
Levee=-1,10.70856,13.59507,-1,106.5496,13.59507,,
Bank Sta=25.748,74.532
XS Rating Curve= 0 ,0
Exp/Cntr=0.3,0.1

Type RM Length L Ch R = 1 ,118     ,20,20,20
XS GIS Cut Line= 6
      589648.821     4874710.551      589607.307     4874715.094
      589604.402     4874715.413      589602.721     4874715.596
      589600.774      4874715.81      589506.486      4874726.13
#Sta/Elev= 30
       0   9.123   7.238   8.405   23.13   8.647  23.226    9.85  25.058  11.185
  26.287  11.265  27.127  11.054  31.216   8.465  32.248   8.077  43.676   7.349
  44.962   6.964  44.995    6.21  48.615   5.714  54.663   5.707  58.758   6.348
   69.87    6.59   74.83   6.454  79.269   5.722  89.221   5.597  90.253   5.625
  91.078   6.063  91.116   6.961  91.755   7.359 117.778   8.248 121.776  10.882
  124.06  10.949 125.562  10.594  127.45   9.403 131.402   7.503 143.185   7.618
#Mann= 3 ,0,0
       0    .035       0  43.676    .035       0  91.755    .035       0
Levee=-1,26.28705,13.51342,-1,122.0154,13.51342,,
Bank Sta=43.676,91.755
XS Rating Curve= 0 ,0
Exp/Cntr=0.3,0.1

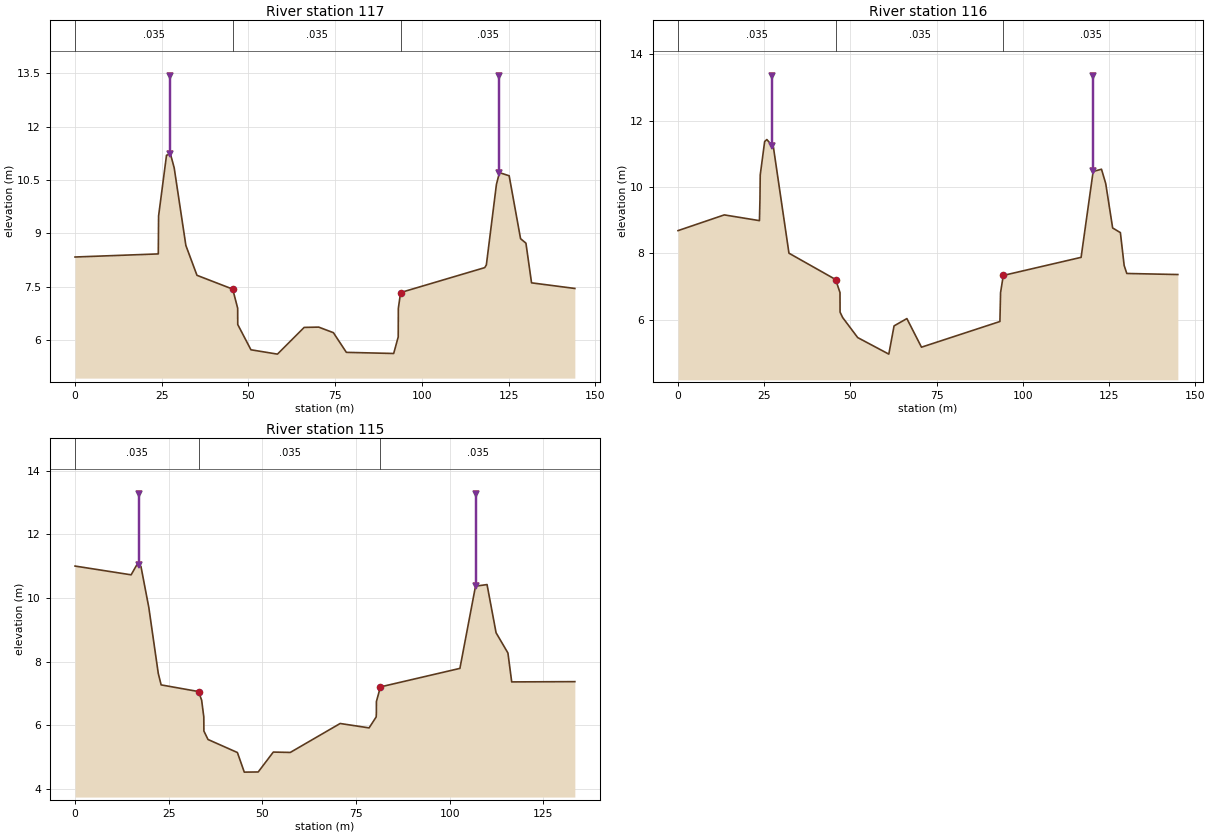
Type RM Length L Ch R = 1 ,117     ,20,20,20
XS GIS Cut Line= 6
      589648.449     4874690.472       589544.82     4874701.814
      589531.059     4874703.321      589525.725     4874703.904
      589517.639      4874704.79      589505.233     4874706.147
#Sta/Elev= 30
       0   8.333  23.998    8.42  24.083   9.486  26.371  11.197  27.516  11.229
  28.582  10.843   31.95   8.658  35.149   7.818  45.451   7.429   46.88   6.892
  46.901   6.434  50.707   5.722  58.347     5.6  66.048   6.352  70.246    6.36
  74.481   6.203   78.21    5.65  91.853   5.618  93.159   6.083  93.194   6.889
  93.849   7.333 118.091   8.034 118.566   8.111 121.462  10.373 122.338  10.708
 125.137  10.619 128.423   8.849 129.973   8.723 131.591   7.606 144.071   7.448
#Mann= 3 ,0,0
       0    .035       0  45.451    .035       0  93.849    .035       0
Levee=-1,27.51637,13.43176,-1,122.3384,13.43176,,
Bank Sta=45.451,93.849
XS Rating Curve= 0 ,0
Exp/Cntr=0.3,0.1

Type RM Length L Ch R = 1 ,116     ,20,20,20
XS GIS Cut Line= 6
      589646.273     4874670.591      589622.795      4874673.16
      589613.877     4874674.137      589613.603     4874674.166
      589613.274     4874674.203      589502.134     4874686.367
#Sta/Elev= 30
       0   8.686   13.42    9.16  23.618   8.987  23.766   9.619  23.844  10.361
  25.127   11.37   25.77   11.43  27.664  11.205  32.182   8.006  45.711   7.213
  46.984    6.82  47.009    6.23  47.763   6.067  52.118   5.464   61.15   4.965
  62.673   5.816  66.388   6.036  70.627   5.174  93.382   5.948  93.567   6.817
  94.361   7.336 116.933   7.881 120.425  10.468 122.849  10.536 124.078  10.103
 126.087   8.766 128.331   8.626 129.426   7.636 130.186   7.395     145   7.363
#Mann= 3 ,0,0
       0    .035       0  45.711    .035       0  94.361    .035       0
Levee=-1,27.27799,13.3501,-1,120.4249,13.3501,,
Bank Sta=45.711,94.361
XS Rating Curve= 0 ,0
Exp/Cntr=0.3,0.1

Type RM Length L Ch R = 1 ,115     ,20,20,20
XS GIS Cut Line= 6
      589630.561     4874647.854      589587.947     4874655.775
      589586.144     4874656.111      589552.203     4874662.419
      589550.417     4874662.752      589499.394     4874672.236
#Sta/Elev= 30
       0  11.002   14.97  10.727  16.569  11.056   17.59  10.994  19.695   9.704
  22.227   7.629  22.986   7.273  32.971   7.064  33.796   6.793  34.374   6.267
  34.395   5.826  35.498    5.56  43.344   5.151  45.178   4.536  48.897   4.541
   52.92   5.165  57.462   5.154  70.773   6.062  78.488   5.924  80.385   6.267
  80.437   6.396  80.445   6.751  81.517    7.21 102.735   7.791 106.902  10.371
  109.98  10.421  112.39   8.909 115.553   8.274 116.561   7.367 133.414   7.375
#Mann= 3 ,0,0
       0    .035       0  32.971    .035       0  81.517    .035       0
Levee=-1,17.15292,13.26844,-1,106.9025,13.26844,,
Bank Sta=32.971,81.517
XS Rating Curve= 0 ,0
Exp/Cntr=0.3,0.1