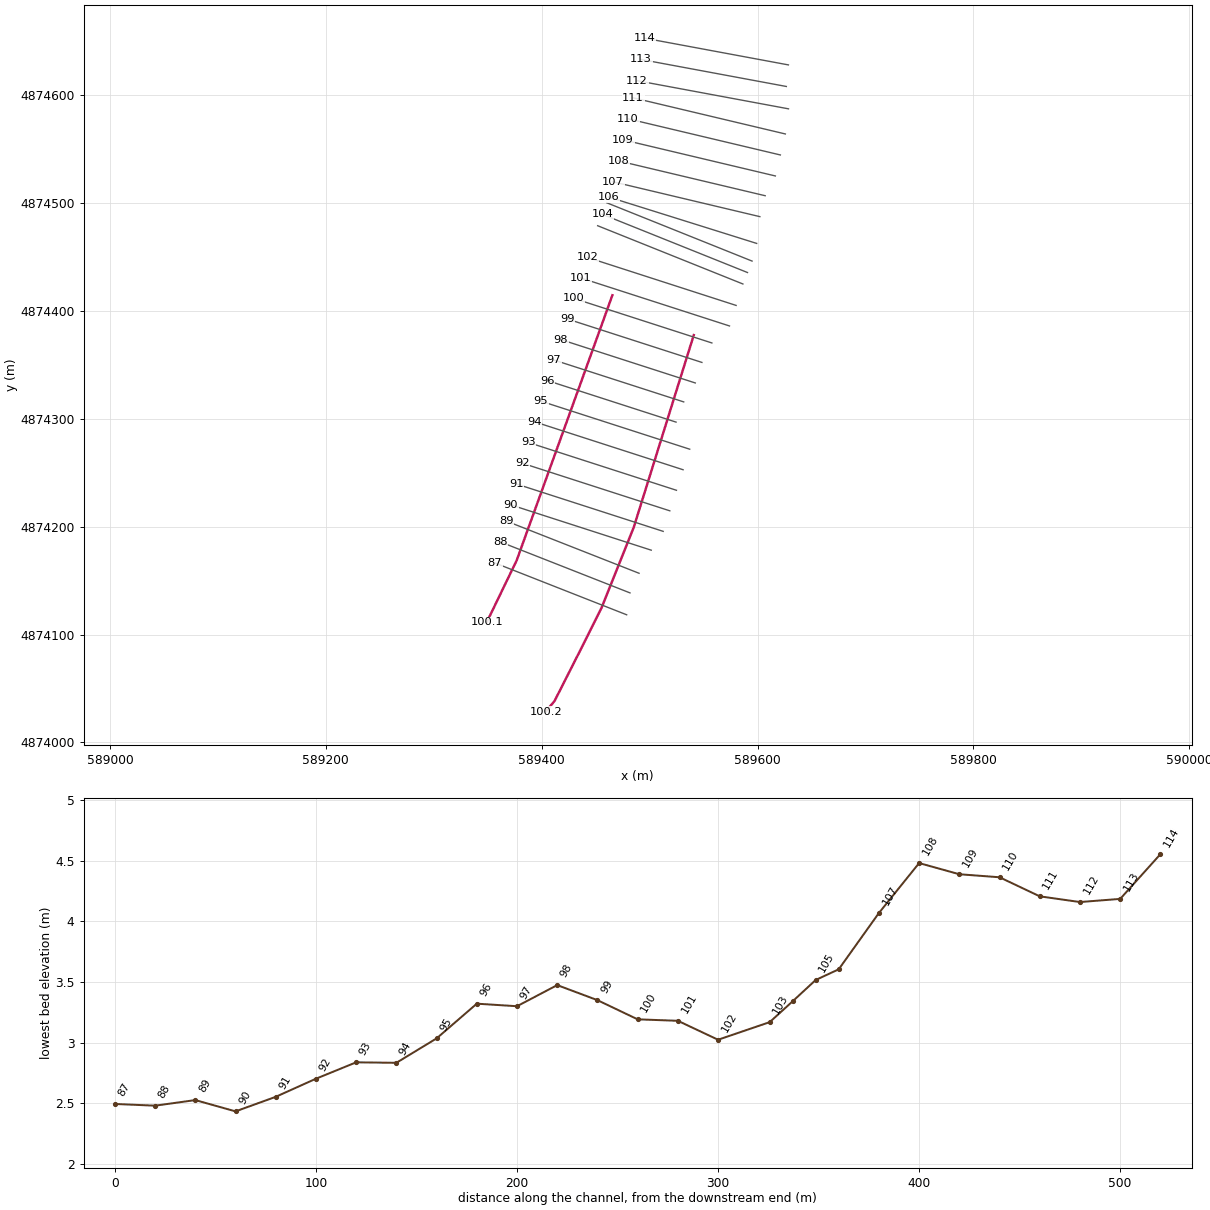
HEC-RAS study massa.prj: massa

--- massa.g05 (geometry) --- (continued)

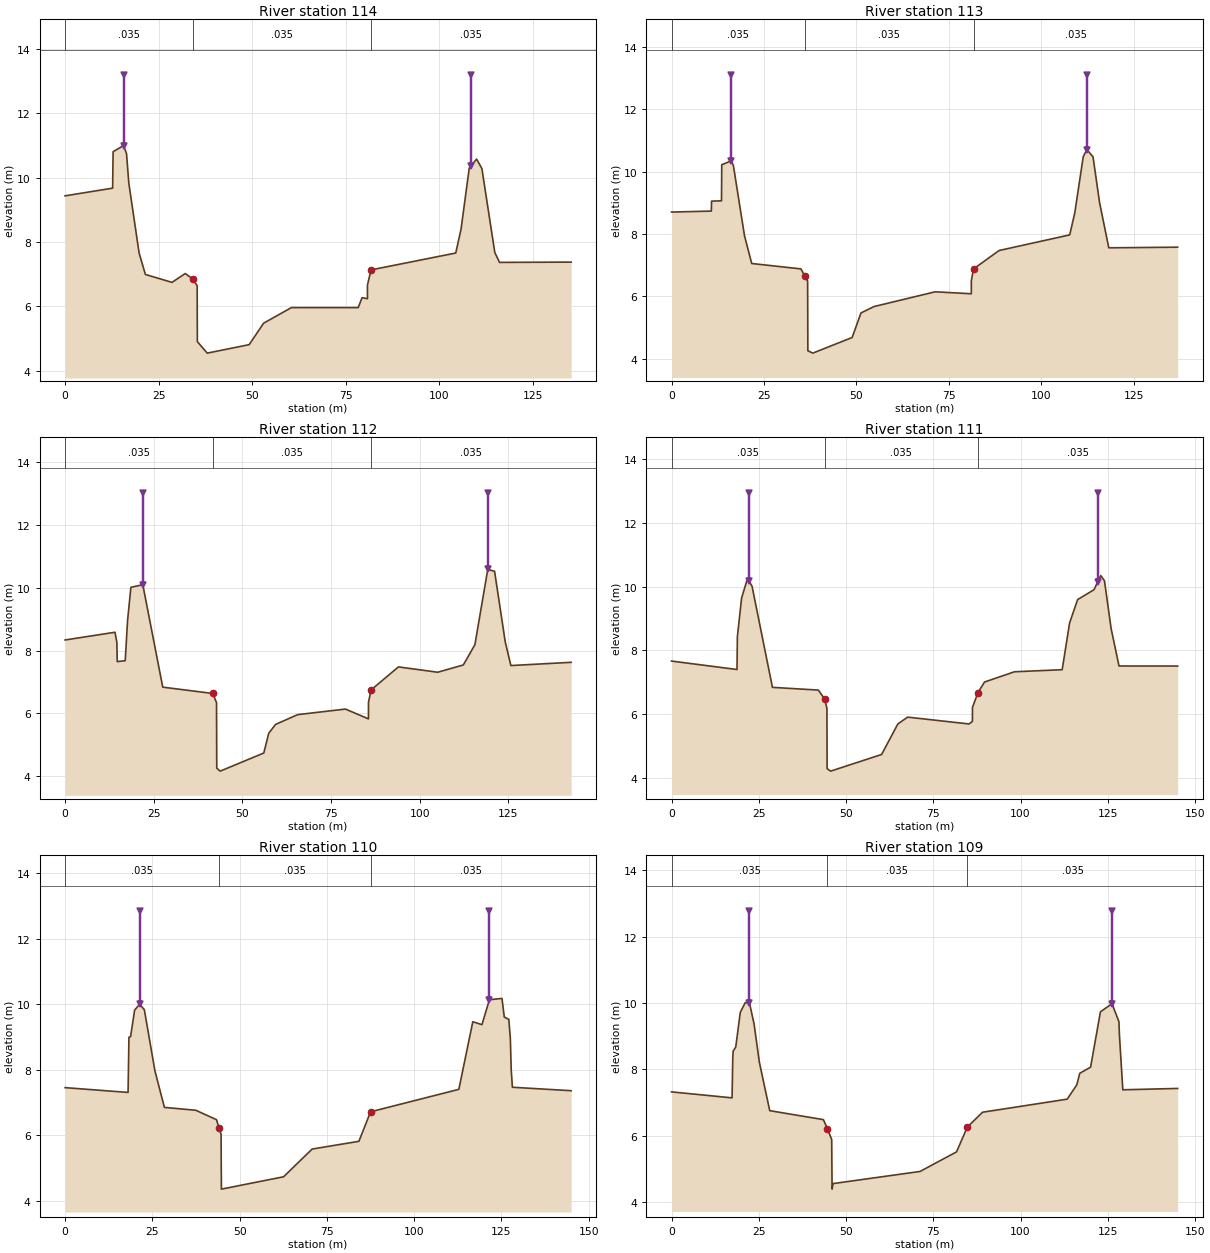
Type RM Length L Ch R = 1 ,114     ,20,20,20
XS GIS Cut Line= 6
       589628.63      4874627.87      589612.786     4874630.816
      589594.236     4874634.264      589593.898     4874634.326
      589591.304     4874634.809      589495.739     4874652.573
#Sta/Elev= 30
       0   9.432  12.698   9.671  12.823  10.802  15.616  10.993  16.409  10.742
   17.02   9.827  19.767   7.659  21.446   6.993  28.551   6.747    32.1   7.022
   34.07   6.857  35.277   6.642  35.327   4.908  37.966   4.552  49.167   4.815
  53.019    5.48  60.446   5.965  78.288   5.965  79.324   6.272  80.751   6.241
  80.759   6.661  81.716   7.134 104.345   7.658 105.764   8.403 107.955  10.297
 109.912  10.572 111.331  10.277 114.775   7.674  116.04   7.367 135.168   7.376
#Mann= 3 ,0,0
       0    .035       0   34.07    .035       0  81.716    .035       0
Levee=-1,15.61602,13.18678,-1,108.4649,13.18678,,
Bank Sta=34.07,81.716
XS Rating Curve= 0 ,0
Exp/Cntr=0.3,0.1

Type RM Length L Ch R = 1 ,113     ,20,20,20
XS GIS Cut Line= 6
      589626.699     4874607.887      589620.685     4874609.004
      589616.118     4874609.854      589605.375      4874611.85
      589605.235     4874611.877      589492.084      4874632.91
#Sta/Elev= 30
       0   8.706  10.762   8.737  10.818   9.056  13.512   9.066  13.579  10.223
  16.195  10.351   16.74  10.188  19.743   7.941  21.689   7.057  34.992   6.884
  36.153   6.641  36.813   6.492  36.876    4.26  38.221   4.184  48.857   4.685
  51.244   5.471  54.771   5.677  71.324    6.15  81.102   6.087  81.111   6.509
  81.705   6.884   88.62   7.473  107.72   7.974  109.09   8.678 111.386  10.481
 112.372  10.707 114.033  10.477 115.817       9 118.296    7.56 136.921    7.58
#Mann= 3 ,0,0
       0    .035       0  36.153    .035       0  81.705    .035       0
Levee=-1,16.19462,13.10512,-1,112.3724,13.10512,,
Bank Sta=36.153,81.705
XS Rating Curve= 0 ,0
Exp/Cntr=0.3,0.1

Type RM Length L Ch R = 1 ,112     ,20,20,20
XS GIS Cut Line= 6
      589628.706     4874587.171       589587.78     4874594.778
      589516.236     4874608.078      589505.142      4874610.14
      589504.799     4874610.203      589488.429     4874613.247
#Sta/Elev= 30
       0   8.336  14.072   8.582   14.59   8.261  14.706   7.648  16.951   7.675
  17.616   8.959  18.552  10.013  21.912  10.096  27.534   6.833  41.627   6.632
  42.697   6.341  42.757   4.251  43.731   4.158   56.02   4.735  57.414   5.362
  59.327   5.645  65.562   5.957  79.045   6.135  85.529   5.823   85.54   6.355
   86.29   6.747  93.982   7.478  105.04   7.308  112.28    7.54 115.543   8.186
 119.166  10.584  121.09  10.524 124.094   8.276 125.681   7.521  142.68   7.624
#Mann= 3 ,0,0
       0    .035       0  41.627    .035       0   86.29    .035       0
Levee=-1,21.91213,13.02347,-1,119.1659,13.02347,,
Bank Sta=41.627,86.29
XS Rating Curve= 0 ,0
Exp/Cntr=0.3,0.1

Type RM Length L Ch R = 1 ,111     ,20,20,20
XS GIS Cut Line= 6
      589625.785     4874563.881      589567.226     4874577.786
      589565.353      4874578.23      589559.979     4874579.507
      589550.309     4874581.802      589484.707      4874597.38
#Sta/Elev= 30
       0    7.66   18.75   7.395  18.856   8.421  20.069   9.641  21.752  10.247
  23.062   10.01  28.903   6.835  42.049   6.749  43.839   6.474  44.512   6.181
  44.569   4.282  45.597   4.205  60.187   4.728  64.843   5.686  67.636     5.9
  85.221   5.686  86.199   5.765  86.219   6.204  87.796    6.67  89.666   7.002
  98.256   7.324 111.922   7.389 114.049   8.857 116.347    9.59 121.048   9.901
 122.975  10.343 124.038  10.182 125.936   8.685 128.207   7.505 145.001   7.504
#Mann= 3 ,0,0
       0    .035       0  43.839    .035       0  87.796    .035       0
Levee=-1,22.17999,12.94181,-1,122.0569,12.94181,,
Bank Sta=43.839,87.796
XS Rating Curve= 0 ,0
Exp/Cntr=0.3,0.1

Type RM Length L Ch R = 1 ,110     ,20,20,20
XS GIS Cut Line= 6
      589621.164     4874544.422      589543.192     4874562.937
      589539.258      4874563.87      589537.653     4874564.252
      589521.212     4874568.155      589480.087     4874577.921
#Sta/Elev= 30
       0   7.461  18.042   7.315  18.293   8.999  18.766   9.018  19.921   9.829
  21.363  10.007  22.705   9.842  25.741   7.973  28.453   6.858  37.454    6.77
  43.386   6.483  44.069   6.239  44.699   6.031  44.742   5.054  44.791   4.362
    62.6   4.739  70.792   5.586  84.183   5.822  87.524   6.723  112.82   7.409
  116.82   9.474 119.443   9.384 121.578  10.146 125.179  10.185 125.842   9.614
 127.129   9.548 127.574   8.969 127.821   8.014 128.163   7.473     145   7.367
#Mann= 3 ,0,0
       0    .035       0  44.069    .035       0  87.524    .035       0
Levee=-1,21.36306,12.86015,-1,121.578,12.86015,,
Bank Sta=44.069,87.524
XS Rating Curve= 0 ,0
Exp/Cntr=0.3,0.1

Type RM Length L Ch R = 1 ,109     ,20,20,20
XS GIS Cut Line= 6
      589616.544     4874524.963      589534.103     4874544.538
      589503.566      4874551.79      589502.757     4874551.981
      589501.653     4874552.244      589475.466     4874558.462
#Sta/Elev= 30
       0   7.319  17.338   7.139  17.534   8.342  17.652   8.547  18.396   8.673
  19.691   9.716  21.105   10.01  22.326   9.999  23.642   9.367  25.163   8.211
  28.129   6.753  43.514   6.482  44.671   6.205  45.883   5.882  45.992   4.387
  46.282   4.554  71.206    4.92  81.659   5.511  84.733   6.256  89.119   6.706
 113.366     7.1 116.119   7.532 116.951   7.879 120.065   8.065 122.886   9.735
 126.204   9.977 128.182   9.436 128.319   9.042 129.296   7.382 145.001   7.423
#Mann= 3 ,0,0
       0    .035       0  44.671    .035       0  84.733    .035       0
Levee=-1,22.326,12.77849,-1,126.204,12.77849,,
Bank Sta=44.671,84.733
XS Rating Curve= 0 ,0
Exp/Cntr=0.3,0.1

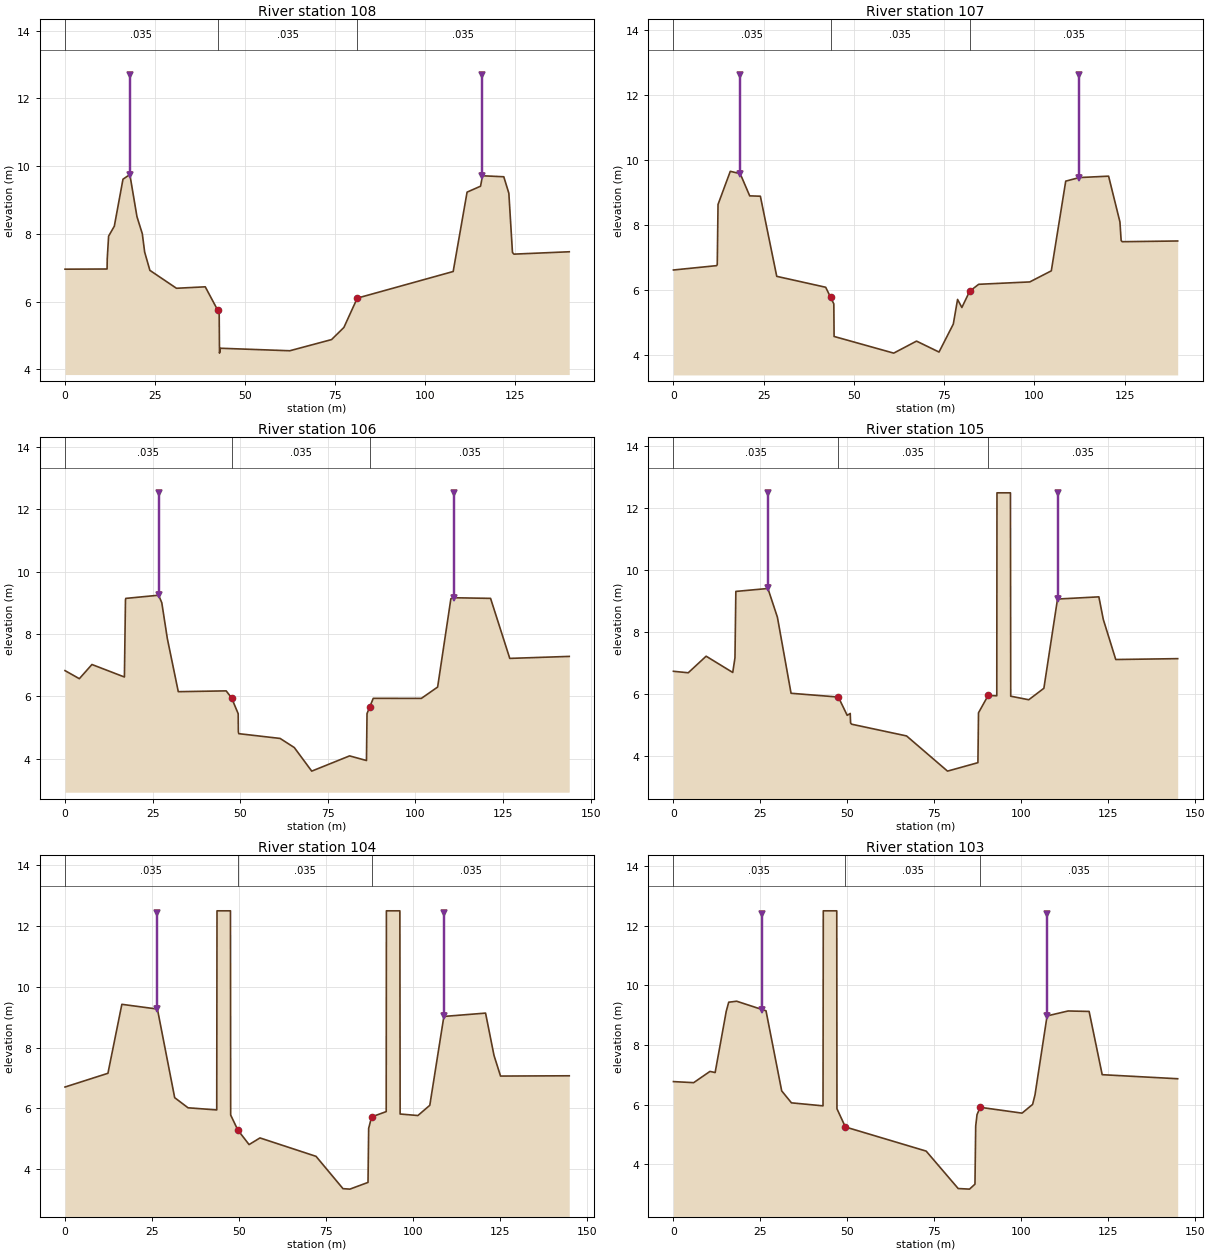
Type RM Length L Ch R = 1 ,108     ,20,20,20
XS GIS Cut Line= 6
      589607.108     4874506.647      589591.934     4874510.251
      589584.775      4874511.95      589575.059     4874514.258
      589525.305     4874526.071      589470.846     4874539.003
#Sta/Elev= 30
       0   6.958  11.684   6.963  11.733   7.267   12.11   7.933  13.695   8.227
  16.106   9.615  18.013   9.752  19.984    8.51  21.473   8.003  22.124   7.463
  23.577   6.923  30.956   6.394  38.955   6.437  42.423   5.746  42.815   5.733
  42.911   4.479   43.18   4.623  62.433   4.549  74.031   4.879  77.457   5.237
  81.175   6.103 107.811   6.889 111.671   9.233 115.413   9.408 115.954   9.716
 121.866   9.687 123.274     9.2 124.275   7.453 124.679   7.402 140.051   7.472
#Mann= 3 ,0,0
       0    .035       0  42.423    .035       0  81.175    .035       0
Levee=-1,18.01341,12.69683,-1,115.954,12.69683,,
Bank Sta=42.423,81.175
XS Rating Curve= 0 ,0
Exp/Cntr=0.3,0.1

Type RM Length L Ch R = 1 ,107     ,20,20,20
XS GIS Cut Line= 6
      589602.179     4874487.262      589561.127     4874497.009
      589558.819     4874497.558      589529.381     4874504.548
      589528.257     4874504.814      589466.225     4874519.544
#Sta/Elev= 30
       0   6.621  11.974   6.755  12.144   6.788  12.359   8.634  15.756   9.652
  18.505   9.579  21.134   8.898  24.091   8.887  28.628   6.426  42.193   6.091
  43.556    5.78  44.443   5.582  44.519    4.58  61.043   4.068  67.363   4.437
  73.595   4.101  77.552   4.959  78.736   5.717  79.927   5.469  82.091   5.968
  84.588   6.182  98.751   6.255 104.714   6.595 108.709    9.35 112.482    9.46
 120.587   9.503 123.729   8.097 124.063   7.528 124.357    7.49 139.734   7.512
#Mann= 3 ,0,0
       0    .035       0  43.556    .035       0  82.091    .035       0
Levee=-1,18.50459,12.61517,-1,112.4819,12.61517,,
Bank Sta=43.556,82.091
XS Rating Curve= 0 ,0
Exp/Cntr=0.3,0.1

Type RM Length L Ch R = 1 ,106     ,11.452,11.452,11.452
XS GIS Cut Line= 6
       589599.21     4874462.461       589582.74     4874467.623
      589582.651      4874467.65      589555.314     4874476.217
      589517.462     4874488.077      589461.883     4874505.494
#Sta/Elev= 30
       0   6.829   4.095    6.57    7.69   7.025  16.955   6.624   17.26   9.107
  17.353   9.146  26.722   9.248  27.625   9.006  29.205   7.858   32.33   6.153
  46.001   6.179  47.548   5.953  49.431   5.444  49.475   4.867  49.588   4.806
  61.392   4.653  65.436   4.361  70.414   3.604  81.224   4.093  86.037   3.944
  86.196    5.45   86.97   5.662  87.969   5.939 101.704   5.938 106.344   6.301
 110.128   9.135 110.881   9.167 121.455   9.147 126.934   7.221 143.912   7.285
#Mann= 3 ,0,0
       0    .035       0  47.548    .035       0   86.97    .035       0
Levee=-1,26.72182,12.53352,-1,110.8813,12.53352,,
Bank Sta=47.548,86.97
XS Rating Curve= 0 ,0
Exp/Cntr=0.3,0.1

Type RM Length L Ch R = 1 ,105     ,11.433,11.433,11.433
XS GIS Cut Line= 6
      589594.959     4874446.091      589516.074     4874477.735
      589510.971     4874479.781        589501.7     4874483.501
      589500.693     4874483.904      589460.382     4874500.074
#Sta/Elev= 30
       0   6.739   4.257   6.691   9.406   7.226  17.053   6.701  17.695   7.173
  17.948   9.317  27.167   9.412    29.9   8.484  33.822   6.029  47.427   5.907
  49.965   5.317  50.838   5.378  50.944    5.07  51.237   5.031  67.037   4.652
  78.814   3.516  87.556   3.789  87.725   5.399  90.493   5.958  92.981   5.948
  93.037    12.5  96.909    12.5  96.987   5.935 102.176    5.82 106.522    6.19
 110.446   9.071 122.337   9.142   123.6   8.417 127.189   7.119 145.001   7.147
#Mann= 3 ,0,0
       0    .035       0  47.427    .035       0  90.493    .035       0
Levee=-1,27.16724,12.48676,-1,110.4457,12.48676,,
Bank Sta=47.427,90.493
XS Rating Curve= 0 ,0
Exp/Cntr=0.3,0.1

Type RM Length L Ch R = 1 ,104     ,11.434,11.434,11.434
XS GIS Cut Line= 6
      589590.702      4874435.48       589509.66     4874467.988
      589498.382     4874472.513      589494.822      4874473.94
       589476.21     4874481.407      589456.125     4874489.463
#Sta/Elev= 30
       0   6.701  12.344   7.153   16.35   9.423  26.573   9.267  31.539   6.351
  35.375   6.018  43.632   5.947  43.709    12.5  47.581    12.5  47.637    5.78
  49.704   5.285  52.931   4.807  56.065   5.026  72.186    4.42  79.941   3.356
  81.927   3.341  87.132   3.562  87.319   5.341  88.174   5.718  92.362   5.892
  92.419    12.5  96.291    12.5  96.369   5.813 101.477   5.763 104.901     6.1
 108.945   9.024 120.933   9.134  123.36   7.742 125.239   7.062 145.001   7.071
#Mann= 3 ,0,0
       0    .035       0  49.704    .035       0  88.174    .035       0
Levee=-1,26.5732,12.44008,-1,108.9447,12.44008,,
Bank Sta=49.704,88.174
XS Rating Curve= 0 ,0
Exp/Cntr=0.3,0.1

Type RM Length L Ch R = 1 ,103     ,25.681,25.681,25.681
XS GIS Cut Line= 6
      589586.445     4874424.869      589561.738     4874434.779
      589505.777     4874457.227      589504.565     4874457.714
      589482.901     4874466.403      589451.869     4874478.852
#Sta/Elev= 30
       0   6.774   5.824   6.739  10.504   7.116  11.992   7.078  15.189   9.134
  15.897   9.436  18.184   9.469   26.62   9.148  31.129   6.464  33.931   6.062
  43.013   5.961   43.09    12.5  46.963    12.5  47.019   5.864  49.443   5.253
   72.67   4.444  81.879   3.189  85.137   3.169  86.707   3.335  86.916   5.283
    87.3   5.669  88.222   5.912 100.244   5.717 103.281    6.01 103.967   6.329
 107.445   8.977 113.486   9.142 119.531   9.127  123.29   7.006 144.999    6.87
#Mann= 3 ,0,0
       0    .035       0  49.443    .035       0  88.222    .035       0
Levee=-1,25.49041,12.39339,-1,107.4447,12.39339,,
Bank Sta=49.443,88.222
XS Rating Curve= 0 ,0
Exp/Cntr=0.3,0.1

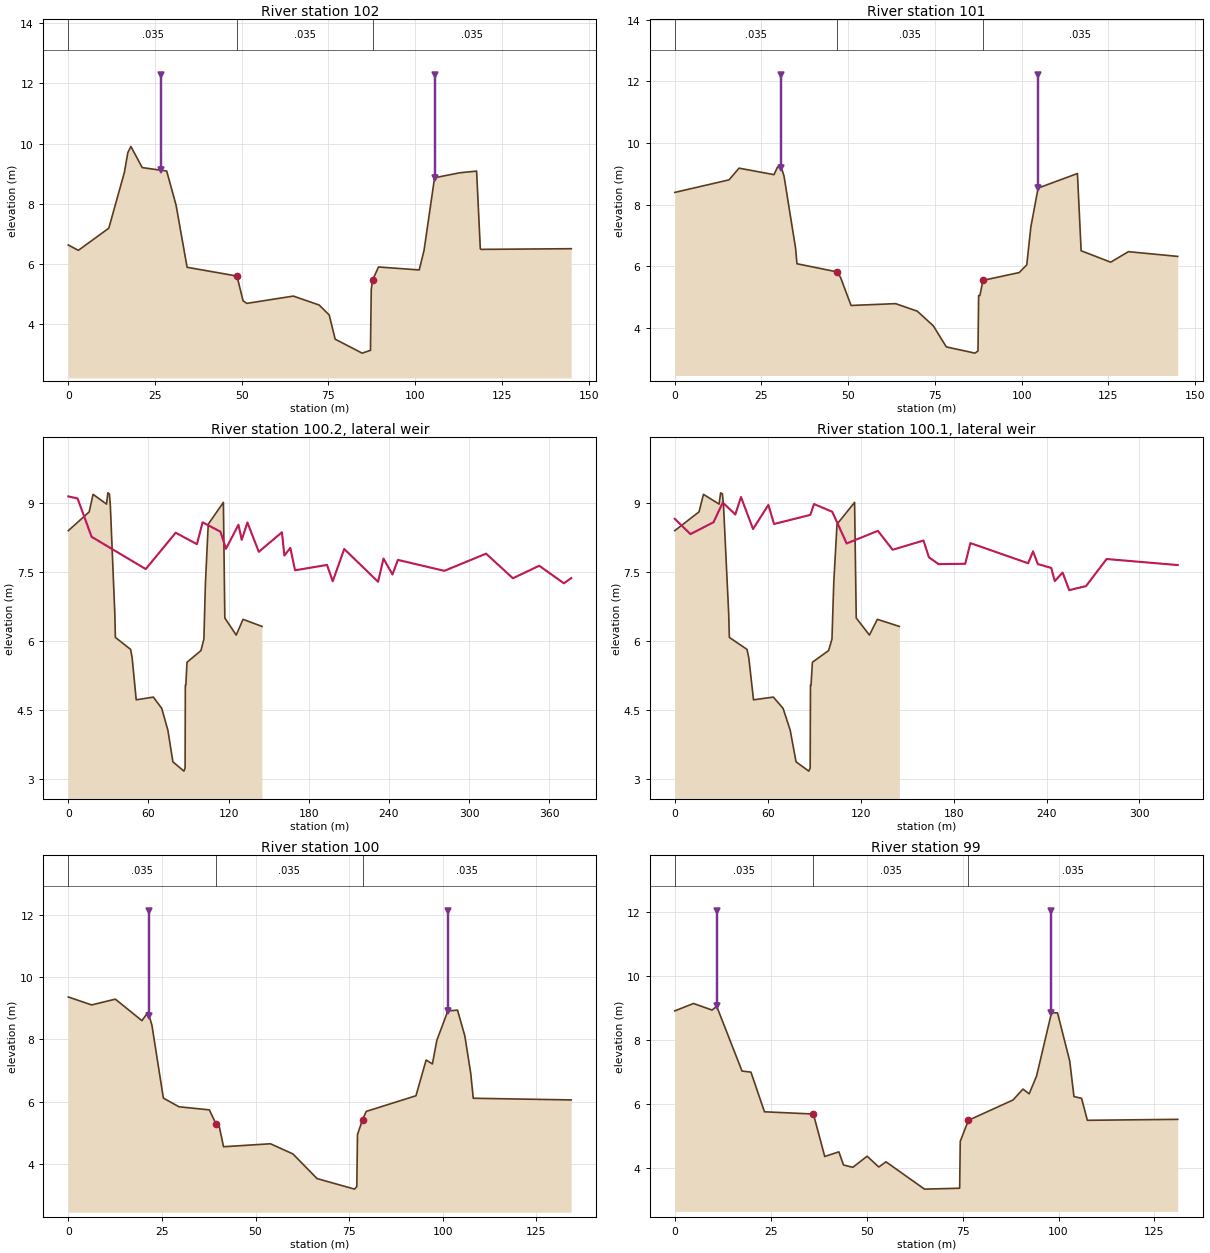
Type RM Length L Ch R = 1 ,102     ,20,20,20
XS GIS Cut Line= 6
      589580.172        4874405.      589532.219     4874420.477
      589518.435     4874424.927      589511.337     4874427.217
      589506.885     4874428.655      589442.182     4874449.539
#Sta/Elev= 30
       0   6.623     2.9   6.446  11.673   7.183  16.154   9.036  17.162     9.7
  18.043   9.904  21.309     9.2  28.362   9.086  31.074   7.947  34.246   5.882
   48.62    5.59  50.389   4.764  51.469    4.68  64.873   4.923  72.332   4.625
  75.218   4.293  76.935   3.488  84.704   3.024  87.111   3.116  87.335   5.147
  87.735   5.463  89.438   5.892 101.163   5.793 102.554   6.443  105.59   8.862
 112.922   9.029 117.709   9.084  118.78     6.5 118.986   6.478     145     6.5
#Mann= 3 ,0,0
       0    .035       0   48.62    .035       0  87.735    .035       0
Levee=-1,26.73955,12.28854,-1,105.5895,12.28854,,
Bank Sta=48.62,87.735
XS Rating Curve= 0 ,0
Exp/Cntr=0.3,0.1

Type RM Length L Ch R = 1 ,101     ,20,20,20
XS GIS Cut Line= 6
      589574.029     4874385.967        589556.4     4874391.656
      589552.428     4874392.939      589463.557     4874421.624
      589462.544      4874421.95      589436.039     4874430.506
#Sta/Elev= 30
       0   8.393  15.639     8.8  18.524    9.18  28.604   8.969  29.599   9.213
  30.763   9.187  31.479   8.929  34.811   6.595  35.227   6.079  46.628   5.819
  47.777    5.64  50.823   4.726   63.66   4.785  69.911   4.541  74.526   4.067
  78.288   3.382  86.531    3.18  87.413   3.249  87.602   5.046  87.961   5.046
  88.849    5.54  99.286   5.793 101.477   6.042 102.645   7.265 104.743   8.533
 116.084   9.006 117.148     6.5 125.676    6.13 130.778   6.471     145   6.317
#Mann= 3 ,0,0
       0    .035       0  46.628    .035       0  88.849    .035       0
Levee=-1,30.76309,12.20688,-1,104.7435,12.20688,,
Bank Sta=46.628,88.849
XS Rating Curve= 0 ,0
Exp/Cntr=0.3,0.1

Type RM Length L Ch R = 6 ,100.2   ,,,
Lateral Weir Pos= 0
Lateral Weir End=                ,                ,        ,south_01
Lateral Weir TW Multiple XS=0
Lateral Weir WD=1
Lateral Weir Coef=1.1
LW OverFlow Method 2D=0
LW OverFlow Use Velocity Into 2D=0
Lateral Weir WSCriteria=-1
Lateral Weir Flap Gates= 0
Lateral Weir Hagers EQN= 0 ,,,,,
Lateral Weir SS=0.05,0.05,
Lateral Weir Type= 0
Lateral Weir Connection Pos and Dist= 3 ,
Lateral Weir SE= 30
       0   9.135   6.942   9.091  17.418    8.26  57.946    7.56   80.38   8.348
  96.267     8.1 100.511   8.574 113.932   8.369 117.989   7.999 127.353   8.521
 129.797   8.194 134.063    8.57  142.57   7.934 159.893   8.358 161.731   7.854
 166.179   8.019 169.714   7.533 193.618    7.65 197.926   7.296 206.542   7.995
 231.861   7.284  235.92   7.788 242.631   7.443 246.691   7.759  281.45   7.522
  312.71   7.894 332.786   7.361 352.472   7.632 370.937   7.252 376.469   7.365
Lateral Weir Centerline= 6
589540.9262610144874377.48629334589485.410403892 4874199.6855077
589455.4018324754874124.66407915589436.6464753394874087.15336488
 589411.889403924874038.38943633 589403.637046784874028.63665062
LW Div RC= 0 ,False,,

Type RM Length L Ch R = 6 ,100.1   ,,,
Lateral Weir Pos= 3
Lateral Weir End=                ,                ,        ,north_01
Lateral Weir TW Multiple XS=0
Lateral Weir WD=1
Lateral Weir Coef=1.1
LW OverFlow Method 2D=0
LW OverFlow Use Velocity Into 2D=0
Lateral Weir WSCriteria=-1
Lateral Weir Flap Gates= 0
Lateral Weir Hagers EQN= 0 ,,,,,
Lateral Weir SS=0.05,0.05,
Lateral Weir Type= 0
Lateral Weir Connection Pos and Dist= 3 ,
Lateral Weir SE= 30
       0   8.649  10.121   8.318  25.025   8.576   30.97   9.002  39.086   8.744
  42.753   9.123   50.52   8.428  60.428   8.951  64.084   8.538   87.52   8.735
  89.885    8.97 101.669   8.802 110.956   8.115 131.126   8.389 140.642   7.979
 160.584   8.179 164.078   7.815 170.327   7.667 187.514   7.675 190.854   8.123
 228.136   7.686 231.282   7.944 234.385   7.669 243.065   7.584 245.322     7.3
 250.389   7.484 254.642   7.104  265.46    7.19 278.791   7.778 324.711   7.647
Lateral Weir Centerline= 3
589465.4828379574874414.38023428589376.8421379974874168.77162814
589349.1419192594874111.52450942
LW Div RC= 0 ,False,,

Type RM Length L Ch R = 1 ,100     ,20,20,20
XS GIS Cut Line= 6
      589557.706     4874370.219      589473.403      4874397.43
      589469.363     4874398.733      589466.776     4874399.569
      589454.799     4874403.434      589429.896     4874411.473
#Sta/Elev= 30
       0    9.36   6.229   9.105  12.561    9.29  19.652     8.6  21.285   8.871
  22.319    8.46   25.38   6.115   29.56   5.835  37.667   5.736  39.494    5.27
  40.225   5.249  41.454   4.553  53.983   4.648  59.979   4.322  66.429    3.53
  76.446   3.192  77.039   3.277  77.214   4.944  78.573   5.424  79.557   5.687
  92.831   6.189  95.549   7.337  97.214    7.21  98.418   7.972 101.349   8.911
 103.929   8.938 105.885   8.108 107.455   6.912 108.135   6.109 134.303   6.055
#Mann= 3 ,0,0
       0    .035       0  39.494    .035       0  78.573    .035       0
Levee=-1,21.59396,12.12522,-1,101.3487,12.12522,,
Bank Sta=39.494,78.573
XS Rating Curve= 0 ,0
Exp/Cntr=0.3,0.1

Type RM Length L Ch R = 1 ,99      ,20,20,20
XS GIS Cut Line= 6
      589548.471     4874352.184      589477.381     4874375.129
      589456.704     4874381.804      589446.161     4874385.206
      589440.879     4874386.912      589423.752     4874392.439
#Sta/Elev= 30
       0   8.918   4.888   9.149   9.721   8.944   10.92   9.062  17.521   7.039
  19.843   7.005  23.377   5.766  36.118   5.696  39.076    4.37   42.76   4.515
  43.966   4.104  46.395   4.031  50.121   4.378  53.161   4.041  55.035   4.203
  65.075    3.35  74.232   3.378  74.386   4.843  76.508     5.5  88.129   6.134
   90.73   6.475  92.339   6.327  94.274   6.883  98.159   8.859   99.73   8.855
 102.908   7.355 104.018   6.242 105.997   6.187 107.507     5.5 131.055    5.53
#Mann= 3 ,0,0
       0    .035       0  36.118    .035       0  76.508    .035       0
Levee=-1,10.91985,12.04357,-1,98.15939,12.04357,,
Bank Sta=36.118,76.508
XS Rating Curve= 0 ,0
Exp/Cntr=0.3,0.1

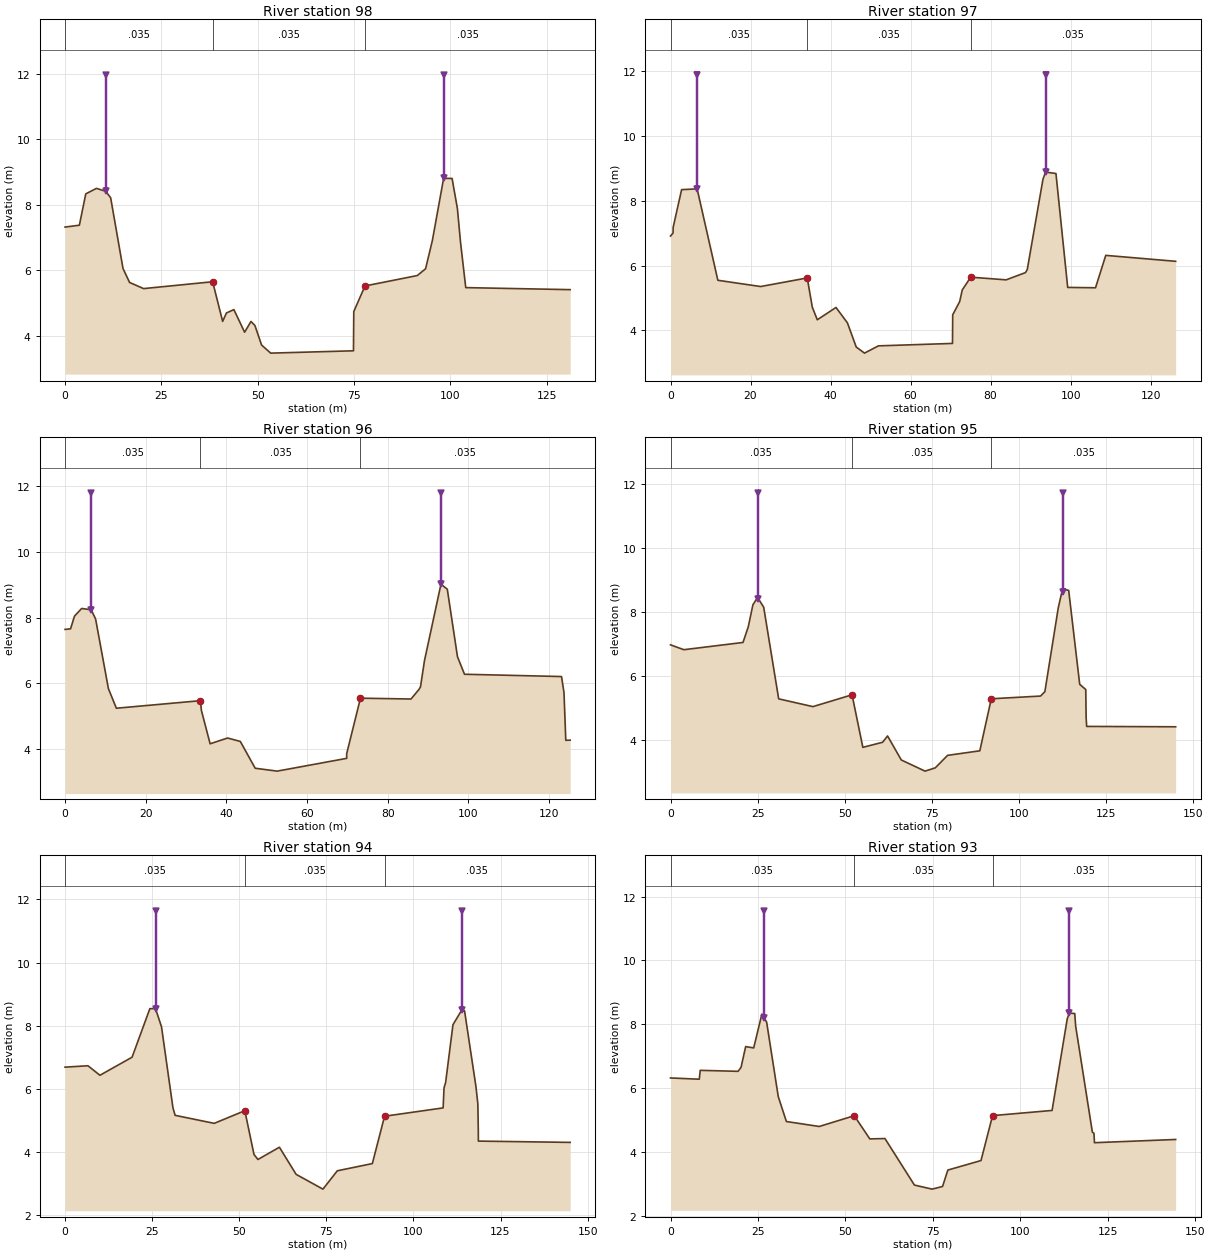
Type RM Length L Ch R = 1 ,98      ,20,20,20
XS GIS Cut Line= 6
      589542.334     4874333.149      589530.379     4874337.008
      589528.021     4874337.768      589498.852     4874347.184
      589493.805     4874348.812      589417.609     4874373.406
#Sta/Elev= 30
       0   7.319   3.715   7.375   5.378   8.331    8.15   8.499  10.557   8.409
  11.833   8.213   15.04   6.055  16.748   5.629  20.379   5.442  38.291   5.651
  40.893   4.442  41.873   4.699  43.808   4.801  46.591   4.112  48.245    4.44
  49.271   4.315  50.994   3.721  53.355   3.474  74.833   3.545  74.912   4.741
  77.828   5.523  91.391    5.84  93.544   6.047  95.302   6.908  98.225   8.806
 100.421   8.801 101.799   7.883 102.614    6.85 103.968   5.472 131.061    5.41
#Mann= 3 ,0,0
       0    .035       0  38.291    .035       0  77.828    .035       0
Levee=-1,10.55743,11.96191,-1,98.22546,11.96191,,
Bank Sta=38.291,77.828
XS Rating Curve= 0 ,0
Exp/Cntr=0.3,0.1

Type RM Length L Ch R = 1 ,97      ,20,20,20
XS GIS Cut Line= 6
      589531.614     4874315.593      589528.873     4874316.477
      589525.022     4874317.721       589520.35     4874319.228
      589495.524     4874327.242      589411.466     4874354.373
#Sta/Elev= 30
       0   6.909    .639   7.004    .664   7.179   2.775    8.34   6.656   8.364
  11.836   5.546  22.533   5.353  34.175   5.618  35.444   4.715  36.684   4.328
  41.359   4.708  44.214   4.234  46.418   3.489  48.482     3.3   51.97   3.524
  70.477   3.599  70.535   4.482  72.282   4.891  72.915   5.247  75.037   5.642
  83.881   5.559  88.727   5.783  89.169   5.877  93.094   8.662  93.739   8.883
  96.338   8.837  99.273   5.326 106.226   5.315 108.785   6.314 126.252   6.131
#Mann= 3 ,0,0
       0    .035       0  34.175    .035       0  75.037    .035       0
Levee=-1,6.655689,11.88025,-1,93.73866,11.88025,,
Bank Sta=34.175,75.037
XS Rating Curve= 0 ,0
Exp/Cntr=0.3,0.1

Type RM Length L Ch R = 1 ,96      ,20,20,20
XS GIS Cut Line= 6
      589524.519     4874296.867      589465.153     4874316.029
      589452.847        4874320.      589436.265     4874325.353
      589432.049     4874326.713      589405.322      4874335.34
#Sta/Elev= 30
       0   7.638   1.369   7.656   2.339   8.042   4.116   8.276   6.494   8.236
   7.585   7.951  10.753   5.833  12.729   5.237  33.577   5.467   33.81    5.17
  35.972   4.154  40.315    4.33  43.461   4.225  47.146   3.409  52.606   3.321
  69.832    3.71  69.841   3.857  73.251   5.543  85.787   5.518   87.78   5.813
  88.136   5.889  89.129    6.69  93.213   9.016   94.78   8.863  97.308   6.805
  99.047   6.272 123.106   6.202 123.717   5.712 124.162   4.261 125.252   4.264
#Mann= 3 ,0,0
       0    .035       0  33.577    .035       0  73.251    .035       0
Levee=-1,6.494031,11.79859,-1,93.21333,11.79859,,
Bank Sta=33.577,73.251
XS Rating Curve= 0 ,0
Exp/Cntr=0.3,0.1

Type RM Length L Ch R = 1 ,95      ,20,20,20
XS GIS Cut Line= 6
      589537.169     4874271.768      589513.159     4874279.518
      589509.435     4874280.719       589508.84     4874280.912
      589477.874     4874290.906      589399.179     4874316.307
#Sta/Elev= 30
       0   6.975   3.834   6.823  20.808   7.049  22.317   7.535  23.655   8.225
  24.996   8.451  26.752   8.148   31.05    5.29  40.872   5.047  52.112   5.416
  55.213   3.777  60.877   3.935  62.307   4.132  66.247   3.383  73.058   3.035
  75.999   3.137  79.541   3.527  88.787   3.669  92.081   5.292 106.227   5.377
 107.465   5.515 111.306   8.129 112.229   8.571 113.153   8.704 114.302   8.672
 117.457   5.744 119.199    5.58 119.304   4.711 119.459    4.43     145   4.418
#Mann= 3 ,0,0
       0    .035       0  52.112    .035       0  92.081    .035       0
Levee=-1,25.2298,11.71693,-1,112.549,11.71693,,
Bank Sta=52.112,92.081
XS Rating Curve= 0 ,0
Exp/Cntr=0.3,0.1

Type RM Length L Ch R = 1 ,94      ,20,20,20
XS GIS Cut Line= 6
      589531.026     4874252.735      589431.646     4874284.812
      589428.653     4874285.777       589423.78     4874287.351
      589418.132     4874289.173      589393.036     4874297.274
#Sta/Elev= 30
       0   6.691   6.575   6.736  10.015   6.435  19.239   7.006  24.346   8.541
  25.971   8.542  27.698   7.964  30.965   5.412  31.593   5.168  42.821   4.914
  51.606   5.314   54.24   3.929  55.373   3.772  61.533   4.159  66.331   3.301
  74.025   2.834  78.158   3.414   88.21   3.642  91.715   5.139 108.525   5.403
 108.784   6.033 109.247   6.207 111.351   8.034 113.824   8.488 114.682   8.472
 117.949   6.076 118.493   5.532 118.629   4.666 118.646   4.353     145   4.312
#Mann= 3 ,0,0
       0    .035       0  51.606    .035       0  91.715    .035       0
Levee=-1,25.97139,11.63527,-1,113.8238,11.63527,,
Bank Sta=51.606,91.715
XS Rating Curve= 0 ,0
Exp/Cntr=0.3,0.1

Type RM Length L Ch R = 1 ,93      ,20,20,20
XS GIS Cut Line= 6
      589524.882     4874233.702      589514.541     4874237.039
        589498.4     4874242.249      589495.187     4874243.287
      589476.914     4874249.184      589387.424     4874278.069
#Sta/Elev= 30
       0    6.32   8.224    6.28   8.505   6.558  19.322   6.527  20.166    6.65
  21.491   7.302  23.786    7.26  26.129   8.321  27.491   8.067  30.814   5.735
  33.139   4.955   42.53     4.8  52.546   5.137   56.99   4.411  61.323   4.422
  69.746   2.965  74.813   2.838  77.787   2.921   79.31   3.435  88.784   3.733
  92.089    5.14 109.108   5.302 113.445   8.172 114.026   8.349  115.59   8.338
 115.855    7.94 120.631   4.622 121.085   4.588 121.229   4.292 144.441   4.393
#Mann= 3 ,0,0
       0    .035       0  52.546    .035       0  92.089    .035       0
Levee=-1,26.7933,11.55362,-1,114.0256,11.55362,,
Bank Sta=52.546,92.089
XS Rating Curve= 0 ,0
Exp/Cntr=0.3,0.1

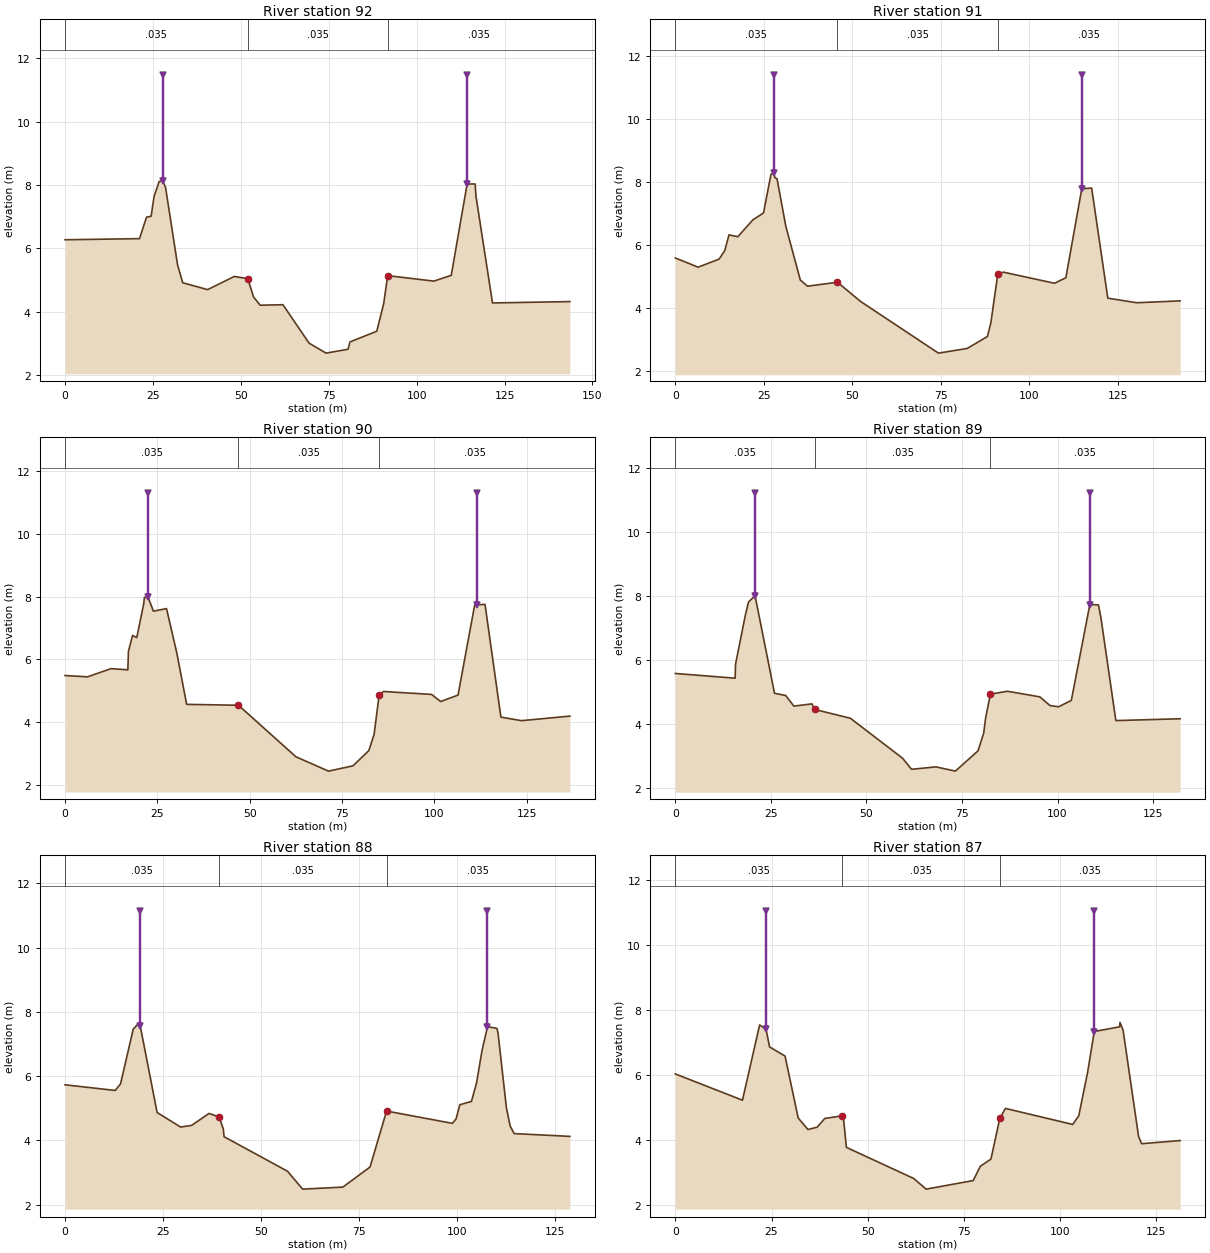
Type RM Length L Ch R = 1 ,92      ,20,20,20
XS GIS Cut Line= 6
      589518.739     4874214.668      589492.284     4874223.208
      589479.832     4874227.226      589407.527     4874250.564
      589403.047     4874252.011      589382.107     4874258.769
#Sta/Elev= 30
       0   6.275   21.17    6.31  23.185   6.987  24.483   7.016  25.318   7.637
  26.768   8.112  27.799   8.128  28.596   7.921  32.001   5.486  33.469    4.92
  40.558   4.704  48.145   5.119  51.984   5.048  53.615    4.47  55.515   4.213
  61.971   4.228  69.405   3.018  74.245   2.703   80.49   2.825  81.032   3.056
  88.662   3.393  90.623   4.262  91.767   5.145 104.917   4.972 109.843   5.155
 114.353   8.031 116.636   8.033 116.862   7.653  121.57   4.284 143.573   4.327
#Mann= 3 ,0,0
       0    .035       0  51.984    .035       0  91.767    .035       0
Levee=-1,27.79926,11.47196,-1,114.3525,11.47196,,
Bank Sta=51.984,91.767
XS Rating Curve= 0 ,0
Exp/Cntr=0.3,0.1

Type RM Length L Ch R = 1 ,91      ,20,20,20
XS GIS Cut Line= 6
      589512.596     4874195.635      589424.372     4874224.111
      589410.024     4874228.743      589400.599     4874231.784
      589396.844     4874232.997      589376.789      4874239.47
#Sta/Elev= 30
       0   5.575   6.436   5.283  12.373   5.539  13.959   5.806  15.174   6.309
  17.669    6.25  21.948   6.789  24.927   7.005  27.032    8.23  27.796   8.287
  28.161    8.12  28.757   8.092   31.22   6.585  35.324   4.878   37.34   4.679
  45.825   4.805  52.366   4.195  74.379   2.554  82.492   2.702  88.216   3.081
  89.193   3.518   91.15   5.063  92.706   5.126 107.179   4.772 110.398   4.948
 114.895   7.773 117.686   7.794 122.251   4.299 130.428   4.154 142.706   4.213
#Mann= 3 ,0,0
       0    .035       0  45.825    .035       0   91.15    .035       0
Levee=-1,27.79579,11.3903,-1,114.8946,11.3903,,
Bank Sta=45.825,91.15
XS Rating Curve= 0 ,0
Exp/Cntr=0.3,0.1

Type RM Length L Ch R = 1 ,90      ,20,20,20
XS GIS Cut Line= 6
      589501.526     4874178.192      589495.735     4874180.062
      589485.192     4874183.464      589481.239     4874184.741
      589474.522     4874186.908      589371.472      4874220.17
#Sta/Elev= 30
       0   5.482   6.085   5.441   12.48   5.703  17.005   5.664  17.164   6.254
  18.281   6.761  19.422   6.692  21.318    7.78  21.479   7.975  22.515   7.972
   23.93   7.534  27.472   7.617  30.272   6.194  32.924   4.563   46.95   4.535
  62.487   2.893  71.316   2.434  77.957   2.603  82.241   3.089  83.658   3.602
  85.025    4.85  86.176   4.974  99.226    4.88  101.68   4.654 106.389   4.859
 110.884   7.726  113.69   7.754 117.992   4.156 123.566   4.043 136.661   4.189
#Mann= 3 ,0,0
       0    .035       0   46.95    .035       0  85.025    .035       0
Levee=-1,22.51549,11.30864,-1,111.4501,11.30864,,
Bank Sta=46.95,85.025
XS Rating Curve= 0 ,0
Exp/Cntr=0.3,0.1

Type RM Length L Ch R = 1 ,89      ,20,20,20
XS GIS Cut Line= 6
      589490.244     4874156.793      589413.402     4874187.017
      589411.958     4874187.584      589387.233     4874197.309
      589387.182      4874197.33      589367.331     4874205.137
#Sta/Elev= 30
       0    5.58  15.649   5.432  15.746   5.867  18.327   7.408  19.147   7.812
  20.853   8.014   25.95    4.96  28.877   4.891   31.02   4.559  35.727    4.63
   36.47   4.455  45.787    4.18  59.438   2.932  61.798   2.584  68.191    2.66
  73.268   2.527  79.194   3.162  80.682   3.717  81.157   4.171  82.426   4.933
  86.885   5.024   95.37   4.848   98.02   4.577 100.255   4.538 103.603   4.737
 108.443   7.734 110.692   7.723 111.336   7.331 115.254   4.107 132.079   4.164
#Mann= 3 ,0,0
       0    .035       0   36.47    .035       0  82.426    .035       0
Levee=-1,20.85319,11.22698,-1,108.4435,11.22698,,
Bank Sta=36.47,82.426
XS Rating Curve= 0 ,0
Exp/Cntr=0.3,0.1

Type RM Length L Ch R = 1 ,88      ,20,20,20
XS GIS Cut Line= 6
      589481.838     4874138.608      589444.261     4874153.388
      589440.404     4874154.904      589390.021     4874174.722
      589388.999     4874175.123      589361.988     4874185.747
#Sta/Elev= 30
       0   5.729  12.802   5.553  14.159   5.758  17.401   7.463  19.013   7.672
  23.483   4.868  29.477   4.414  32.289   4.465  36.722   4.837  39.326   4.728
  40.379   4.351  40.575   4.113  56.755   3.038  60.616   2.481  70.867   2.544
   77.81   3.169  82.022   4.912  98.801   4.529  99.762   4.667 100.711   5.108
 103.679   5.212 104.973   5.782 106.364   6.784 107.768   7.539 110.172   7.486
  110.46   7.341 112.597   5.016 113.561   4.444 114.576    4.21 128.787   4.123
#Mann= 3 ,0,0
       0    .035       0  39.326    .035       0  82.022    .035       0
Levee=-1,19.19157,11.14532,-1,107.7677,11.14532,,
Bank Sta=39.326,82.022
XS Rating Curve= 0 ,0
Exp/Cntr=0.3,0.1

Type RM Length L Ch R = 1 ,87      ,20,20,20
XS GIS Cut Line= 6
      589478.739     4874118.335      589402.414     4874148.355
      589389.285      4874153.52      589373.453     4874159.746
      589371.282     4874160.601      589356.653     4874166.354
#Sta/Elev= 30
       0   6.042  17.446   5.233  21.903    7.55  23.574   7.416  24.495   6.873
  28.515   6.592   31.93   4.684  34.479    4.33  36.841   4.402  38.854   4.672
  43.411   4.751  43.714    4.65   44.45   3.781  61.927   2.824  65.179   2.495
  77.414   2.759  79.242   3.198  82.016    3.42  84.315   4.672  85.785    4.98
 103.274   4.486 104.835   4.752 107.144   6.096 108.864   7.348  115.47   7.493
  115.54   7.627  116.35   7.393 120.378   4.119 121.174   3.894  131.19    3.99
#Mann= 3 ,0,0
       0    .035       0  43.411    .035       0  84.315    .035       0
Levee=-1,23.57404,11.06367,-1,108.8637,11.06367,,
Bank Sta=43.411,84.315
XS Rating Curve= 0 ,0
Exp/Cntr=0.3,0.1