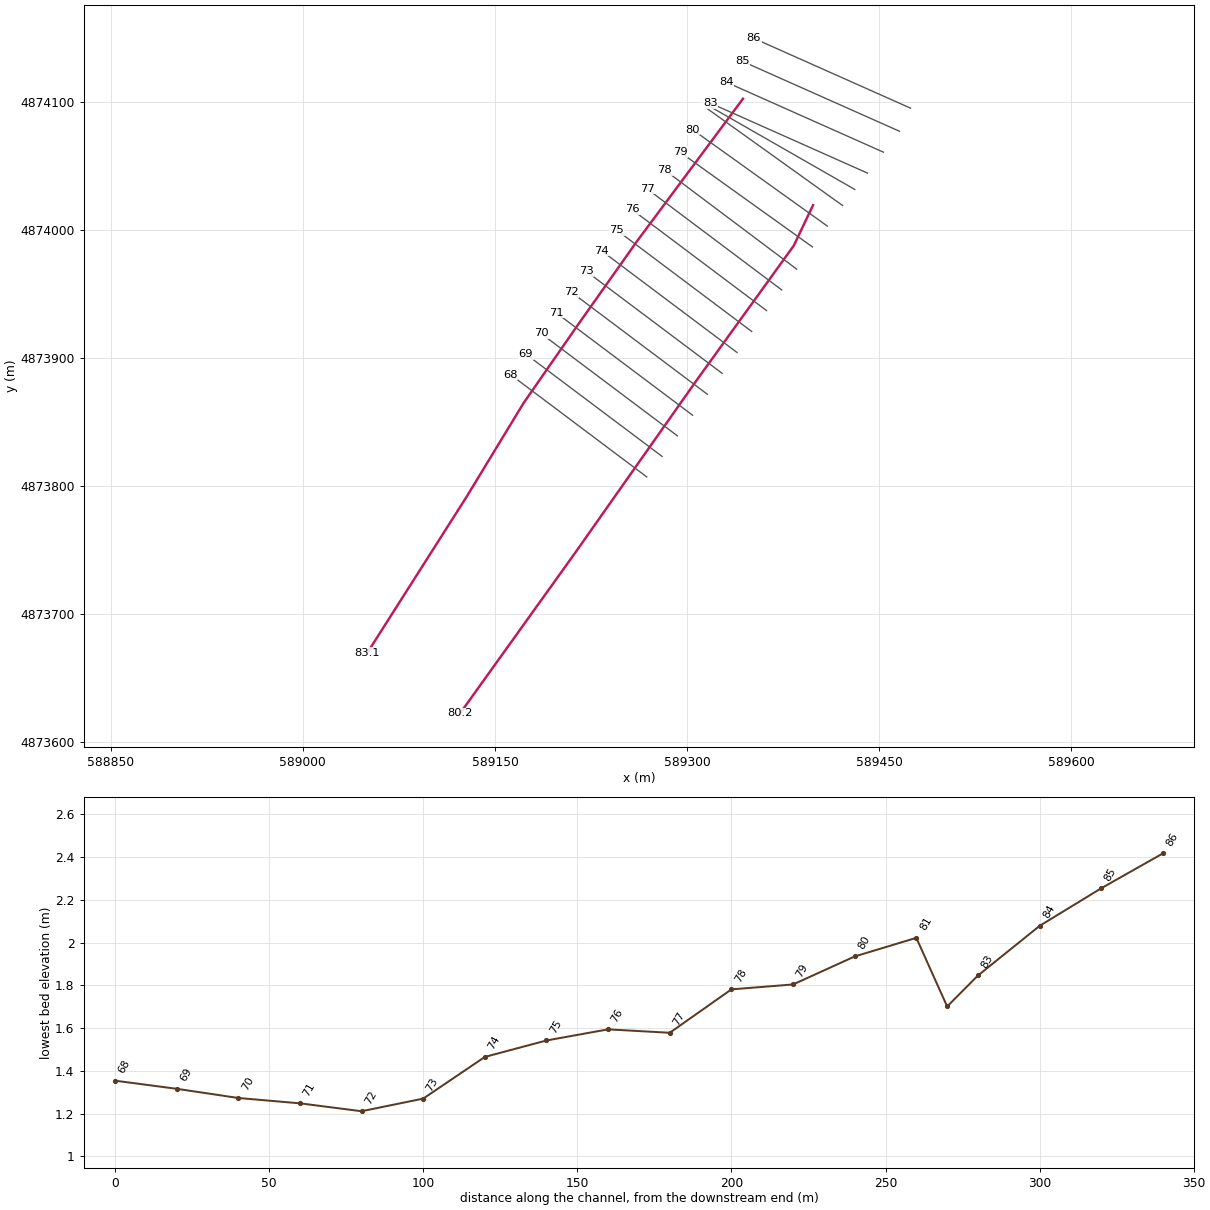
HEC-RAS study massa.prj: massa

--- massa.g05 (geometry) --- (continued)

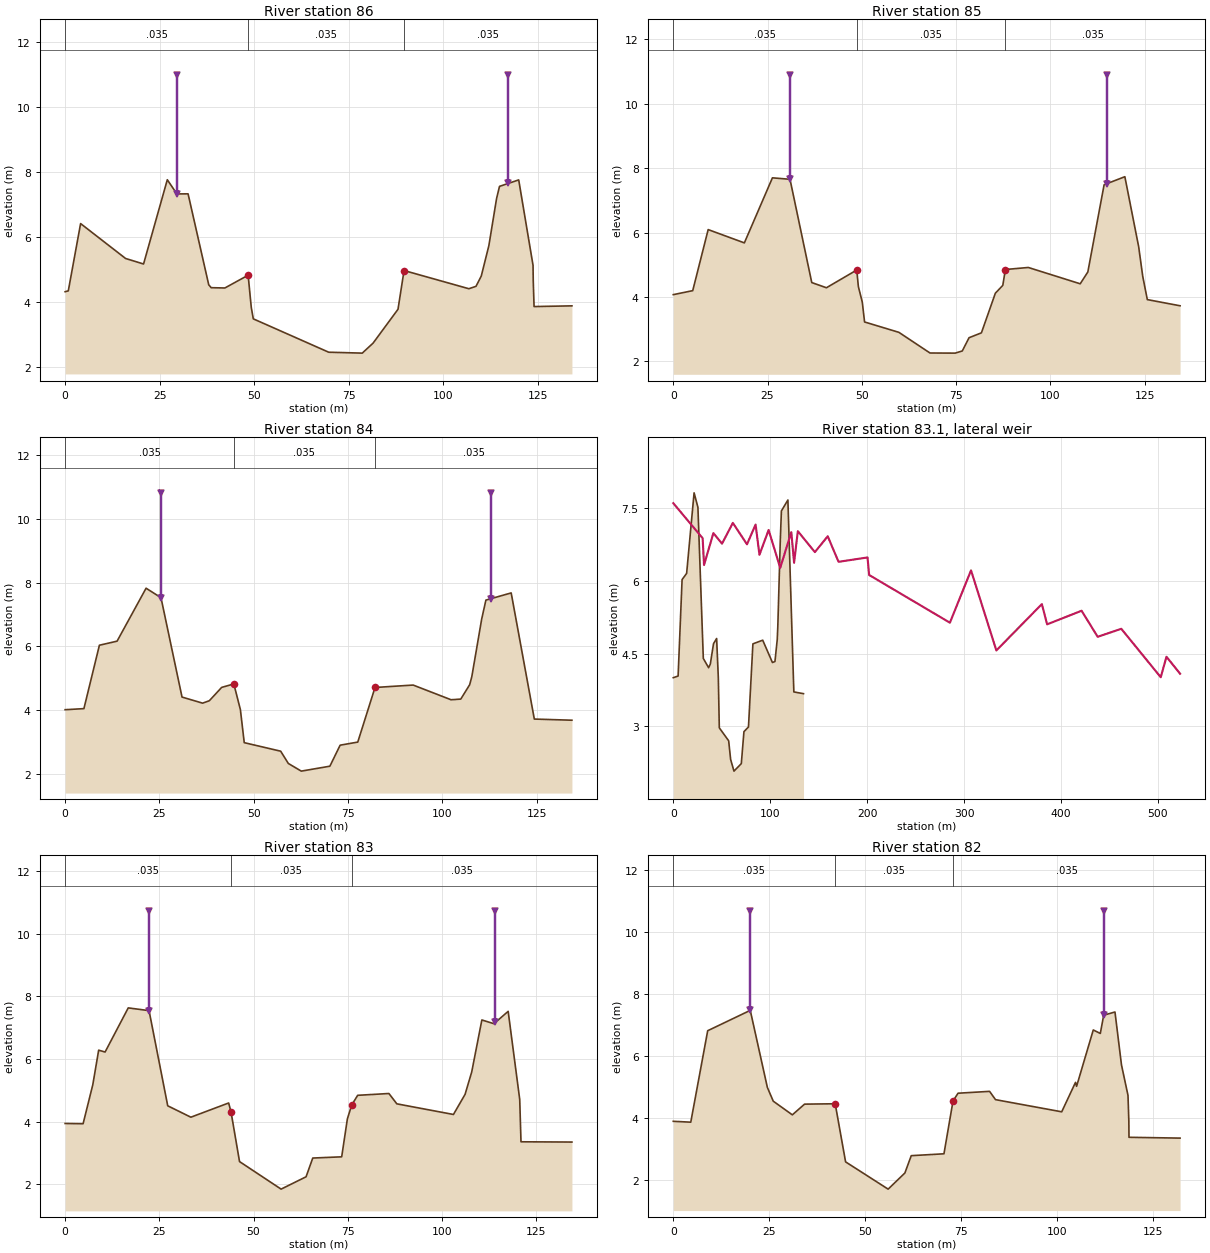
Type RM Length L Ch R = 1 ,86      ,20,20,20
XS GIS Cut Line= 6
       589474.43     4874095.214      589410.792     4874123.559
      589392.603     4874131.662      589391.723     4874132.053
      589372.121     4874140.785      589352.075     4874149.713
#Sta/Elev= 30
       0   4.307    .838   4.333    4.09   6.404  15.978    5.33  20.728    5.16
  27.005   7.753  29.545   7.317  32.496   7.319  37.955    4.52  38.601   4.431
  42.221   4.422  48.372   4.815  49.194   3.827  49.733   3.472  69.665   2.445
  78.531   2.417  81.387   2.724  87.979   3.767  89.577   4.959 106.707   4.399
 108.594   4.473 109.993   4.791 111.999   5.729 114.026   7.173 114.807   7.549
 119.881   7.748 123.669   5.118 123.721   4.648  123.94    3.85 133.944   3.872
#Mann= 3 ,0,0
       0    .035       0  48.372    .035       0  89.577    .035       0
Levee=-1,29.54506,10.98201,-1,117.1783,10.98201,,
Bank Sta=48.372,89.577
XS Rating Curve= 0 ,0
Exp/Cntr=0.3,0.1

Type RM Length L Ch R = 1 ,85      ,20,20,20
XS GIS Cut Line= 6
      589465.817     4874077.156      589420.973      4874097.13
      589420.026     4874097.553      589395.797     4874108.344
      589379.801      4874115.47      589343.029     4874131.848
#Sta/Elev= 30
       0   4.071   5.157   4.195   9.254   6.092  18.854   5.679  26.296     7.7
   30.96   7.655  36.729   4.446  40.619   4.285  48.662   4.836  49.091   4.321
  50.128    3.84  50.737   3.222  59.835     2.9  68.089   2.258  74.777   2.254
  76.652   2.321   78.45   2.733  81.726   2.884  85.427   4.116  87.399   4.359
  88.081   4.852  94.163   4.915 107.931   4.408 109.956   4.776 114.269   7.485
 119.773   7.735 123.439   5.558 124.513   4.642  125.73   3.917 134.418   3.725
#Mann= 3 ,0,0
       0    .035       0  48.662    .035       0  88.081    .035       0
Levee=-1,30.95964,10.90035,-1,114.9319,10.90035,,
Bank Sta=48.662,88.081
XS Rating Curve= 0 ,0
Exp/Cntr=0.3,0.1

Type RM Length L Ch R = 1 ,84      ,20,20,20
XS GIS Cut Line= 6
       589453.31     4874060.833      589396.117     4874086.307
      589357.118     4874103.679      589356.559     4874103.927
       589343.54     4874109.727      589330.581     4874115.498
#Sta/Elev= 30
       0   4.007    4.98   4.041   9.085   6.032  13.773    6.16  21.463   7.823
  25.416   7.525  30.989   4.404  36.444   4.213  38.221   4.288  41.502   4.708
  44.724   4.816  46.465   4.009  47.484   2.972  57.143   2.704  59.168   2.319
   62.61   2.078  70.188   2.233  72.909   2.893  77.581    2.99  82.152   4.705
  92.268   4.781 102.304    4.32 104.886    4.34 107.238    4.79 107.813   5.044
 110.434   6.857 111.551   7.449 118.251   7.675 124.386   3.713 134.353   3.677
#Mann= 3 ,0,0
       0    .035       0  44.724    .035       0  82.152    .035       0
Levee=-1,25.41585,10.81869,-1,112.8607,10.81869,,
Bank Sta=44.724,82.152
XS Rating Curve= 0 ,0
Exp/Cntr=0.3,0.1

Type RM Length L Ch R = 6 ,83.1    ,,,
Lateral Weir Pos= 3
Lateral Weir End=                ,                ,        ,north_01
Lateral Weir TW Multiple XS=0
Lateral Weir WD=1
Lateral Weir Coef=1.1
LW OverFlow Method 2D=0
LW OverFlow Use Velocity Into 2D=0
Lateral Weir WSCriteria=-1
Lateral Weir Flap Gates= 0
Lateral Weir Hagers EQN= 0 ,,,,,
Lateral Weir SS=0.05,0.05,
Lateral Weir Type= 0
Lateral Weir Connection Pos and Dist= 3 ,
Lateral Weir SE= 30
       0   7.609  30.289   6.886  31.719   6.333  41.356   6.991  50.301   6.774
  61.466   7.202  76.031    6.76  84.929   7.168  88.896   6.543  98.336   7.056
 110.337   6.274 121.754   7.012 124.631   6.379 128.501   7.031 146.101   6.599
 159.342   6.926 170.495   6.399 200.415   6.489 202.065   6.127  285.39   5.142
 307.179   6.222 333.326   4.569 380.279   5.526 385.695   5.108 421.257   5.389
 437.849   4.851 462.235   5.016 502.932   4.016 508.836   4.439 522.873   4.089
Lateral Weir Centerline= 6
589343.6464371414874102.56272748589260.7841541324873991.12724343
589214.3527024474873925.40888105589172.2072309174873864.69082884
589127.918769309 4873791.8291662589050.4139614954873670.03589678
LW Div RC= 0 ,False,,

Type RM Length L Ch R = 1 ,83      ,10,10,10
XS GIS Cut Line= 6
      589440.803     4874044.509      589345.499     4874086.959
      589343.914     4874087.666      589336.851     4874090.811
      589330.307     4874093.727      589317.948     4874099.231
#Sta/Elev= 30
       0   3.943   4.768   3.935   7.341    5.18   8.901   6.285  10.605   6.226
  16.749   7.636  22.274   7.548  27.228   4.508  33.367   4.144  43.396   4.598
  44.033   4.308  46.283   2.726  57.317   1.846  63.939    2.24  65.717   2.839
  73.392   2.878  74.903   4.091  76.053   4.533  77.634   4.843  85.925   4.901
  88.025   4.571  103.05   4.231 106.138   4.874 107.898   5.589 110.592    7.25
 113.798   7.131 117.574   7.526 120.639   4.711 120.974   3.358 134.491    3.35
#Mann= 3 ,0,0
       0    .035       0  44.033    .035       0  76.053    .035       0
Levee=-1,22.27417,10.73703,-1,114.1897,10.73703,,
Bank Sta=44.033,76.053
XS Rating Curve= 0 ,0
Exp/Cntr=0.3,0.1

Type RM Length L Ch R = 1 ,82      ,10,10,10
XS GIS Cut Line= 6
      589430.985     4874031.696      589423.373     4874036.057
      589412.856      4874042.08      589384.991     4874058.042
      589382.454     4874059.494      589316.511     4874097.267
#Sta/Elev= 30
       0   3.893   4.552   3.865   8.959   6.821  20.039   7.479  24.494   4.988
  26.022   4.544  30.991   4.102  34.178   4.448   42.15    4.46  44.854   2.582
  55.928   1.701  60.292   2.223  61.945   2.782   70.46   2.843  72.819   4.549
  74.126   4.801  82.333   4.861  83.881   4.593 101.113     4.2  104.71   5.152
 104.986   5.024  109.33   6.845  111.16   6.733 112.043   7.323 114.977   7.426
 116.669   5.719 118.368    4.73 118.587   3.901 118.626   3.376 131.924    3.35
#Mann= 3 ,0,0
       0    .035       0   42.15    .035       0  72.819    .035       0
Levee=-1,20.03857,10.6962,-1,112.0428,10.6962,,
Bank Sta=42.15,72.819
XS Rating Curve= 0 ,0
Exp/Cntr=0.3,0.1

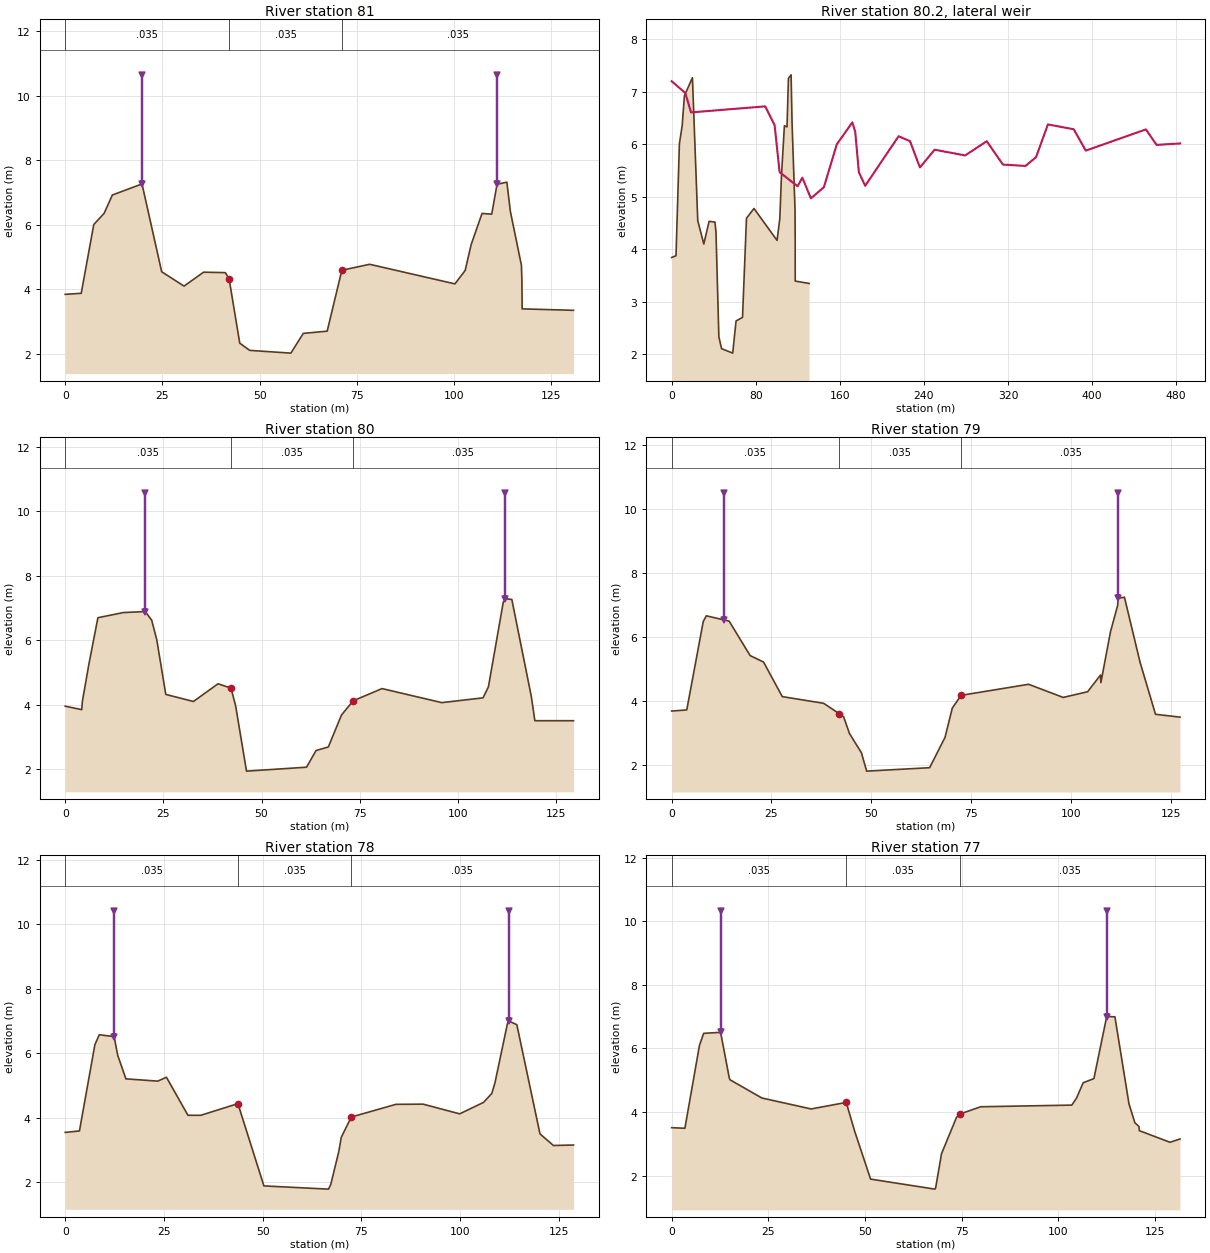
Type RM Length L Ch R = 1 ,81      ,20,20,20
XS GIS Cut Line= 6
      589421.408     4874019.198      589420.616     4874019.766
      589415.249     4874023.607      589394.407     4874038.529
      589391.827     4874040.375      589315.083     4874095.317
#Sta/Elev= 30
       0   3.845   4.122   3.878   7.352   6.012  10.013   6.358  12.129   6.927
  19.757    7.27  24.815   4.547  30.569   4.101  35.597   4.533  41.186   4.519
  42.163   4.328  44.902   2.331  47.473   2.107   58.05   2.022  61.249   2.635
  67.393   2.703   71.16   4.592   78.31   4.778 100.255    4.17 102.885   4.586
 104.425   5.387 107.228   6.355 109.718   6.333 111.089    7.26 113.614   7.325
 114.517   6.417 117.358   4.749 117.478    4.29 117.544   3.395 130.764    3.35
#Mann= 3 ,0,0
       0    .035       0  42.163    .035       0   71.16    .035       0
Levee=-1,19.75747,10.65537,-1,111.0893,10.65537,,
Bank Sta=42.163,71.16
XS Rating Curve= 0 ,0
Exp/Cntr=0.3,0.1

Type RM Length L Ch R = 6 ,80.2    ,,,
Lateral Weir Pos= 0
Lateral Weir End=                ,                ,        ,south_01
Lateral Weir TW Multiple XS=0
Lateral Weir WD=1
Lateral Weir Coef=1.1
LW OverFlow Method 2D=0
LW OverFlow Use Velocity Into 2D=0
Lateral Weir WSCriteria=-1
Lateral Weir Flap Gates= 0
Lateral Weir Hagers EQN= 0 ,,,,,
Lateral Weir SS=0.05,0.05,
Lateral Weir Type= 0
Lateral Weir Connection Pos and Dist= 3 ,
Lateral Weir SE= 30
       0   7.203  12.965   6.978  18.432   6.609      89   6.724  97.935   6.366
 102.674    5.47 119.766   5.201 124.276   5.366 132.461   4.971 144.792   5.184
 157.123   6.002 171.862   6.419 174.616   6.238 178.091   5.467 184.091   5.211
 215.887   6.155 226.735    6.06 236.158    5.56 250.128   5.898  279.22   5.789
 299.702    6.06 315.105   5.615 336.626   5.589  346.66   5.757 357.915    6.38
  382.45   6.288 393.959   5.881 451.104   6.285 461.325    5.99  483.58   6.017
Lateral Weir Centerline= 5
589398.3278215284874019.42847606589383.269949693 4873987.8069452
589307.2276969244873882.40184235589212.3631043624873747.63388943
589122.7687669424873622.65355319
LW Div RC= 0 ,False,,

Type RM Length L Ch R = 1 ,80      ,20,20,20
XS GIS Cut Line= 6
      589409.522     4874003.111      589385.674     4874020.184
      589382.968      4874022.12      589375.181     4874027.696
      589371.975      4874029.99      589304.257      4874078.47
#Sta/Elev= 30
       0   3.951   4.211   3.844   4.376   4.105   6.033   5.255   8.329   6.697
   14.85   6.858  20.392   6.887  22.026    6.62  23.319   6.013  25.618   4.316
  32.657   4.097  38.926   4.646  42.234   4.511  43.422   3.951  46.176   1.935
  61.466   2.057  63.884   2.574  67.013   2.685  70.371   3.679  73.343   4.118
  80.693   4.497  95.918   4.061 106.411    4.21 107.788   4.553 111.568    7.18
 112.117   7.286 113.747   7.264 118.712   4.249 119.612     3.5  129.46     3.5
#Mann= 3 ,0,0
       0    .035       0  42.234    .035       0  73.343    .035       0
Levee=-1,20.39182,10.57372,-1,112.1174,10.57372,,
Bank Sta=42.234,73.343
XS Rating Curve= 0 ,0
Exp/Cntr=0.3,0.1

Type RM Length L Ch R = 1 ,79      ,20,20,20
XS GIS Cut Line= 6
      589397.911     4873986.827      589390.848     4873991.882
      589386.205     4873995.207      589366.955     4874008.987
      589361.699     4874012.751      589294.386      4874060.94
#Sta/Elev= 30
       0    3.68   3.779   3.714   7.911   6.475   8.686   6.653  14.396   6.486
  19.654   5.411  23.023   5.208  27.707    4.13   38.07   3.921  41.909   3.602
  43.075   3.499  44.535   2.978  47.516   2.381  48.843   1.804  64.608   1.911
  68.467   2.858  70.291   3.773  72.508    4.17    89.4   4.515  98.056   4.105
 104.174   4.282 107.412   4.804 107.507   4.567 109.919    6.16 111.698   6.973
 111.838   7.197 113.403   7.234   117.3   5.209 121.187   3.578 127.319    3.49
#Mann= 3 ,0,0
       0    .035       0  41.909    .035       0  72.508    .035       0
Levee=-1,13.00603,10.49206,-1,111.8377,10.49206,,
Bank Sta=41.909,72.508
XS Rating Curve= 0 ,0
Exp/Cntr=0.3,0.1

Type RM Length L Ch R = 1 ,78      ,20,20,20
XS GIS Cut Line= 6
      589385.534     4873969.521      589351.282     4873995.244
      589348.094     4873997.637      589342.756     4874001.647
      589310.262     4874026.048      589282.568     4874046.847
#Sta/Elev= 30
       0    3.54   3.608   3.585   7.517   6.258   8.634   6.568  12.391    6.51
  13.306    5.93  15.375     5.2  23.444    5.13  25.642    5.25  31.087   4.072
  34.317   4.069   43.75   4.432  50.338   1.881  66.693   1.781  67.253   1.916
  69.304   2.945  69.933   3.387  72.464   4.016  83.779    4.41  90.666   4.416
   99.93   4.115 105.991   4.472 108.082   4.751 108.857   5.072 112.033   6.916
 112.362   6.992 114.405   6.881 120.268   3.495 123.672   3.134 128.768   3.149
#Mann= 3 ,0,0
       0    .035       0   43.75    .035       0  72.464    .035       0
Levee=-1,12.39101,10.4104,-1,112.362,10.4104,,
Bank Sta=43.75,72.464
XS Rating Curve= 0 ,0
Exp/Cntr=0.3,0.1

Type RM Length L Ch R = 1 ,77      ,20,20,20
XS GIS Cut Line= 6
      589373.858     4873953.277       589336.01     4873981.701
      589277.243     4874025.833      589277.147     4874025.906
      589270.813     4874030.663      589268.748     4874032.213
#Sta/Elev= 30
       0    3.51    3.42   3.492   7.197   6.104   8.273   6.476  12.658   6.508
  14.901   5.072  15.101   5.015  23.332   4.443  36.077   4.099  45.142   4.304
  47.333   3.393   51.44   1.893   68.06   1.578  68.262   1.617   69.79   2.696
  73.675   3.838  74.504   3.937  79.901   4.168 103.478    4.22 104.718   4.446
 106.409   4.923 109.187   5.053 112.502   7.005  114.62   6.996 118.259   4.261
 119.789   3.662 120.826   3.552 120.946   3.416 128.868   3.051  131.45   3.155
#Mann= 3 ,0,0
       0    .035       0  45.142    .035       0  74.504    .035       0
Levee=-1,12.6582,10.32874,-1,112.502,10.32874,,
Bank Sta=45.142,74.504
XS Rating Curve= 0 ,0
Exp/Cntr=0.3,0.1

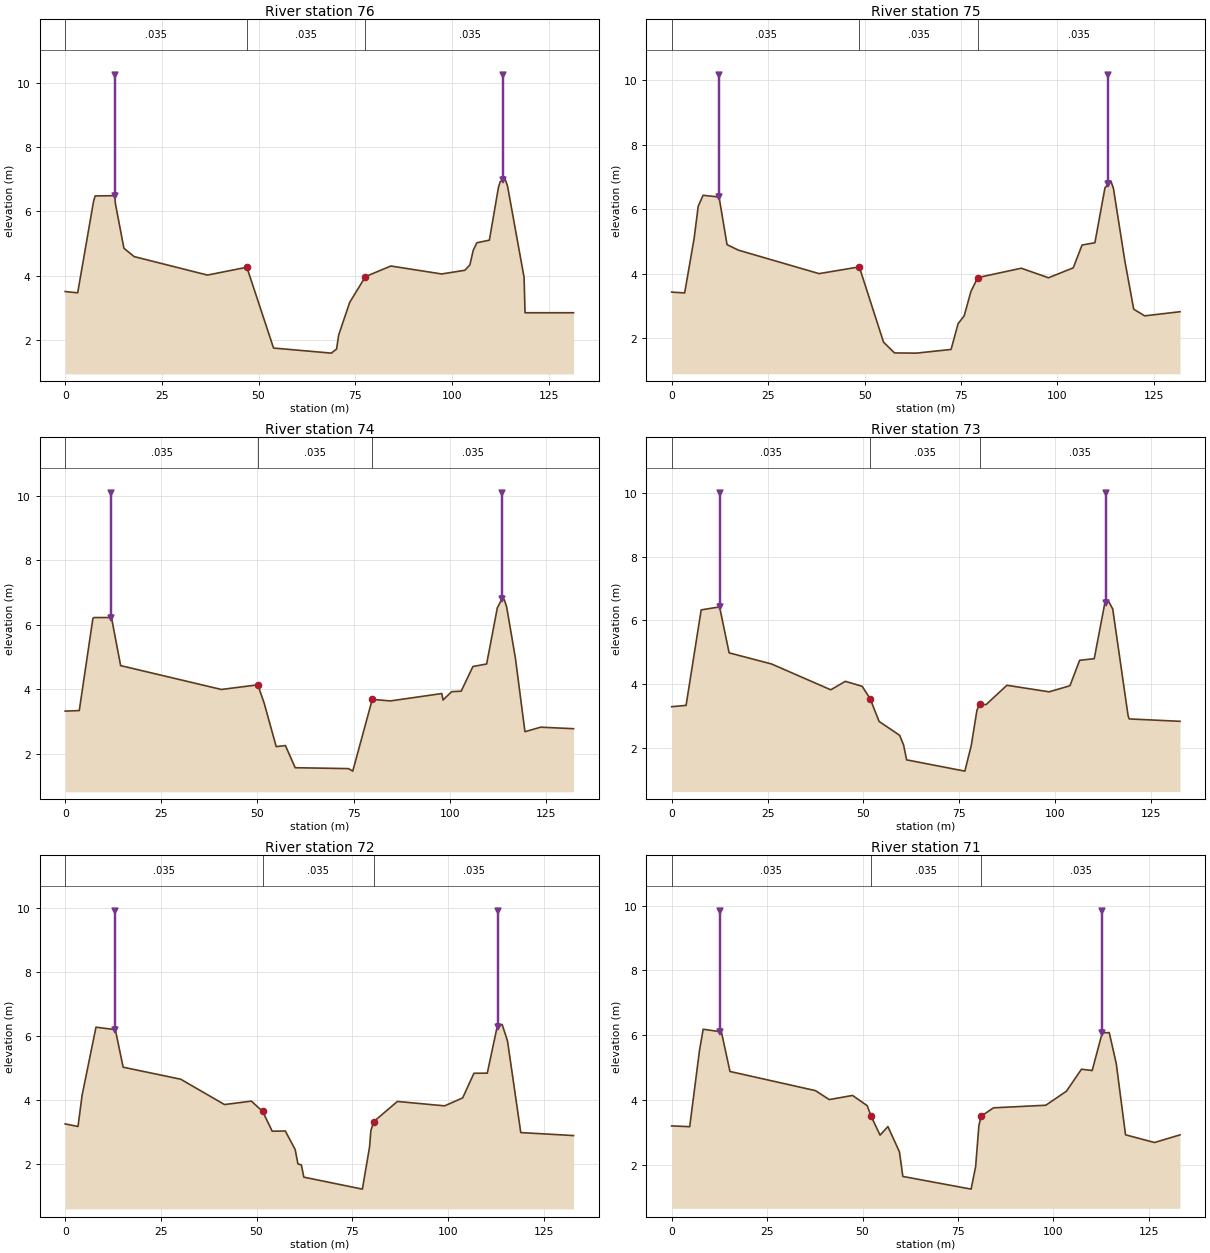
Type RM Length L Ch R = 1 ,76      ,20,20,20
XS GIS Cut Line= 6
      589362.032     4873937.147      589351.643     4873944.948
      589278.354     4873999.987      589274.321     4874003.017
      589268.644     4874007.279      589256.917     4874016.087
#Sta/Elev= 30
       0   3.509   3.225   3.469   7.331   6.313   7.744   6.481  12.811    6.49
  12.992   6.235  15.186   4.855  17.834   4.595  36.787   4.021  46.978   4.264
  53.879   1.752  68.826   1.594   70.18   1.723  70.719   2.157  73.568   3.171
  77.649   3.973  84.225   4.303  97.363   4.055 103.329    4.17 104.646   4.334
 105.526   4.794 106.456   5.026 109.691   5.106 112.033   6.743 112.516   6.931
 113.798    6.99 114.385   6.791 118.667    3.95 118.917    2.85 131.456    2.85
#Mann= 3 ,0,0
       0    .035       0  46.978    .035       0  77.649    .035       0
Levee=-1,12.811,10.24708,-1,113.2406,10.24708,,
Bank Sta=46.978,77.649
XS Rating Curve= 0 ,0
Exp/Cntr=0.3,0.1

Type RM Length L Ch R = 1 ,75      ,20,20,20
XS GIS Cut Line= 6
      589350.442     4873920.839      589345.782     4873924.339
       589344.94      4873924.97      589340.623     4873928.213
      589339.555     4873929.014      589245.087     4873999.959
#Sta/Elev= 30
       0   3.433   3.366   3.407   5.828   5.104    6.88   6.094   8.145   6.433
   12.28    6.38  14.354   4.903  17.286   4.733  38.204   4.005  48.629   4.214
  54.917   1.882  57.758   1.548  63.432   1.542  72.421   1.656  74.242   2.455
  75.818   2.697  77.562   3.451  79.327   3.882  90.614   4.173  97.673   3.877
 104.091   4.185 106.371   4.892 109.699   4.962 112.303   6.662 113.846    6.87
 114.498   6.651 117.438   4.415  119.76   2.904 122.589   2.697 131.756   2.825
#Mann= 3 ,0,0
       0    .035       0  48.629    .035       0  79.327    .035       0
Levee=-1,12.2796,10.16542,-1,113.1106,10.16542,,
Bank Sta=48.629,79.327
XS Rating Curve= 0 ,0
Exp/Cntr=0.3,0.1

Type RM Length L Ch R = 1 ,74      ,20,20,20
XS GIS Cut Line= 6
      589338.975     4873904.439      589327.767     4873912.855
      589279.175     4873949.348      589275.236     4873952.306
      589275.112     4873952.398      589233.258      4873983.83
#Sta/Elev= 30
       0   3.324   3.656    3.34   7.204   6.196   7.582   6.222  12.038   6.221
  14.414   4.733  40.625   3.994  50.092   4.138  51.743   3.572  54.882   2.224
  57.274   2.257  59.818   1.571  73.661   1.543  74.785   1.465  79.866   3.686
  84.568   3.639  97.952   3.868   98.26   3.667 100.497   3.925 102.989   3.941
 106.041   4.705 109.609   4.783 112.386   6.521 113.616   6.802 114.171   6.781
 114.804   6.558 117.075   4.977 119.574   2.686 123.652   2.826 132.208   2.779
#Mann= 3 ,0,0
       0    .035       0  50.092    .035       0  79.866    .035       0
Levee=-1,12.0376,10.08377,-1,113.6156,10.08377,,
Bank Sta=50.092,79.866
XS Rating Curve= 0 ,0
Exp/Cntr=0.3,0.1

Type RM Length L Ch R = 1 ,73      ,20,20,20
XS GIS Cut Line= 6
      589327.372      4873888.14      589316.541     4873896.275
      589315.634     4873896.955      589237.146     4873955.898
      589236.245     4873956.576      589221.423     4873967.706
#Sta/Elev= 30
       0   3.292   3.755   3.333   7.694   6.329  12.491   6.423  14.977   4.981
  26.028   4.632   41.47   3.822  45.279   4.087  49.648   3.932  51.717   3.546
  54.074   2.829  59.423   2.394  60.466   2.084  61.234   1.624  76.415    1.27
  78.089   2.072  79.564   3.176  80.243   3.368  81.954   3.358  87.384   3.964
   98.38   3.758 103.812   3.949 106.342   4.748 110.145   4.798 112.836   6.499
 113.808   6.616 114.966   6.357 118.966   3.012 119.256   2.908 132.499   2.833
#Mann= 3 ,0,0
       0    .035       0  51.717    .035       0  80.243    .035       0
Levee=-1,12.491,10.00211,-1,113.132,10.00211,,
Bank Sta=51.717,80.243
XS Rating Curve= 0 ,0
Exp/Cntr=0.3,0.1

Type RM Length L Ch R = 1 ,72      ,20,20,20
XS GIS Cut Line= 6
      589315.835     4873871.793      589305.357     4873879.662
      589303.912     4873880.746      589303.727     4873880.886
      589265.971     4873909.239       589209.61     4873951.566
#Sta/Elev= 30
       0   3.252   3.348   3.171   4.415    4.15   8.044   6.279  13.104   6.202
  15.142   5.027  30.177   4.651  41.628   3.858  48.646   3.965  51.599   3.643
  54.099   3.023  57.518    3.03    60.1    2.45  60.818       2  61.718    1.97
  62.359   1.586  77.662   1.211  79.539   2.532  79.881   3.045  80.641   3.324
  86.812   3.955  99.154   3.817 103.864   4.065 106.821   4.837 110.306    4.84
 112.861   6.278 114.183   6.366 115.587    5.85 119.056   2.981 132.844   2.887
#Mann= 3 ,0,0
       0    .035       0  51.599    .035       0  80.641    .035       0
Levee=-1,13.1038,9.920447,-1,113.1156,9.920447,,
Bank Sta=51.599,80.641
XS Rating Curve= 0 ,0
Exp/Cntr=0.3,0.1

Type RM Length L Ch R = 1 ,71      ,20,20,20
XS GIS Cut Line= 6
      589304.296     4873855.447      589294.169     4873863.051
      589209.443      4873926.68      589209.219     4873926.847
      589203.149     4873931.407       589197.81     4873935.415
#Sta/Elev= 30
       0     3.2   4.723   3.176   7.303   5.539   8.256   6.184  13.027   6.102
  15.274    4.88  37.665   4.289  41.291   4.012  47.386    4.14  51.225   3.824
  52.245     3.5  54.596   2.914  56.653    3.18  59.672   2.399  60.562    1.64
  78.446   1.248  79.634   1.943  80.474   3.197  81.051   3.498  84.323   3.758
  98.008   3.837 103.417    4.27 107.359   4.949 110.162   4.909 112.796   6.072
 114.635    6.08 116.475   5.123 118.902   2.925 126.494   2.687  133.17   2.923
#Mann= 3 ,0,0
       0    .035       0  52.245    .035       0  81.051    .035       0
Levee=-1,12.664,9.838789,-1,112.7956,9.838789,,
Bank Sta=52.245,81.051
XS Rating Curve= 0 ,0
Exp/Cntr=0.3,0.1

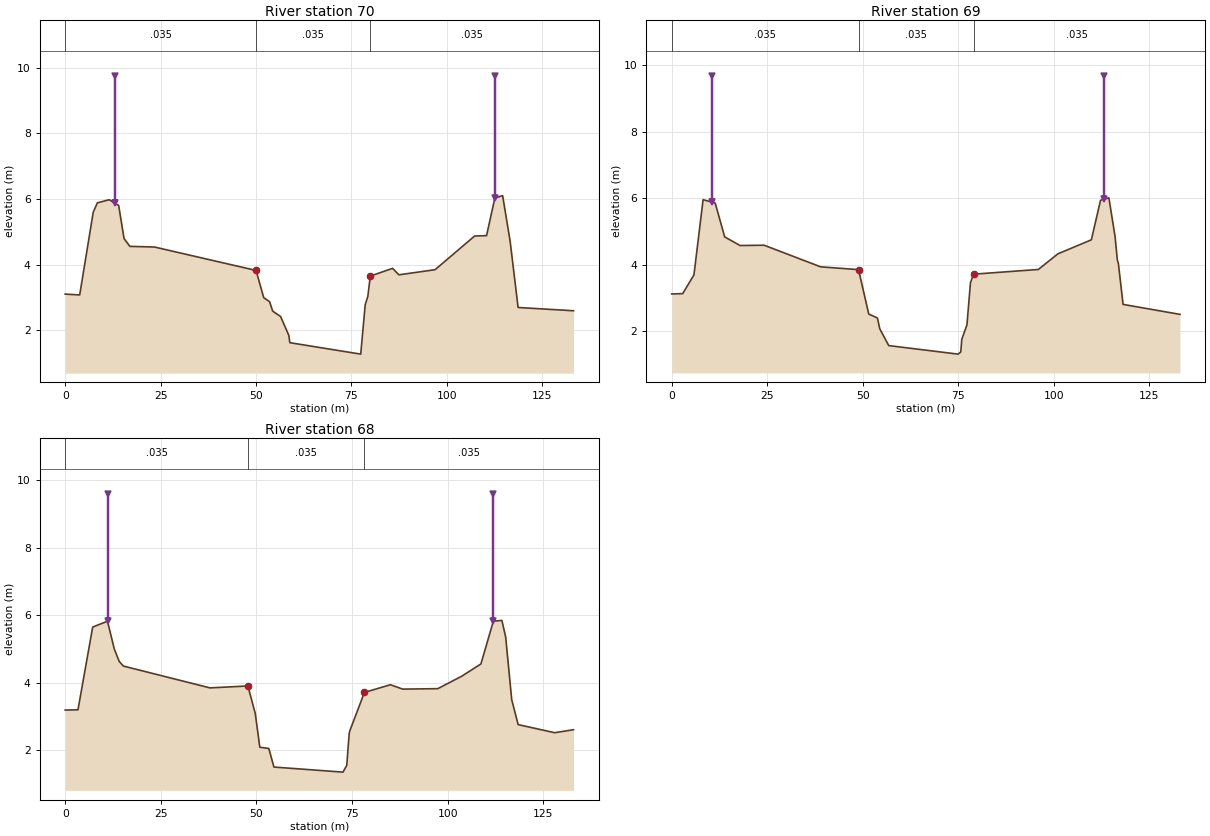
Type RM Length L Ch R = 1 ,70      ,20,20,20
XS GIS Cut Line= 6
      589292.467     4873839.318      589228.534      4873887.33
      589208.675     4873902.245      589202.435      4873906.93
      589200.286     4873908.545      589185.946     4873919.313
#Sta/Elev= 30
       0   3.103   3.798   3.077   7.342   5.597   8.431   5.885  11.546    5.98
  14.009   5.807  15.427   4.795  16.961   4.558  23.396   4.538  50.016   3.824
  52.021   2.996  53.562   2.872  54.374   2.584  56.444   2.421  58.609   1.842
  58.866   1.622  77.444   1.273  78.616   2.776  79.314   3.037  79.954   3.652
  85.794   3.888  87.446   3.691  96.932   3.847 107.298   4.874 110.422   4.885
 112.593   6.032 114.632   6.106 116.602   4.713 118.689   2.695 133.214   2.595
#Mann= 3 ,0,0
       0    .035       0  50.016    .035       0  79.954    .035       0
Levee=-1,13.026,9.757131,-1,112.5928,9.757131,,
Bank Sta=50.016,79.954
XS Rating Curve= 0 ,0
Exp/Cntr=0.3,0.1

Type RM Length L Ch R = 1 ,69      ,20,20,20
XS GIS Cut Line= 6
      589280.523     4873823.276      589207.968     4873877.763
      589203.758     4873880.926       589202.37     4873881.967
      589191.652     4873890.016      589174.098       4873903.2
#Sta/Elev= 30
       0   3.124   2.884   3.133   5.833   3.696   8.228   5.955    11.4   5.854
  13.872   4.838  17.911   4.578  24.219   4.587  39.001   3.938  48.927   3.854
  51.602    2.52  53.874   2.402  54.492   2.075  56.844   1.572  74.995   1.316
    75.7   1.381  75.962   1.763   77.31   2.193  78.231    3.46  79.035   3.717
  96.002   3.859 101.112   4.328 109.887    4.75 112.289   5.938 114.481   6.009
 116.096   4.846 116.687   4.148 116.977   4.025 118.189    2.81 133.094    2.51
#Mann= 3 ,0,0
       0    .035       0  48.927    .035       0  79.035    .035       0
Levee=-1,10.4512,9.675472,-1,113.1498,9.675472,,
Bank Sta=48.927,79.035
XS Rating Curve= 0 ,0
Exp/Cntr=0.3,0.1

Type RM Length L Ch R = 1 ,68      ,20,20,20
XS GIS Cut Line= 6
      589268.531      4873807.27      589205.978     4873854.246
      589205.356     4873854.714      589176.447     4873876.423
      589175.186     4873877.371      589162.263     4873887.076
#Sta/Elev= 30
       0   3.192   3.339   3.199   7.186   5.649  11.061   5.822  12.816   5.006
  14.119   4.631  15.199   4.495  37.854   3.848  47.761   3.905  49.698   3.086
  50.879   2.091  53.238   2.055  54.567   1.504  72.626   1.354  73.603   1.554
  74.241   2.483  74.391   2.571  78.228   3.714  85.014   3.941  88.233   3.812
  97.408   3.825 103.665   4.193 108.692   4.558 111.939   5.823 114.169   5.845
 115.159   5.353 116.737   3.499 118.417   2.761 127.976   2.521 132.898    2.61
#Mann= 3 ,0,0
       0    .035       0  47.761    .035       0  78.228    .035       0
Levee=-1,11.0612,9.593814,-1,111.9392,9.593814,,
Bank Sta=47.761,78.228
XS Rating Curve= 0 ,0
Exp/Cntr=0.3,0.1