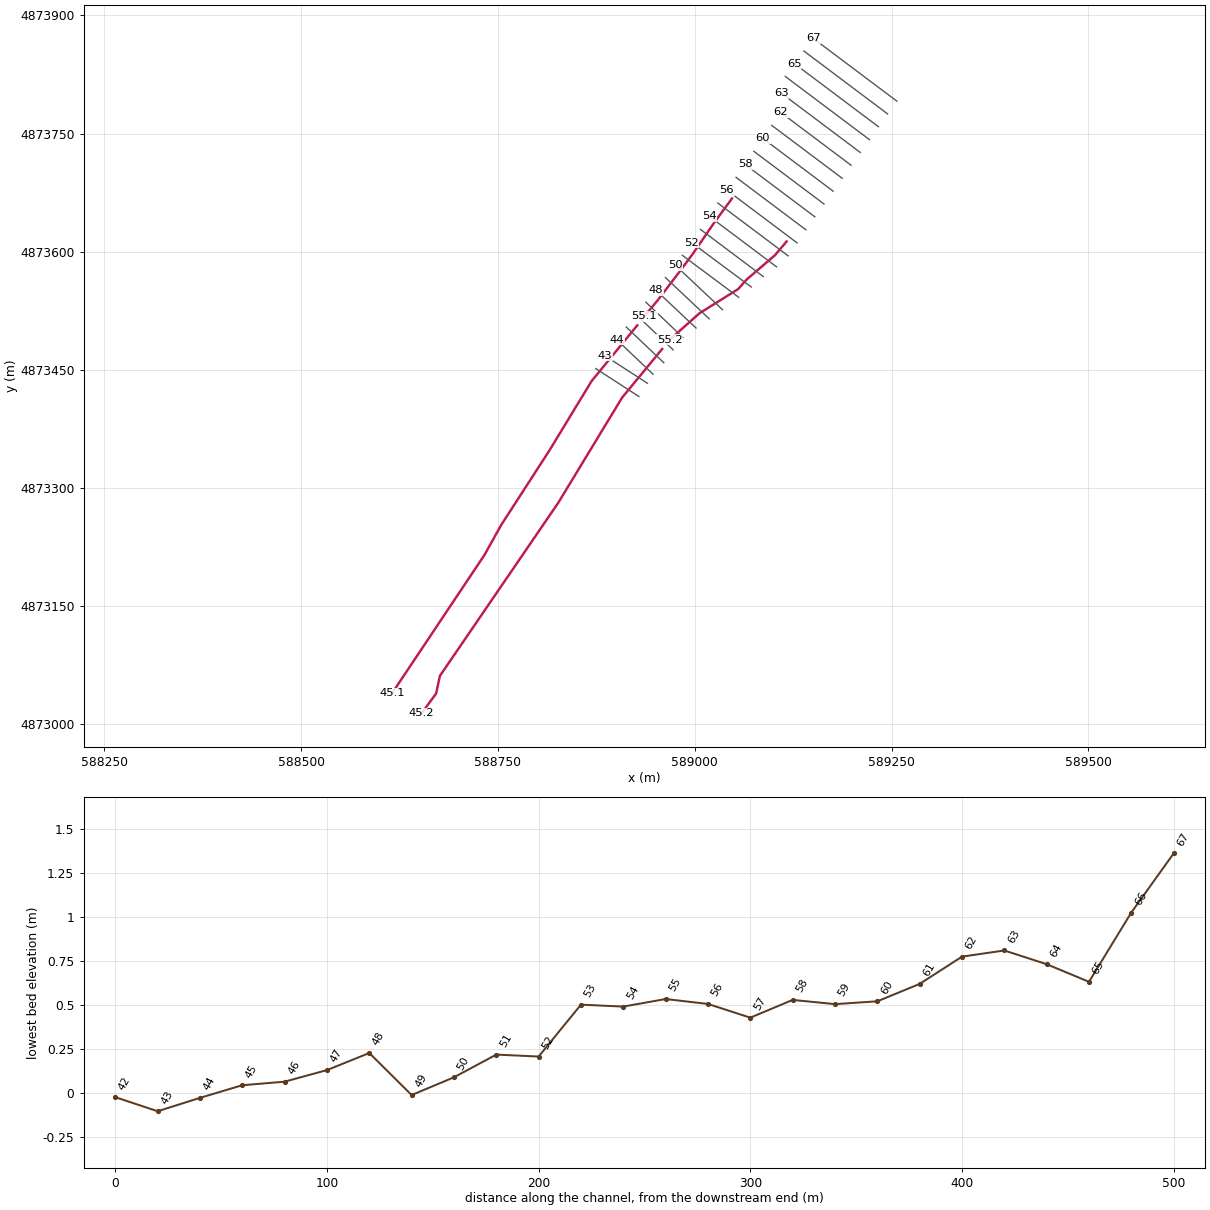
HEC-RAS study massa.prj: massa

--- massa.g05 (geometry) --- (continued)

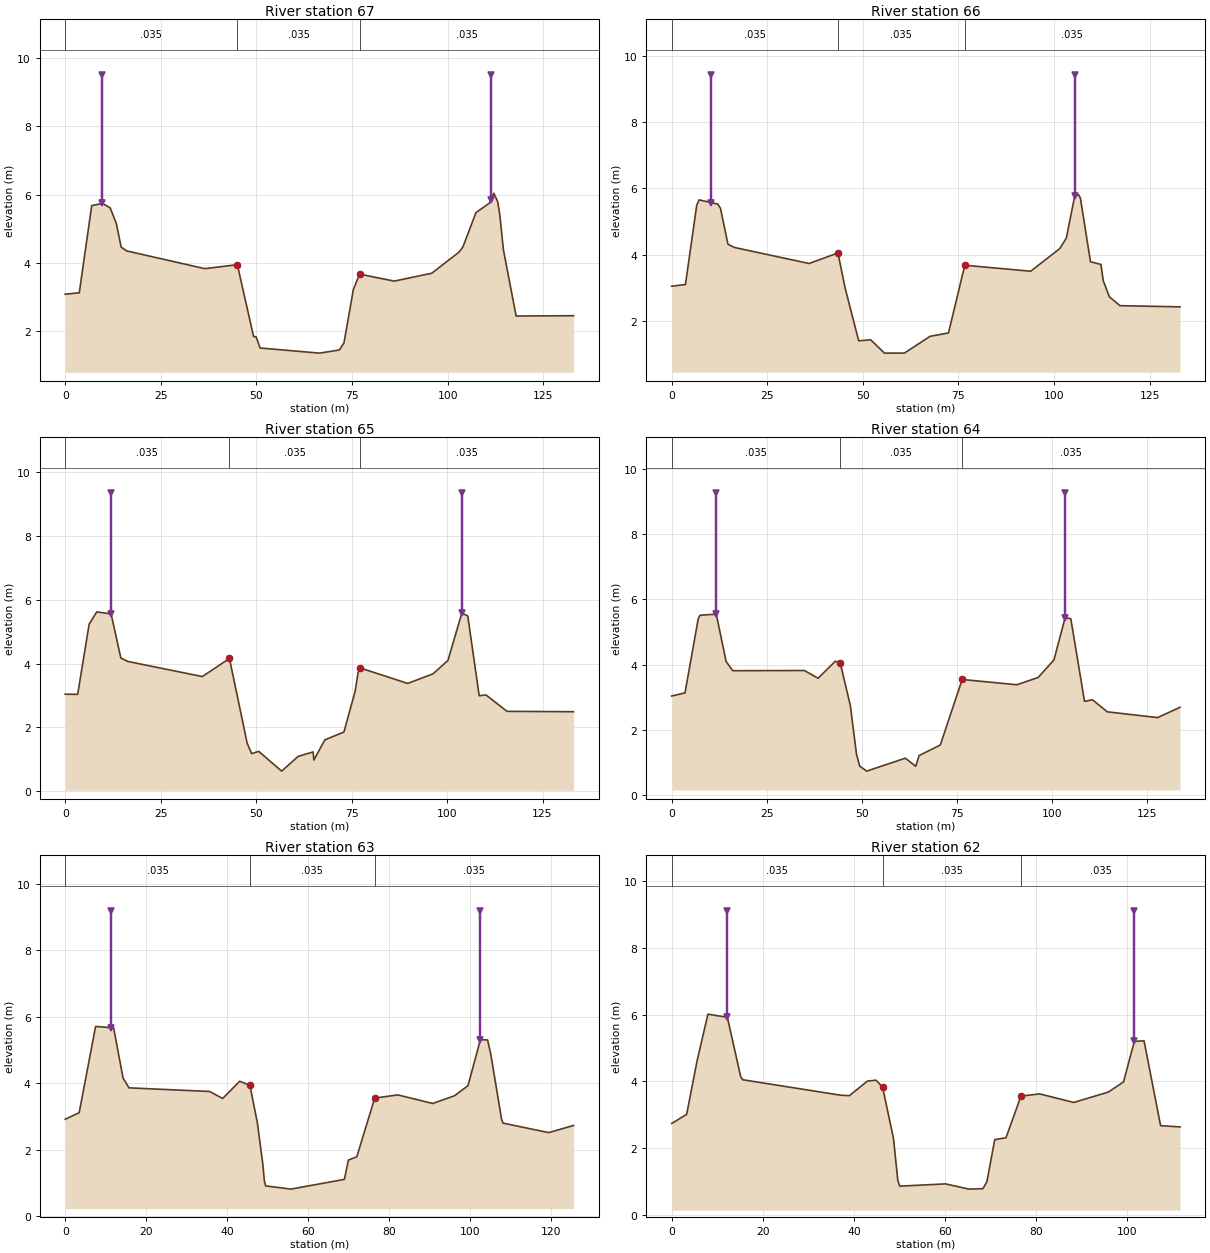
Type RM Length L Ch R = 1 ,67      ,20,20,20
XS GIS Cut Line= 6
      589256.684     4873791.155      589200.657     4873833.231
      589198.156     4873835.108      589168.896     4873857.083
      589165.849      4873859.37      589150.433     4873870.948
#Sta/Elev= 30
       0   3.087   3.683   3.129   6.926   5.682   9.737   5.745  11.757   5.617
  13.359    5.16  14.627   4.466  16.103   4.354  36.491   3.835  44.999   3.951
  49.239   1.848  49.916   1.838  50.933   1.511  66.504   1.361  71.648   1.453
  72.872    1.66  75.322   3.222  76.954   3.674  86.017   3.471    95.8     3.7
 102.914   4.317 103.953   4.468 107.365   5.475 110.991   5.764 112.033   6.044
 113.034   5.806 113.597   5.419 114.549   4.388 117.871   2.448 132.877   2.457
#Mann= 3 ,0,0
       0    .035       0  44.999    .035       0  76.954    .035       0
Levee=-1,9.737032,9.512156,-1,111.3415,9.512156,,
Bank Sta=44.999,76.954
XS Rating Curve= 0 ,0
Exp/Cntr=0.3,0.1

Type RM Length L Ch R = 1 ,66      ,20,20,20
XS GIS Cut Line= 6
      589244.907     4873774.988      589242.028     4873777.149
      589215.466     4873797.098       589203.28     4873806.248
      589195.323     4873812.225      589138.602     4873854.821
#Sta/Elev= 30
       0   3.046     3.6   3.097   6.559   5.496   7.178   5.654   12.06   5.526
  12.753   5.403  14.725   4.313  16.455   4.215   35.95   3.732  43.484    4.05
  45.354   2.996  48.913   1.397  52.058   1.427  55.649   1.025  60.882   1.026
  67.586   1.533  72.393   1.634  76.665    3.68  93.889   3.498  101.51   4.183
 103.223   4.502 105.394    5.76 106.428   5.808 106.908   5.703 109.535   3.785
 112.266   3.704 112.867   3.215 114.478   2.725 117.245   2.458 132.944   2.423
#Mann= 3 ,0,0
       0    .035       0  43.484    .035       0  76.665    .035       0
Levee=-1,10.39342,9.430497,-1,105.5685,9.430497,,
Bank Sta=43.484,76.665
XS Rating Curve= 0 ,0
Exp/Cntr=0.3,0.1

Type RM Length L Ch R = 1 ,65      ,20,20,20
XS GIS Cut Line= 6
      589233.224      4873758.75       589230.61     4873760.712
      589220.087     4873768.616       589219.53     4873769.033
      589191.294     4873790.239      589126.772     4873838.693
#Sta/Elev= 30
       0   3.041   3.268   3.036    6.27   5.236   8.257   5.619  12.024   5.557
  14.564   4.175  16.429   4.066  35.918   3.593  43.013    4.16  47.651   1.508
   48.82    1.18  50.683    1.25  56.693    .631  60.996   1.092  64.918   1.232
  65.124     .98  68.005   1.611  72.996   1.856  75.935   3.135  76.707   3.721
  77.334    3.86  89.703   3.378  96.311   3.678  100.23   4.096 103.877   5.581
 105.427   5.494 108.416   2.993 110.208   3.017 115.705   2.504 133.127   2.492
#Mann= 3 ,0,0
       0    .035       0  43.013    .035       0  77.334    .035       0
Levee=-1,12.024,9.348839,-1,103.8772,9.348839,,
Bank Sta=43.013,77.334
XS Rating Curve= 0 ,0
Exp/Cntr=0.3,0.1

Type RM Length L Ch R = 1 ,64      ,20,20,20
XS GIS Cut Line= 6
      589221.904     4873742.239      589193.961     4873763.223
      589192.326     4873764.452      589191.098     4873765.373
      589148.774     4873797.159      589114.942     4873822.565
#Sta/Elev= 30
       0   3.035    3.51   3.131   6.994   5.409   7.466   5.512  11.737   5.546
  14.327   4.092    16.1   3.811  34.945   3.817  38.525    3.58  43.052   4.101
  44.358    4.05  47.018   2.742  48.643   1.247  49.474    .887   51.32    .731
  61.485   1.128   64.23    .879  65.098   1.208  70.687   1.531  76.446   3.542
  90.853    3.38  96.439   3.604  100.59    4.14 103.538   5.438 105.033   5.405
  108.64   2.872  110.75   2.919 114.621    2.55 127.874   2.373 133.765   2.688
#Mann= 3 ,0,0
       0    .035       0  44.358    .035       0  76.446    .035       0
Levee=-1,11.7368,9.26718,-1,103.5378,9.26718,,
Bank Sta=44.358,76.446
XS Rating Curve= 0 ,0
Exp/Cntr=0.3,0.1

Type RM Length L Ch R = 1 ,63      ,20,20,20
XS GIS Cut Line= 6
      589210.248      4873725.98      589206.231     4873728.998
      589200.675     4873733.169       589198.81     4873734.571
      589170.878     4873755.546      589109.771     4873801.437
#Sta/Elev= 30
       0   2.912   3.458    3.11   7.513   5.707  11.972   5.661  14.305   4.153
  15.769   3.857  35.687   3.748  38.926   3.538   43.13   4.055  45.655   3.933
  47.499   2.809  48.831   1.583  49.236    1.05   49.55    .907  55.761    .809
  69.006   1.102  70.014   1.685  72.076   1.781  76.514   3.549  82.207   3.645
   90.85   3.387  96.211   3.618  99.572   3.924 102.632   5.307 104.412   5.299
 105.196   4.873 107.868   2.914 108.232   2.796 119.526    2.51 125.656   2.725
#Mann= 3 ,0,0
       0    .035       0  45.655    .035       0  76.514    .035       0
Levee=-1,11.24041,9.185522,-1,102.6323,9.185522,,
Bank Sta=45.655,76.514
XS Rating Curve= 0 ,0
Exp/Cntr=0.3,0.1

Type RM Length L Ch R = 1 ,62      ,20,20,20
XS GIS Cut Line= 6
      589198.466     4873709.817      589159.689     4873738.937
      589159.551     4873739.042      589146.289        4873749.
      589143.151     4873751.358       589109.28     4873776.794
#Sta/Elev= 30
       0    2.74   3.288   3.011   5.565   4.608   7.956   6.011  12.217   5.917
  15.154   4.135  15.595   4.048  37.067   3.585  39.008   3.572  42.945   4.008
  44.851   4.034  46.282   3.823  48.667   2.295  49.622   1.035  50.048    .863
  60.082    .931  65.251    .774  68.293    .788  69.177    .999  70.884   2.256
  73.352   2.311  76.642   3.558  80.767   3.624  88.224   3.368  95.802   3.678
  99.138   3.983 101.522   5.198 103.646   5.212  107.28   2.673 111.535   2.636
#Mann= 3 ,0,0
       0    .035       0  46.282    .035       0  76.642    .035       0
Levee=-1,12.2168,9.103864,-1,101.5224,9.103864,,
Bank Sta=46.282,76.642
XS Rating Curve= 0 ,0
Exp/Cntr=0.3,0.1

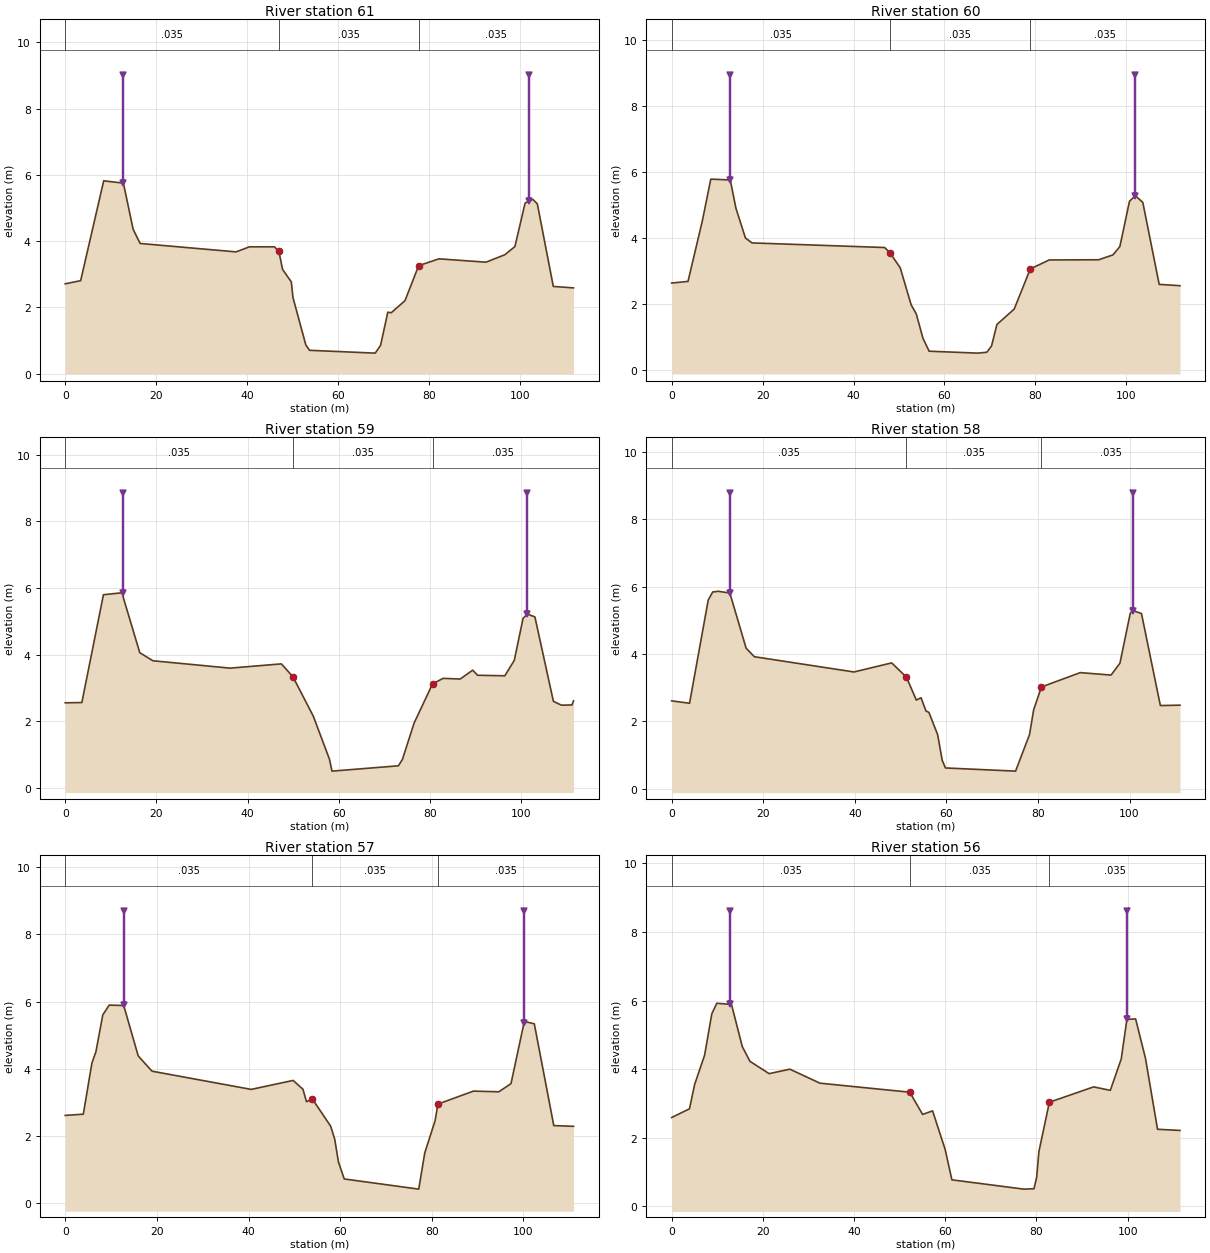
Type RM Length L Ch R = 1 ,61      ,20,20,20
XS GIS Cut Line= 6
      589187.201     4873693.265       589180.43     4873698.349
      589179.285      4873699.21      589155.924     4873716.754
       589149.62     4873721.487      589097.794     4873760.408
#Sta/Elev= 30
       0   2.712   3.397   2.807   8.467   5.822  12.801   5.752  14.946   4.356
  16.479    3.93   37.59   3.676  40.504   3.828  46.013   3.829  46.998   3.694
  47.806   3.149  49.737   2.768   50.09   2.302  52.922    .868  53.742    .704
  68.193    .619  69.359     .85   70.96   1.854  71.716   1.839  74.734   2.202
   77.75    3.26  82.208   3.466  92.569   3.365  96.689   3.589   98.92   3.837
 101.159   5.151 102.852   5.262  103.85   5.126 107.362   2.632 111.811   2.589
#Mann= 3 ,0,0
       0    .035       0  46.998    .035       0   77.75    .035       0
Levee=-1,12.80101,9.022205,-1,101.9444,9.022205,,
Bank Sta=46.998,77.75
XS Rating Curve= 0 ,0
Exp/Cntr=0.3,0.1

Type RM Length L Ch R = 1 ,60      ,20,20,20
XS GIS Cut Line= 6
      589175.739     4873676.861      589135.545     4873707.045
       589102.18     4873732.103       589098.13     4873735.143
      589093.309     4873738.765      589086.338     4873743.999
#Sta/Elev= 30
       0    2.64   3.593    2.69   6.751   4.525   8.608   5.785  12.892   5.759
  14.122    4.91   16.22   4.005  17.664   3.855  46.856   3.715  48.067   3.544
  50.266   3.104  52.667   1.984  53.802   1.704  55.273    .968  56.632    .578
   67.37     .52  69.327    .548  70.356    .737  71.531   1.386   75.34   1.853
  78.885    3.07   83.05   3.339  93.924   3.345  97.056   3.492  98.579   3.745
 100.697   5.115 101.973   5.284 103.626    5.08 107.228     2.6 111.804    2.56
#Mann= 3 ,0,0
       0    .035       0  48.067    .035       0  78.885    .035       0
Levee=-1,12.8924,8.940547,-1,101.973,8.940547,,
Bank Sta=48.067,78.885
XS Rating Curve= 0 ,0
Exp/Cntr=0.3,0.1

Type RM Length L Ch R = 1 ,59      ,20,20,20
XS GIS Cut Line= 6
      589164.145     4873660.556      589117.367     4873695.686
      589094.883      4873712.57       589083.86     4873720.849
       589077.13     4873725.902      589075.014     4873727.492
#Sta/Elev= 30
       0   2.555    3.65   2.563   8.383     5.8  12.592    5.86   12.76   5.705
  16.356   4.058  19.244   3.817  36.138   3.596  47.414   3.724   49.95   3.333
  54.408   2.152  57.958    .858    58.5    .504  73.062    .664  73.951    .857
  76.506   1.946  80.548   3.123   82.88   3.289  86.618   3.269  89.357   3.535
  90.421   3.382  96.396   3.366  98.468   3.828 100.404   5.091 101.322   5.219
 102.997   5.134 107.049     2.6  108.82   2.484 111.139   2.491 111.466   2.615
#Mann= 3 ,0,0
       0    .035       0   49.95    .035       0  80.548    .035       0
Levee=-1,12.59181,8.858889,-1,101.3224,8.858889,,
Bank Sta=49.95,80.548
XS Rating Curve= 0 ,0
Exp/Cntr=0.3,0.1

Type RM Length L Ch R = 1 ,58      ,20,20,20
XS GIS Cut Line= 6
      589152.543     4873644.257      589123.009     4873666.436
      589112.675     4873674.198      589111.548     4873675.043
      589106.909     4873678.528      589063.775      4873710.92
#Sta/Elev= 30
       0   2.611   3.903    2.54   7.981   5.597   8.957   5.838   10.16   5.859
  12.708   5.807  16.261   4.171  18.055   3.919  39.824   3.467  48.045   3.736
  51.268   3.314   53.43   2.634  54.454   2.703  55.546   2.309  56.178    2.27
  58.083    1.61  59.087    .848   59.79    .622  75.105    .528  78.151   1.612
  79.057   2.347  80.751   3.022  89.231   3.448  95.958   3.375    97.9   3.729
 100.151   5.206 100.807   5.284 102.597     5.2 106.725   2.472 111.012   2.483
#Mann= 3 ,0,0
       0    .035       0  51.268    .035       0  80.751    .035       0
Levee=-1,12.70821,8.77723,-1,100.8074,8.77723,,
Bank Sta=51.268,80.751
XS Rating Curve= 0 ,0
Exp/Cntr=0.3,0.1

Type RM Length L Ch R = 1 ,57      ,20,20,20
XS GIS Cut Line= 6
      589141.178      4873627.78      589076.353     4873676.462
      589066.594     4873683.792      589065.764     4873684.414
      589055.928     4873691.802      589052.483     4873694.388
#Sta/Elev= 30
       0   2.617   3.952   2.654   5.825    4.17   6.702   4.509   8.201   5.603
   9.596   5.894  12.768   5.883  15.929   4.385  18.944   3.931  40.591    3.39
   49.74   3.657  51.878   3.393   52.66   3.023  53.918   3.108  57.928   2.297
  58.812   1.909   59.63   1.231  60.885    .729  77.143    .427  78.461   1.505
  80.693    2.45  81.337   2.954  89.083   3.339  94.619   3.319  97.275   3.561
 100.101   5.356 100.787    5.39 102.359   5.339 106.613   2.315 110.921   2.293
#Mann= 3 ,0,0
       0    .035       0  53.918    .035       0  81.337    .035       0
Levee=-1,12.76821,8.695572,-1,100.101,8.695572,,
Bank Sta=53.918,81.337
XS Rating Curve= 0 ,0
Exp/Cntr=0.3,0.1

Type RM Length L Ch R = 1 ,56      ,20,20,20
XS GIS Cut Line= 6
      589129.956     4873611.196      589076.685     4873651.201
      589068.191     4873657.581      589066.409     4873658.918
      589059.944     4873663.773      589040.801      4873678.15
#Sta/Elev= 30
       0   2.592   3.904   2.845   5.047   3.559   7.219   4.405   8.806   5.613
   9.893    5.92   13.12   5.887  15.482    4.66  17.174   4.228  21.372    3.87
  25.932       4  32.521   3.592  52.225   3.329  55.037   2.681  57.231   2.785
  59.983   1.661  61.465    .776  77.243    .505  79.471    .516  80.053    .847
  80.553   1.601  82.849   3.037  92.552   3.484  96.215   3.383  98.611   4.299
  99.847   5.451 101.763   5.464  103.92   4.319  106.57   2.249 111.496   2.215
#Mann= 3 ,0,0
       0    .035       0  52.225    .035       0  82.849    .035       0
Levee=-1,12.8632,8.613914,-1,99.84685,8.613914,,
Bank Sta=52.225,82.849
XS Rating Curve= 0 ,0
Exp/Cntr=0.3,0.1

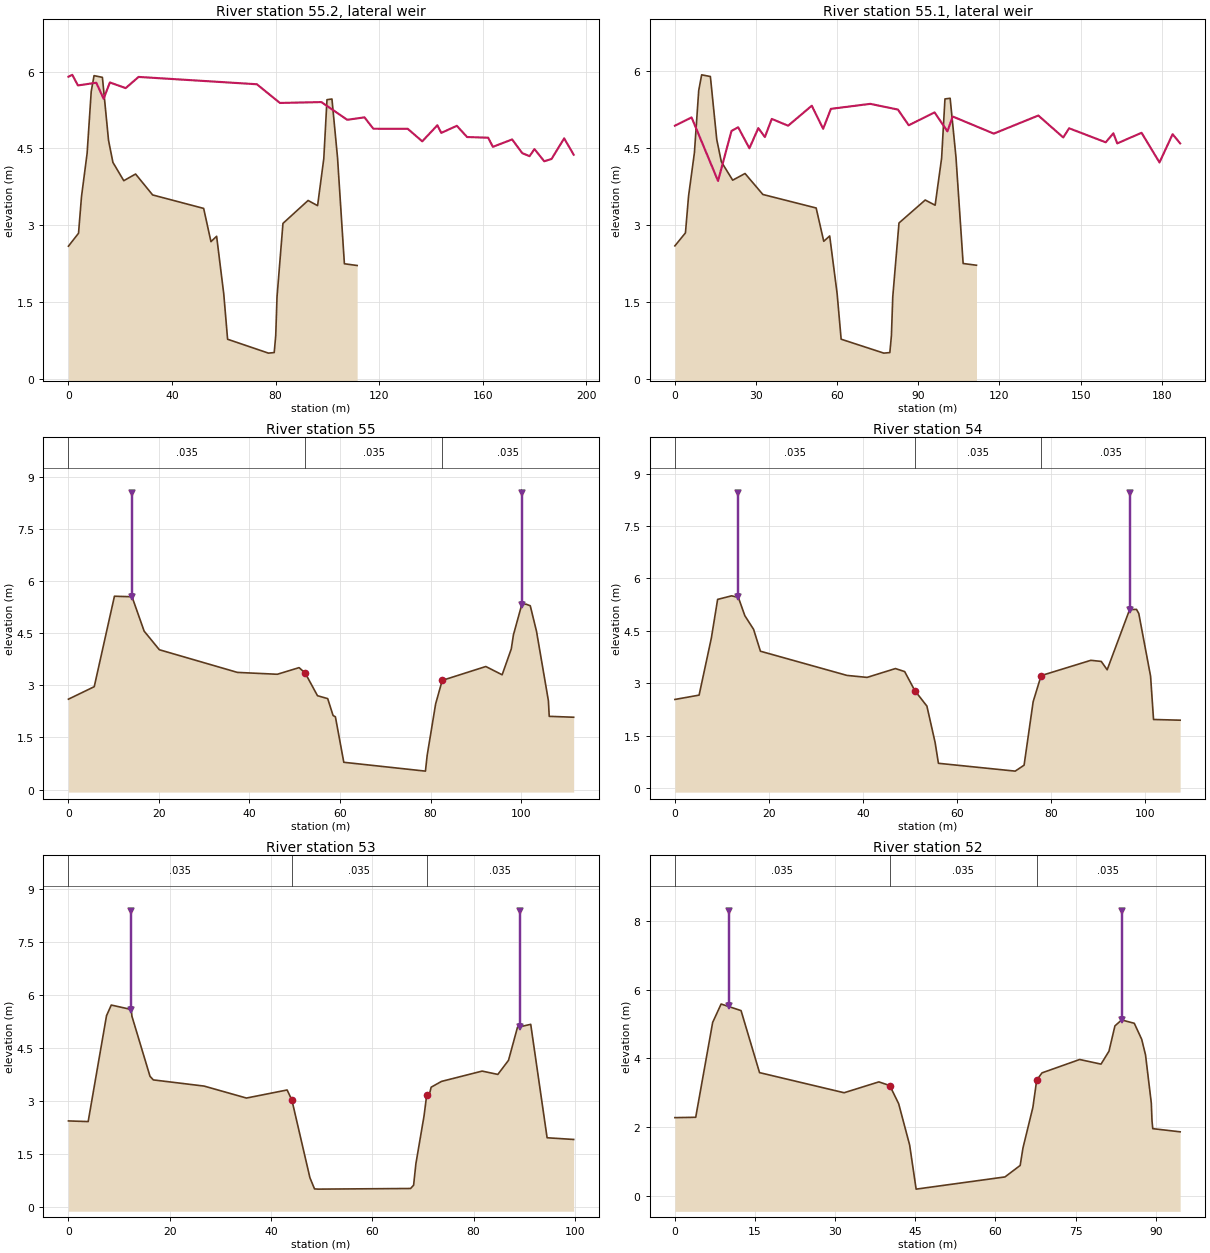
Type RM Length L Ch R = 6 ,55.2    ,,,
Lateral Weir Pos= 0
Lateral Weir End=                ,                ,        ,south_01
Lateral Weir TW Multiple XS=0
Lateral Weir WD=1
Lateral Weir Coef=1.1
LW OverFlow Method 2D=0
LW OverFlow Use Velocity Into 2D=0
Lateral Weir WSCriteria=-1
Lateral Weir Flap Gates= 0
Lateral Weir Hagers EQN= 0 ,,,,,
Lateral Weir SS=0.05,0.05,
Lateral Weir Type= 0
Lateral Weir Connection Pos and Dist= 3 ,
Lateral Weir SE= 30
       0   5.899   1.493   5.936   3.665   5.729  10.753   5.782  13.597   5.469
  15.999   5.787  22.111   5.677  27.101   5.895  72.759   5.752  81.668   5.387
   97.68   5.404 107.646   5.059 114.328   5.106 117.751   4.884  131.02   4.883
 136.638   4.638 142.472   4.952 143.972   4.803  149.99   4.941 153.947   4.722
 162.094   4.709 163.907   4.531  171.35   4.675 175.248   4.408 178.077   4.348
 179.957   4.487 183.735   4.249 186.563   4.294 191.434   4.696 195.116   4.377
Lateral Weir Centerline= 6
589116.6558663564873612.98628946589101.7265952244873595.39107705
589066.0029821584873564.73275241589055.0726229374873552.46942255
589006.019303503 4873521.8110979588968.1629374194873488.22023785
LW Div RC= 0 ,False,,

Type RM Length L Ch R = 6 ,55.1    ,,,
Lateral Weir Pos= 3
Lateral Weir End=                ,                ,        ,north_01
Lateral Weir TW Multiple XS=0
Lateral Weir WD=1
Lateral Weir Coef=1.1
LW OverFlow Method 2D=0
LW OverFlow Use Velocity Into 2D=0
Lateral Weir WSCriteria=-1
Lateral Weir Flap Gates= 0
Lateral Weir Hagers EQN= 0 ,,,,,
Lateral Weir SS=0.05,0.05,
Lateral Weir Type= 0
Lateral Weir Connection Pos and Dist= 3 ,
Lateral Weir SE= 30
       0    4.93   6.165   5.091   15.95   3.855  20.914   4.828  23.396   4.899
  27.541   4.491  30.843   4.883  33.264   4.709  35.807   5.062  41.865    4.93
  50.606   5.319  54.813    4.87  57.682   5.258  72.243   5.355  82.448   5.244
  86.454   4.939  96.004   5.189 100.751    4.82  102.72   5.109   117.9   4.776
 134.369   5.128 143.581   4.701  145.75    4.88 159.275   4.607 162.107   4.782
 163.539   4.586 172.532   4.792 179.162   4.215  184.01   4.765 186.802   4.586
Lateral Weir Centerline= 6
589047.3413932434873667.63808557589024.4142982914873636.44657267
 588998.288073814873598.32361245588980.6928614044873574.59673512
588952.967072159 4873538.3399338588935.9050480094873517.81218599
LW Div RC= 0 ,False,,

Type RM Length L Ch R = 1 ,55      ,20,20,20
XS GIS Cut Line= 6
      589118.576      4873594.73        589105.2     4873604.776
       589078.48     4873624.841      589077.824     4873625.335
       589076.74     4873626.148      589029.312     4873661.766
#Sta/Elev= 30
       0   2.601   5.704    2.96  10.166    5.56  14.049   5.545  16.728   4.557
   20.09   4.022  37.328   3.371  46.153   3.317  50.965   3.508   52.32    3.35
  55.027   2.701  57.285   2.617  58.473   2.132  58.985   2.095  60.842    .787
   78.88    .533   79.26    .985   81.13   2.464  82.589   3.141  92.222    3.54
  95.828   3.302  97.848   4.046  98.313   4.446 100.166   5.322 101.108   5.332
 102.041   5.286 103.421   4.551 106.046   2.558  106.23   2.108 111.633   2.082
#Mann= 3 ,0,0
       0    .035       0   52.32    .035       0  82.589    .035       0
Levee=-1,14.0494,8.532255,-1,100.166,8.532255,,
Bank Sta=52.32,82.589
XS Rating Curve= 0 ,0
Exp/Cntr=0.3,0.1

Type RM Length L Ch R = 1 ,54      ,20,20,20
XS GIS Cut Line= 6
      589103.895     4873580.744      589094.534     4873587.773
      589092.008     4873589.671      589089.534     4873591.528
      589049.833     4873621.344      589018.035     4873645.223
#Sta/Elev= 30
       0    2.54   5.145   2.664   7.749   4.297   9.081   5.402  12.055   5.504
  13.489   5.458  14.866   4.936  16.725   4.545  18.178    3.92  36.565   3.228
  40.846   3.171  46.873   3.424  48.835   3.337  50.988   2.793  53.557    2.35
  55.301    1.31  56.004    .714   72.32     .49  74.211     .66  76.135   2.475
  77.828   3.222  88.396    3.66  90.608   3.628  91.868   3.389  96.641   5.111
  98.103   5.116  98.583       5 101.092   3.205 101.719   1.967 107.376   1.947
#Mann= 3 ,0,0
       0    .035       0  50.988    .035       0  77.828    .035       0
Levee=-1,13.4888,8.450597,-1,96.64143,8.450597,,
Bank Sta=50.988,77.828
XS Rating Curve= 0 ,0
Exp/Cntr=0.3,0.1

Type RM Length L Ch R = 1 ,53      ,20,20,20
XS GIS Cut Line= 6
      589087.083     4873568.358      589068.318     4873582.449
      589059.928     4873588.751      589058.968     4873589.471
      589051.796     4873594.858      589007.293     4873628.278
#Sta/Elev= 30
       0   2.429   3.898   2.411   7.522   5.404   8.464   5.705  12.424   5.579
  12.535   5.391  16.111   3.691  16.769   3.589    26.8   3.414   35.16   3.076
  43.191   3.304   44.13   3.019  47.694    .823    48.6    .508  49.264    .501
  67.566    .519   68.17    .612   68.62   1.218  70.237   2.576  70.755    3.16
  71.338   3.213  71.637   3.383  73.671   3.546  81.704   3.838  84.805   3.744
  86.912   4.143   88.68   5.074    91.3    5.16  94.535   1.953  99.784   1.905
#Mann= 3 ,0,0
       0    .035       0   44.13    .035       0  70.755    .035       0
Levee=-1,12.424,8.368938,-1,89.14503,8.368938,,
Bank Sta=44.13,70.755
XS Rating Curve= 0 ,0
Exp/Cntr=0.3,0.1

Type RM Length L Ch R = 1 ,52      ,20,20,20
XS GIS Cut Line= 6
      589071.752     4873555.123      589065.549     4873559.744
      589063.735     4873561.095      589063.704     4873561.117
       589048.45     4873572.481      588995.915     4873611.613
#Sta/Elev= 30
       0   2.282   3.897   2.292   7.069   5.047    8.65   5.581  12.382    5.39
  15.842   3.589  31.672   3.005  38.176    3.32  40.216   3.213  41.878   2.688
  43.932    1.49  45.151    .206  61.779     .56  64.624    .894   65.15   1.404
  67.005   2.583  67.716   3.372   68.71   3.582  75.757    3.97  79.756   3.836
  81.241   4.211  82.357   4.946  83.611   5.119  85.978   5.022  87.366   4.557
  88.082   4.105  89.165   2.706  89.299   2.184  89.441   1.962  94.564    1.87
#Mann= 3 ,0,0
       0    .035       0  40.216    .035       0  67.716    .035       0
Levee=-1,10.03487,8.28728,-1,83.61107,8.28728,,
Bank Sta=40.216,67.716
XS Rating Curve= 0 ,0
Exp/Cntr=0.3,0.1

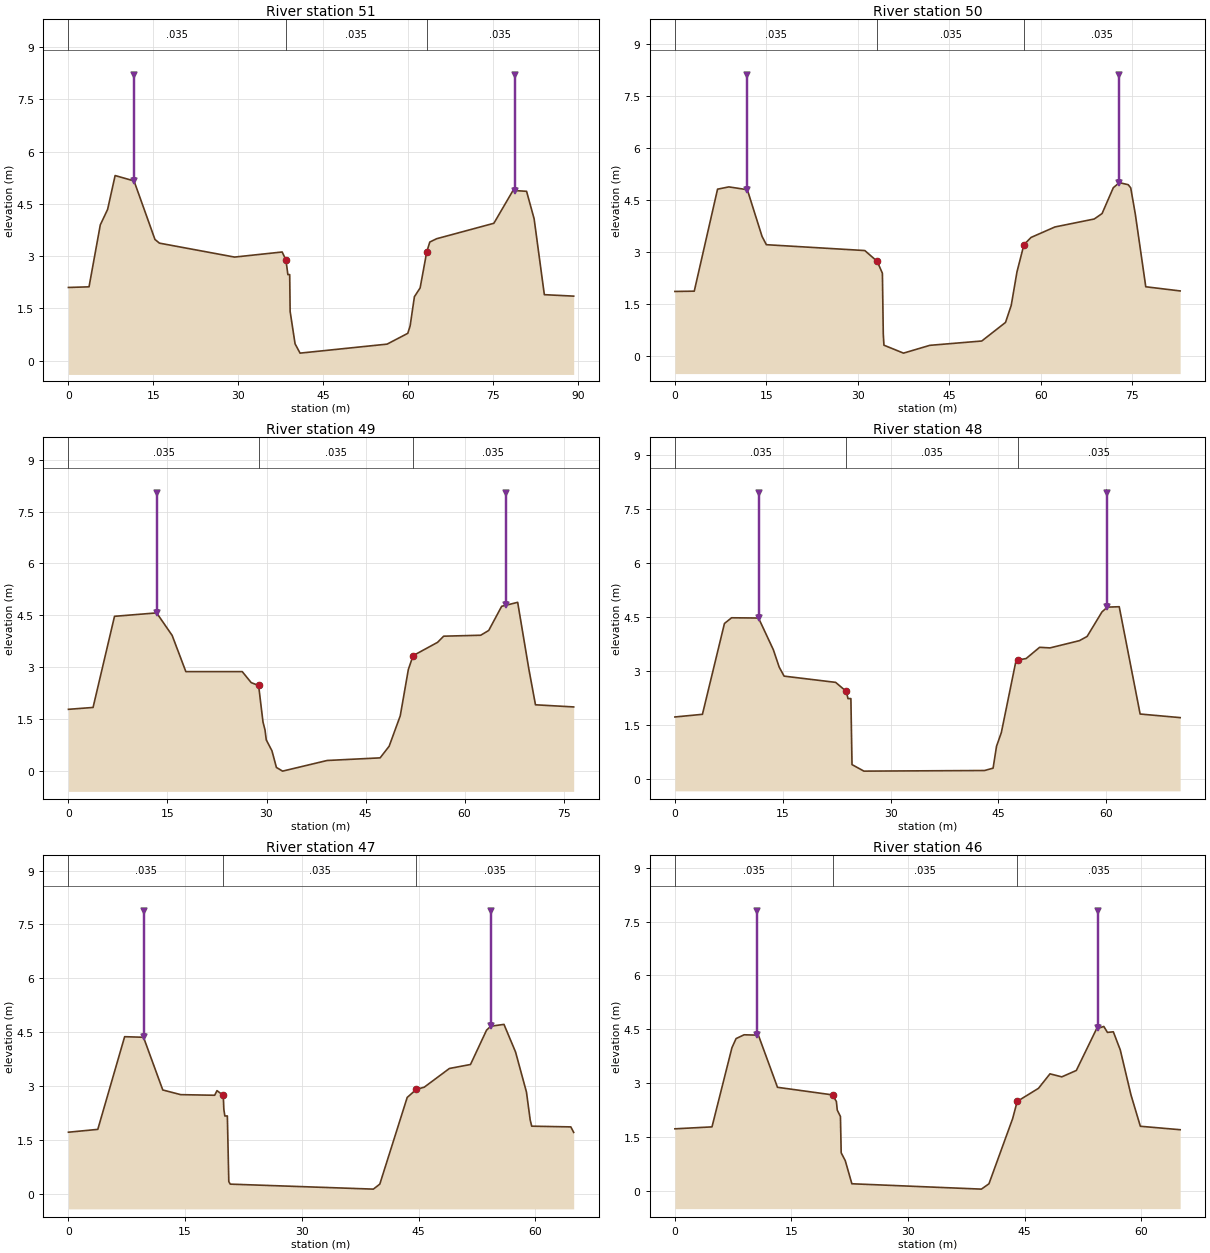
Type RM Length L Ch R = 1 ,51      ,20,20,20
XS GIS Cut Line= 6
      589055.822      4873542.05      589008.887     4873577.011
      589007.357     4873578.152       589006.01     4873579.154
      588992.624     4873589.125      588984.263     4873595.354
#Sta/Elev= 30
       0   2.102   3.639    2.12   5.628   3.898   6.918   4.342   8.247   5.314
  11.584    5.16  15.281    3.48  16.073   3.374  29.345   2.974  37.749    3.12
  38.417   2.887  38.755   2.471  39.076   2.471  39.155   1.414  40.026    .484
  40.906    .217  56.273    .475  59.928    .785  60.341    .995  61.103   1.837
  62.112   2.089  63.284   3.127  63.822   3.406  65.029   3.501  75.133   3.944
  78.521   4.887  80.911   4.862  82.243   4.073  84.048   1.895   89.23   1.853
#Mann= 3 ,0,0
       0    .035       0  38.417    .035       0  63.284    .035       0
Levee=-1,11.58406,8.205622,-1,78.80383,8.205622,,
Bank Sta=38.417,63.284
XS Rating Curve= 0 ,0
Exp/Cntr=0.3,0.1

Type RM Length L Ch R = 1 ,50      ,20,20,20
XS GIS Cut Line= 6
      589035.261     4873526.333      589026.612     4873534.482
      589024.496     4873536.474      589011.585     4873548.638
      589007.379     4873552.599      588974.934     4873583.164
#Sta/Elev= 30
       0   1.869   3.176   1.877   6.997   4.822   8.851   4.888  11.883   4.807
  14.295   3.459  15.003   3.219  31.152    3.05  33.183   2.739  34.039   2.393
  34.183    .642   34.29    .317  37.501    .088   41.82    .313  50.338    .438
  54.232    .974  55.168   1.465  56.115   2.435   57.25   3.218  58.427   3.429
   62.34   3.731  68.789   3.961  70.072   4.118  71.916   4.865  72.913   5.011
  74.365   4.951  74.772    4.86  75.529   4.098  77.241   2.004   82.88   1.884
#Mann= 3 ,0,0
       0    .035       0  33.183    .035       0   57.25    .035       0
Levee=-1,11.88324,8.123963,-1,72.91322,8.123963,,
Bank Sta=33.183,57.25
XS Rating Curve= 0 ,0
Exp/Cntr=0.3,0.1

Type RM Length L Ch R = 1 ,49      ,20,20,20
XS GIS Cut Line= 6
      589018.396     4873514.744      588986.478     4873544.812
      588981.817     4873549.204      588980.802     4873550.159
      588980.261      4873550.67        588962.7     4873567.212
#Sta/Elev= 30
       0   1.776    3.73    1.83   6.979   4.468  13.357   4.567  15.708   3.915
  17.783   2.867   26.32   2.868  27.679   2.549  28.801   2.466  29.469   1.406
  29.775   1.177   29.96    .892  30.822    .576  31.497    .094  32.432   -.013
  39.182    .295  47.204    .371  48.572    .708  50.255   1.589  51.478   2.928
   52.19   3.328  55.906   3.715  56.828   3.893  62.437    3.92  63.649   4.058
  65.611   4.758  68.036   4.873  69.715   2.956  70.732   1.907  76.518   1.845
#Mann= 3 ,0,0
       0    .035       0  28.801    .035       0   52.19    .035       0
Levee=-1,13.35682,8.042305,-1,66.20193,8.042305,,
Bank Sta=28.801,52.19
XS Rating Curve= 0 ,0
Exp/Cntr=0.3,0.1

Type RM Length L Ch R = 1 ,48      ,20,20,20
XS GIS Cut Line= 6
      589001.594     4873503.096      588993.127     4873511.071
      588991.632     4873512.481      588991.037      4873513.04
      588968.787     4873534.002      588950.448     4873551.277
#Sta/Elev= 30
       0   1.731    3.83   1.805   6.891   4.329   7.883   4.488  11.631   4.481
  13.686   3.603  14.503   3.118  15.189   2.866  22.352   2.693   23.84   2.442
  24.069   2.242  24.476   2.242  24.632    .407  26.288    .226  43.072    .243
  44.253    .309  44.727    .916  45.399   1.298  47.389   3.246  47.771   3.315
  48.852   3.356  50.719   3.667  52.167   3.651  56.257   3.852  57.327   3.969
  59.394   4.651  60.143   4.784  61.793   4.795  64.702   1.813  70.266   1.713
#Mann= 3 ,0,0
       0    .035       0   23.84    .035       0  47.771    .035       0
Levee=-1,11.63145,7.960647,-1,60.14287,7.960647,,
Bank Sta=23.84,47.771
XS Rating Curve= 0 ,0
Exp/Cntr=0.3,0.1

Type RM Length L Ch R = 1 ,47      ,20,20,20
XS GIS Cut Line= 6
      588984.998     4873491.056      588971.377     4873504.009
       588971.16     4873504.217       588943.35     4873530.662
      588941.989     4873531.958      588937.939     4873535.808
#Sta/Elev= 30
       0   1.714   3.774   1.793   7.225   4.374   9.652   4.358  12.126    2.89
  14.437    2.76  18.797   2.743  19.097   2.872  19.902   2.739  19.976   2.351
  20.103   2.166  20.427   2.167  20.613    .338    20.8    .268  39.195    .129
  40.022    .269  43.542   2.682  44.703   2.904  45.734   2.968  48.969   3.489
   51.68     3.6  53.742   4.556  54.279   4.665  55.981   4.717  57.473   3.946
  58.872   2.831  59.353   2.053  59.548   1.882  64.574   1.862  64.941   1.709
#Mann= 3 ,0,0
       0    .035       0  19.902    .035       0  44.703    .035       0
Levee=-1,9.651525,7.878988,-1,54.27909,7.878988,,
Bank Sta=19.902,44.703
XS Rating Curve= 0 ,0
Exp/Cntr=0.3,0.1

Type RM Length L Ch R = 1 ,46      ,20,20,20
XS GIS Cut Line= 6
      588972.531     4873475.312      588971.485     4873476.308
      588968.203     4873479.428      588957.474     4873489.632
      588956.031     4873491.003      588925.425     4873520.109
#Sta/Elev= 30
       0   1.739   4.772   1.793   7.339   3.993   7.873   4.247   8.904   4.352
  10.742   4.342  13.199   2.893  20.283   2.682  20.779   2.497   20.89    2.26
  21.299   2.081  21.396   1.072   21.92    .854   22.77    .212  39.434    .063
  40.406    .211  43.455   2.023  44.041   2.501  46.775   2.864  48.257   3.267
  49.779   3.183  51.648   3.361  54.256    4.52  55.183   4.584  55.651   4.419
  56.409   4.435  57.303   3.932  58.682    2.68  59.886    1.81  65.006   1.714
#Mann= 3 ,0,0
       0    .035       0  20.283    .035       0  44.041    .035       0
Levee=-1,10.52294,7.79733,-1,54.40499,7.79733,,
Bank Sta=20.283,44.041
XS Rating Curve= 0 ,0
Exp/Cntr=0.3,0.1

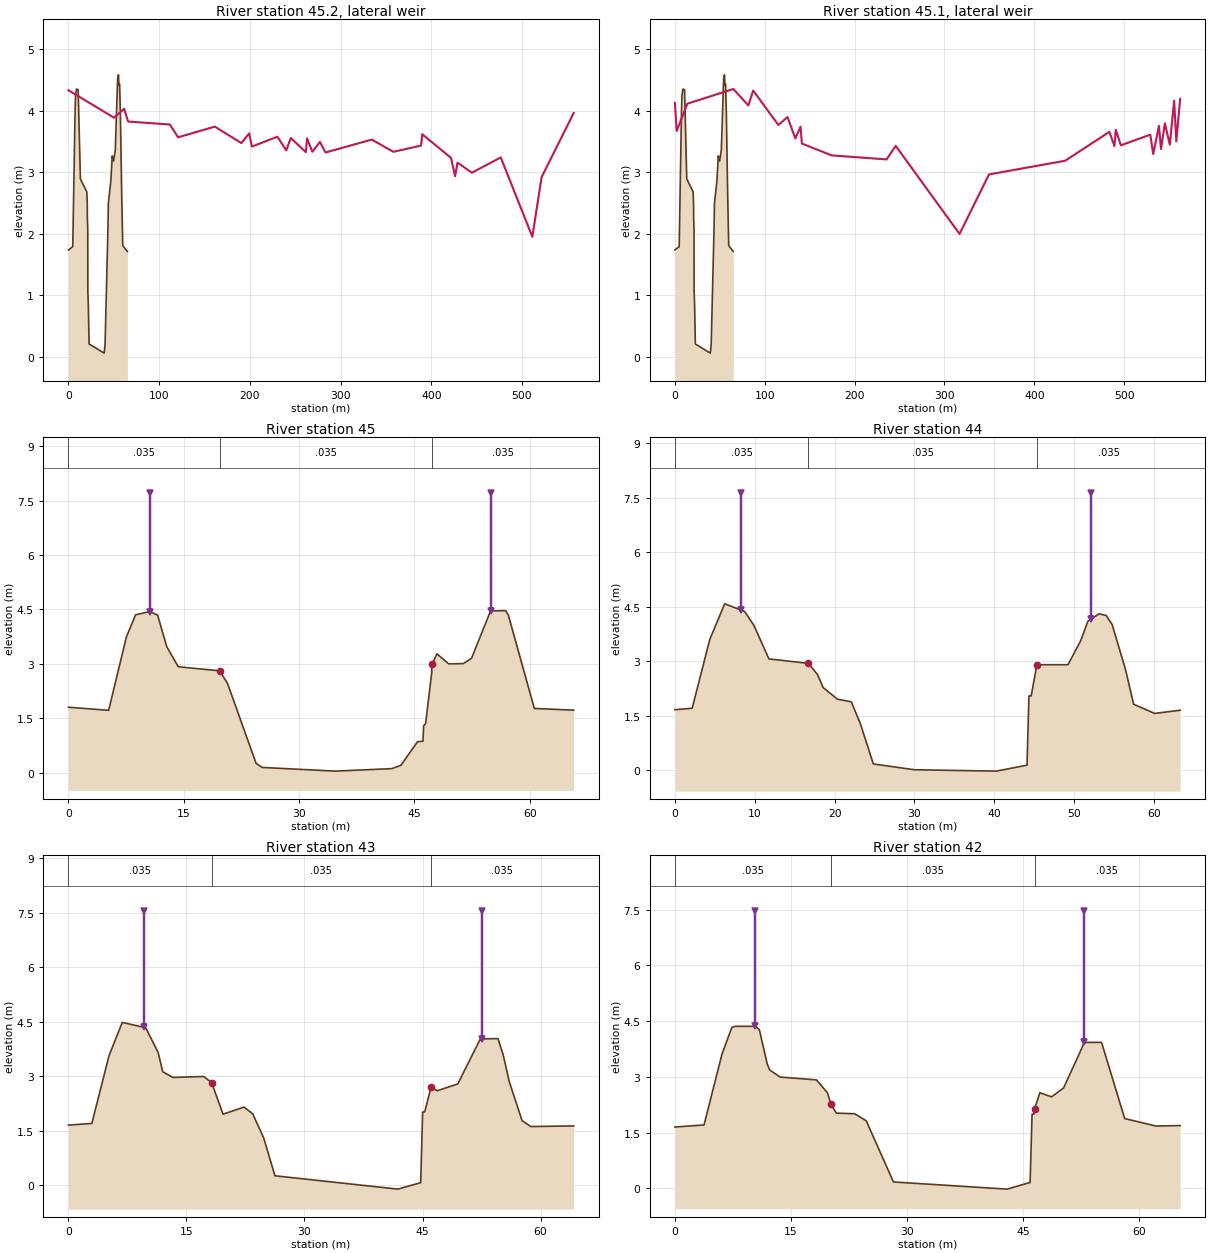
Type RM Length L Ch R = 6 ,45.2    ,,,
Lateral Weir Pos= 0
Lateral Weir End=                ,                ,        ,south_01
Lateral Weir TW Multiple XS=0
Lateral Weir WD=1
Lateral Weir Coef=1.1
LW OverFlow Method 2D=0
LW OverFlow Use Velocity Into 2D=0
Lateral Weir WSCriteria=-1
Lateral Weir Flap Gates= 0
Lateral Weir Hagers EQN= 0 ,,,,,
Lateral Weir SS=0.05,0.05,
Lateral Weir Type= 0
Lateral Weir Connection Pos and Dist= 3 ,
Lateral Weir SE= 30
       0   4.334  50.187   3.888  61.394   4.031  65.807   3.825 111.783   3.777
 120.896   3.569 161.428   3.743 190.627   3.475 199.259   3.633 202.242   3.418
 230.346   3.579 240.117   3.357 245.164   3.558 261.722   3.328 263.011   3.551
 268.923   3.334 277.288   3.494 283.326   3.322 334.396   3.532 358.222   3.333
 388.758   3.435 390.036   3.619 421.722   3.235 426.225   2.936 428.973   3.157
 444.828   2.994 476.566   3.242  511.41   1.954 521.637   2.922 556.987   3.964
Lateral Weir Centerline= 6
588958.6341620314873476.46290952588907.7509411044873414.67614126
588826.5800886724873281.00672755 588676.353436414873061.32044037
588671.5074153694873038.70567551 588652.931001384873013.66790014
LW Div RC= 0 ,False,,

Type RM Length L Ch R = 6 ,45.1    ,,,
Lateral Weir Pos= 3
Lateral Weir End=                ,                ,        ,north_01
Lateral Weir TW Multiple XS=0
Lateral Weir WD=1
Lateral Weir Coef=1.1
LW OverFlow Method 2D=0
LW OverFlow Use Velocity Into 2D=0
Lateral Weir WSCriteria=-1
Lateral Weir Flap Gates= 0
Lateral Weir Hagers EQN= 0 ,,,,,
Lateral Weir SS=0.05,0.05,
Lateral Weir Type= 0
Lateral Weir Connection Pos and Dist= 3 ,
Lateral Weir SE= 30
       0   4.126   1.965   3.672  13.868   4.115  65.039   4.354  81.737   4.086
  87.139   4.329 115.107   3.769 125.286   3.898 134.009   3.551 139.824   3.741
 141.278   3.467 174.504   3.275 235.578    3.21 245.703    3.43 316.742   1.999
 349.516   2.966 434.247   3.188 483.513   3.658 489.044   3.427 490.659   3.689
 496.247   3.439 528.983   3.612 532.259   3.298 538.637   3.754 540.902   3.379
 545.224   3.796 550.705    3.45 555.532   4.164 557.945   3.504 562.231    4.19
Lateral Weir Centerline= 6
588927.0108486874873506.47231397588868.9343304234873435.59927473
588816.1076669174873348.64855529588754.2578155454873253.00276392
588733.0943385514873215.10537488588615.6288383334873039.23524048
LW Div RC= 0 ,False,,

Type RM Length L Ch R = 1 ,45      ,20,20,20
XS GIS Cut Line= 6
      588960.678     4873458.985      588946.436     4873472.529
      588946.111     4873472.837      588942.988     4873475.808
      588942.417      4873476.35       588913.05     4873504.278
#Sta/Elev= 30
       0   1.805   5.233   1.719   7.542   3.744   8.737   4.353   10.59   4.442
  11.604   4.344  12.789   3.476  14.284   2.921  19.654   2.808  20.683   2.469
  24.412    .257  25.199    .145   34.68    .043  42.083    .112  43.254    .205
  45.414    .855  46.119    .868   46.21   1.296  46.461    1.35  47.256   2.751
  47.295   2.983  47.936   3.277  49.465   3.001  51.361   3.007  52.438   3.153
  54.914   4.459   56.88   4.467  57.232   4.342  60.605   1.771  65.726   1.724
#Mann= 3 ,0,0
       0    .035       0  19.654    .035       0  47.295    .035       0
Levee=-1,10.59014,7.715672,-1,54.91358,7.715672,,
Bank Sta=19.654,47.295
XS Rating Curve= 0 ,0
Exp/Cntr=0.3,0.1

Type RM Length L Ch R = 1 ,44      ,20,20,20
XS GIS Cut Line= 6
      588946.999     4873444.393      588941.012     4873450.088
      588940.676     4873450.406      588929.189     4873461.331
       588928.99     4873461.519      588901.147     4873487.998
#Sta/Elev= 30
       0   1.662   2.168   1.703   4.373     3.6   6.239   4.579   8.726   4.369
   9.895   3.986  11.777   3.061  16.711   2.938  17.854   2.634  18.562   2.274
  20.353   1.953  22.088    1.88  23.218   1.284  24.852    .169  29.971    .009
  40.253   -.029  44.099    .135  44.339   2.042   44.62   2.042  45.334   2.901
  49.231   2.901  50.827   3.565  51.716   4.096  53.115   4.303   54.01   4.257
  54.762   4.007  56.436   2.767  57.448   1.814  60.079    1.56  63.276   1.648
#Mann= 3 ,0,0
       0    .035       0  16.711    .035       0  45.334    .035       0
Levee=-1,8.263002,7.634013,-1,52.15149,7.634013,,
Bank Sta=16.711,45.334
XS Rating Curve= 0 ,0
Exp/Cntr=0.3,0.1

Type RM Length L Ch R = 1 ,43      ,20,20,20
XS GIS Cut Line= 6
       588939.91     4873432.911      588902.332     4873457.215
      588901.896     4873457.498      588895.733     4873461.483
      588894.071     4873462.559      588885.994     4873467.783
#Sta/Elev= 30
       0   1.656   2.976   1.703   5.156   3.564   6.843   4.482   9.824   4.335
  11.399   3.656  11.985   3.125  13.258   2.968  17.195   2.994  18.198   2.827
  19.651   1.957  22.321   2.152   23.42   1.967  24.821     1.3  26.247    .262
  41.868   -.105  44.753    .072  44.768    .085  45.015   2.018  45.272   2.018
  46.096   2.704  46.876   2.602  49.479   2.789  52.342   4.027  54.591   4.037
  55.266   3.576  56.025   2.853   57.65   1.781  58.748   1.617  64.211   1.634
#Mann= 3 ,0,0
       0    .035       0  18.198    .035       0  46.096    .035       0
Levee=-1,9.567843,7.552355,-1,52.61149,7.552355,,
Bank Sta=18.198,46.096
XS Rating Curve= 0 ,0
Exp/Cntr=0.3,0.1

Type RM Length L Ch R = 1 ,42      ,20,20,20
XS GIS Cut Line= 6
      588929.048     4873416.117      588919.019     4873422.605
      588918.944     4873422.652      588918.751     4873422.778
      588913.228     4873426.349       588874.18     4873451.605
#Sta/Elev= 30
       0   1.648   3.767   1.703    6.09   3.611   7.376   4.334   7.824    4.36
  10.421    4.36  10.924   4.269  11.945   3.344  12.264   3.184  13.607   2.994
  18.307   2.917  19.724   2.571  20.197   2.257  20.886   2.022  23.257   2.005
  24.745   1.815  28.268    .168  42.968   -.025  45.939    .155  46.193   1.995
  46.432   1.995  46.512   2.135  47.205   2.571  48.719   2.461  50.272     2.7
  52.966   3.927  55.177   3.928  58.173   1.876  62.222   1.674  65.345   1.687
#Mann= 3 ,0,0
       0    .035       0  20.197    .035       0  46.512    .035       0
Levee=-1,10.42104,7.470696,-1,52.96579,7.470696,,
Bank Sta=20.197,46.512
XS Rating Curve= 0 ,0
Exp/Cntr=0.3,0.1