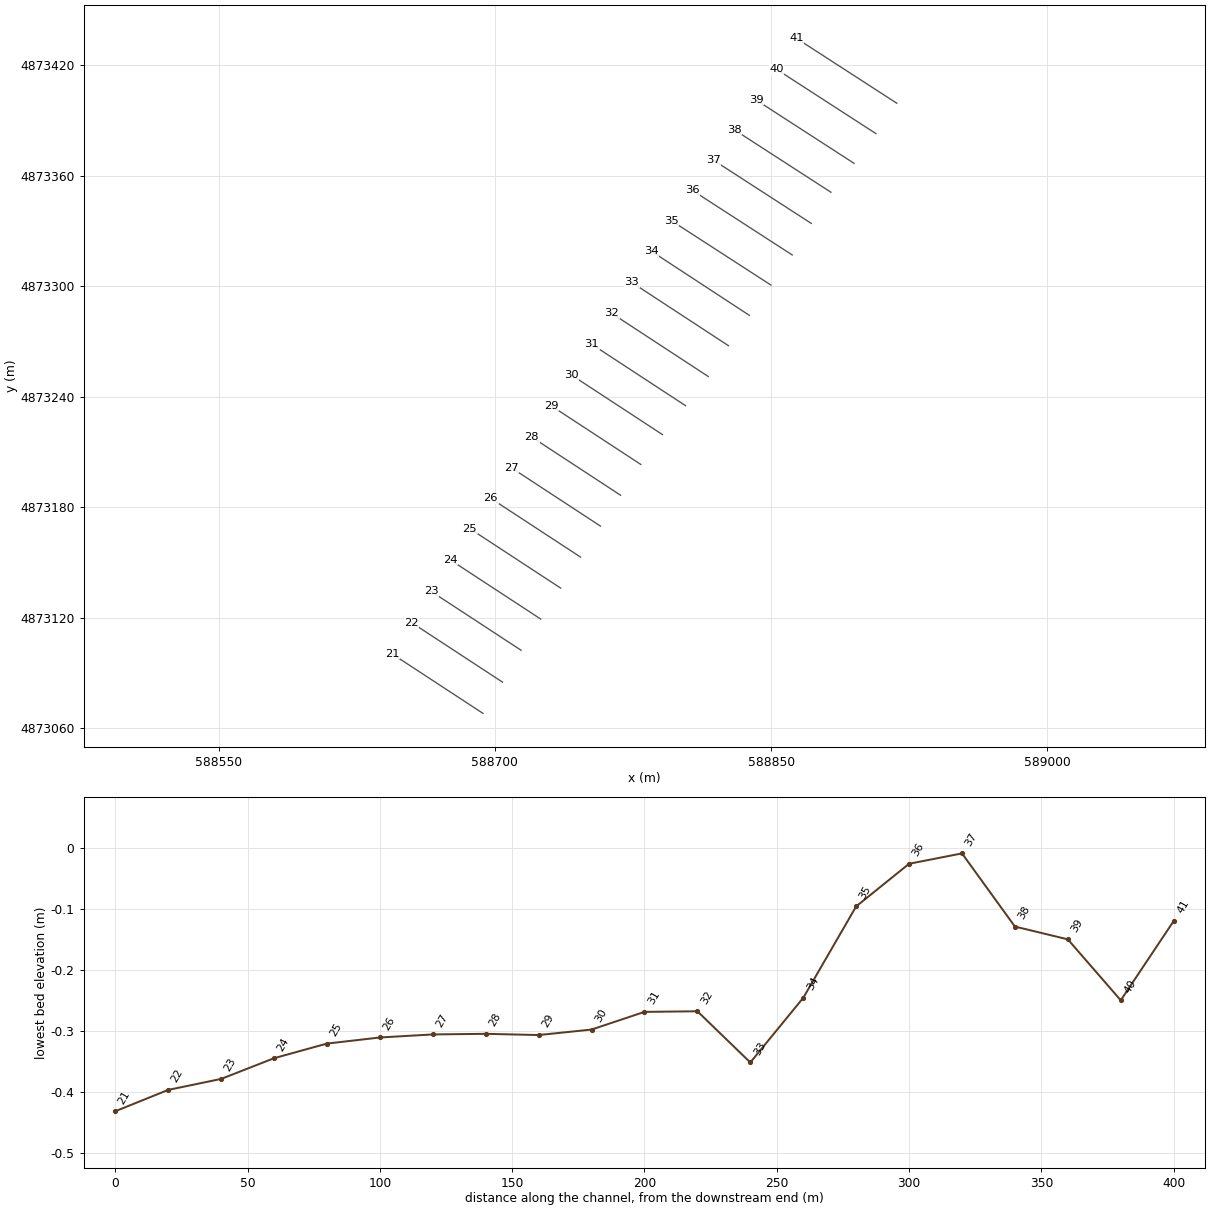
HEC-RAS study massa.prj: massa

--- massa.g05 (geometry) --- (continued)

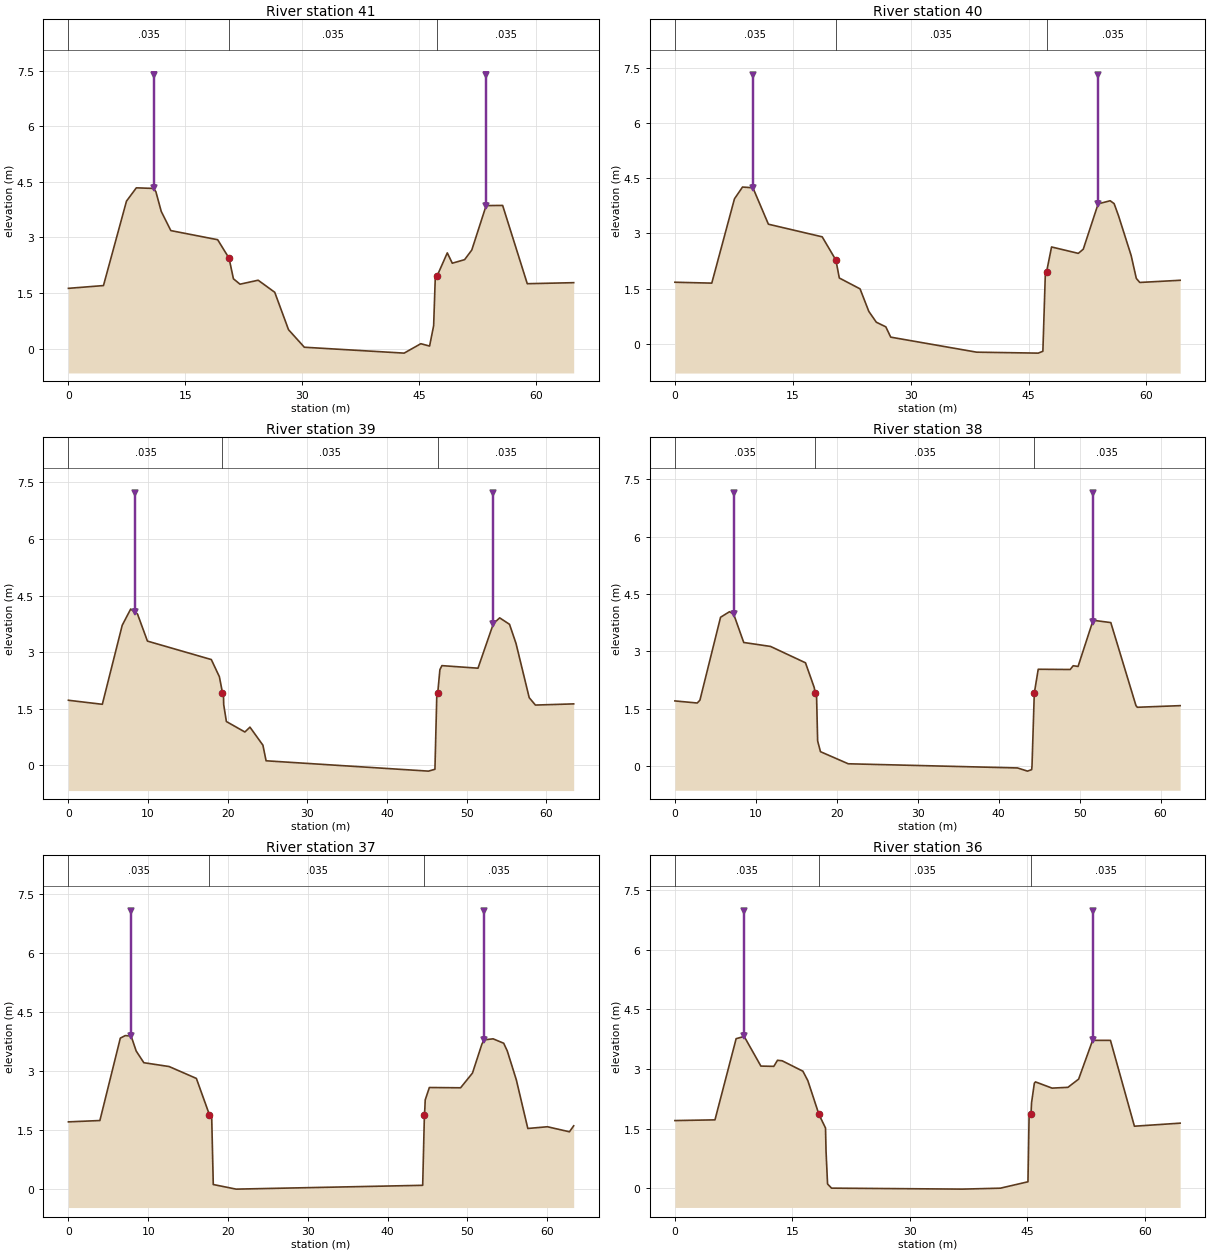
Type RM Length L Ch R = 1 ,41      ,20,20,20
BEGIN DESCRIPTION:
186 pr. 1810.0
END DESCRIPTION:
XS GIS Cut Line= 6
      588918.187     4873399.324      588880.384     4873423.773
      588878.421     4873425.044      588877.341     4873425.741
      588875.475     4873426.949      588863.715     4873434.555
#Sta/Elev= 30
       0   1.628   4.499   1.703   7.454   3.981   8.719    4.34  10.925   4.324
  11.227   4.237  11.916   3.704  13.149   3.186  19.161    2.94  20.623   2.442
  21.184   1.886  22.031    1.74   24.36   1.847  26.488   1.522   28.26    .512
   30.29    .039  43.101    -.12  45.243    .134  46.371    .071  46.892    .619
  47.111   1.973  47.359   1.973  48.644   2.585  49.286   2.306  50.867   2.402
  51.789   2.662  53.632   3.861  55.751   3.865  58.913   1.753  64.872   1.781
#Mann= 3 ,0,0
       0    .035       0  20.623    .035       0  47.359    .035       0
Levee=-1,10.92533,7.389038,-1,53.63198,7.389038,,
Bank Sta=20.623,47.359
XS Rating Curve= 0 ,0
Exp/Cntr=0.3,0.1

Type RM Length L Ch R = 1 ,40      ,20,20,20
XS GIS Cut Line= 6
      588906.843     4873382.842      588901.556     4873386.262
      588900.478     4873386.958      588899.619     4873387.515
      588896.853     4873389.304      588852.858     4873417.758
#Sta/Elev= 30
       0   1.675   4.693   1.651    7.58    3.94   8.604    4.26   9.929    4.24
  11.898   3.251  18.744   2.908  20.488   2.276  20.921    1.79  23.562   1.495
  24.672    .885  25.628     .59  26.838    .464  27.463    .184  38.393   -.224
  46.238    -.25  46.825   -.199  47.144   1.951  47.289   1.951  47.928   2.633
  51.331   2.459  51.964   2.572  53.856   3.803   55.39   3.888  55.892   3.809
   56.45    3.48  58.054   2.403  58.714   1.779  59.153   1.669  64.292   1.728
#Mann= 3 ,0,0
       0    .035       0  20.488    .035       0  47.289    .035       0
Levee=-1,9.92871,7.30738,-1,53.85605,7.30738,,
Bank Sta=20.488,47.289
XS Rating Curve= 0 ,0
Exp/Cntr=0.3,0.1

Type RM Length L Ch R = 1 ,39      ,20,20,20
XS GIS Cut Line= 6
      588894.949     4873366.716      588889.126     4873370.483
      588874.263     4873380.096      588873.488     4873380.596
      588862.446     4873387.739      588841.702     4873401.155
#Sta/Elev= 30
       0   1.728   4.254   1.621   6.752   3.716   7.813   4.145   8.671   4.013
   9.917   3.296  17.933   2.807  18.945   2.353  19.334   1.928  19.455   1.928
  19.488   1.613  19.826   1.164  22.148    .887  22.784   1.016  24.411    .537
  24.808    .124  45.185    -.15      46   -.101  46.242   1.928  46.354   1.928
  46.621   2.537  46.874   2.646  51.403   2.578   53.34   3.762  54.128   3.912
   55.36   3.741  56.176   3.234  57.833   1.797   58.61   1.601  63.414   1.632
#Mann= 3 ,0,0
       0    .035       0  19.334    .035       0  46.354    .035       0
Levee=-1,8.383163,7.225721,-1,53.33959,7.225721,,
Bank Sta=19.334,46.354
XS Rating Curve= 0 ,0
Exp/Cntr=0.3,0.1

Type RM Length L Ch R = 1 ,38      ,20,20,20
XS GIS Cut Line= 6
      588882.435     4873350.992      588873.343     4873356.871
      588868.887     4873359.753      588867.884     4873360.403
      588866.933     4873361.017       588830.02     4873384.892
#Sta/Elev= 30
       0   1.706   2.758   1.651   3.092   1.725   5.641   3.892   6.744   4.037
   7.268    3.97   8.504   3.233  11.813    3.13  16.134   2.702  17.217   2.054
  17.329   1.906  17.494   1.906  17.636     .66  17.987    .379  21.416    .063
  42.329   -.046  43.565   -.129  44.079   -.089   44.12    .009  44.401   1.906
  44.888   2.533  48.835   2.527  49.208   2.625  49.811   2.607  51.611   3.777
  51.782    3.81  53.855   3.753  56.964   1.583  57.134    1.54  62.422   1.582
#Mann= 3 ,0,0
       0    .035       0  17.329    .035       0  44.401    .035       0
Levee=-1,7.268111,7.144063,-1,51.61072,7.144063,,
Bank Sta=17.329,44.401
XS Rating Curve= 0 ,0
Exp/Cntr=0.3,0.1

Type RM Length L Ch R = 1 ,37      ,20,20,20
XS GIS Cut Line= 6
      588871.768     4873334.072      588829.251     4873361.571
      588825.967     4873363.694      588824.636     4873364.556
      588821.366      4873366.67      588818.603     4873368.458
#Sta/Elev= 30
       0     1.7   3.942   1.734   6.504   3.828   7.116   3.892   7.856   3.882
    8.49   3.501    9.45   3.203  12.617   3.106  16.033   2.804  17.664   1.884
  17.947   1.884  18.151    .108  21.016   -.009  44.394    .088   44.61   1.884
  44.664    2.03   44.71   2.258   45.23   2.573  49.146   2.566  50.635   2.941
  51.816   3.677  52.101   3.784  53.217    3.81  54.545   3.698  54.997   3.501
  56.131   2.766  57.568   1.532  60.025   1.576  62.783   1.448  63.316     1.6
#Mann= 3 ,0,0
       0    .035       0  17.664    .035       0   44.61    .035       0
Levee=-1,7.85616,7.062405,-1,52.10083,7.062405,,
Bank Sta=17.664,44.61
XS Rating Curve= 0 ,0
Exp/Cntr=0.3,0.1

Type RM Length L Ch R = 1 ,36      ,20,20,20
XS GIS Cut Line= 6
      588861.409     4873316.953       588852.65     4873322.619
      588847.156     4873326.171      588845.262     4873327.396
      588845.205     4873327.434      588807.245     4873351.985
#Sta/Elev= 30
       0     1.7   5.116   1.718    7.82   3.762   8.847   3.818  10.979   3.072
  12.628   3.065  13.101   3.218  13.697   3.205  16.342   2.943  16.974   2.705
  18.391   1.855   19.23   1.513  19.298    .924  19.491    .104  19.998   -.001
  36.721   -.026  41.559   -.002  45.077    .159  45.225   1.862  45.464   1.862
  45.537   2.153  45.893   2.642  46.035   2.674  48.154   2.517   50.18   2.537
  51.546   2.744   53.33    3.72  55.609   3.719  58.667   1.558  64.506   1.635
#Mann= 3 ,0,0
       0    .035       0  18.391    .035       0  45.464    .035       0
Levee=-1,8.847491,6.980746,-1,53.33017,6.980746,,
Bank Sta=18.391,45.464
XS Rating Curve= 0 ,0
Exp/Cntr=0.3,0.1

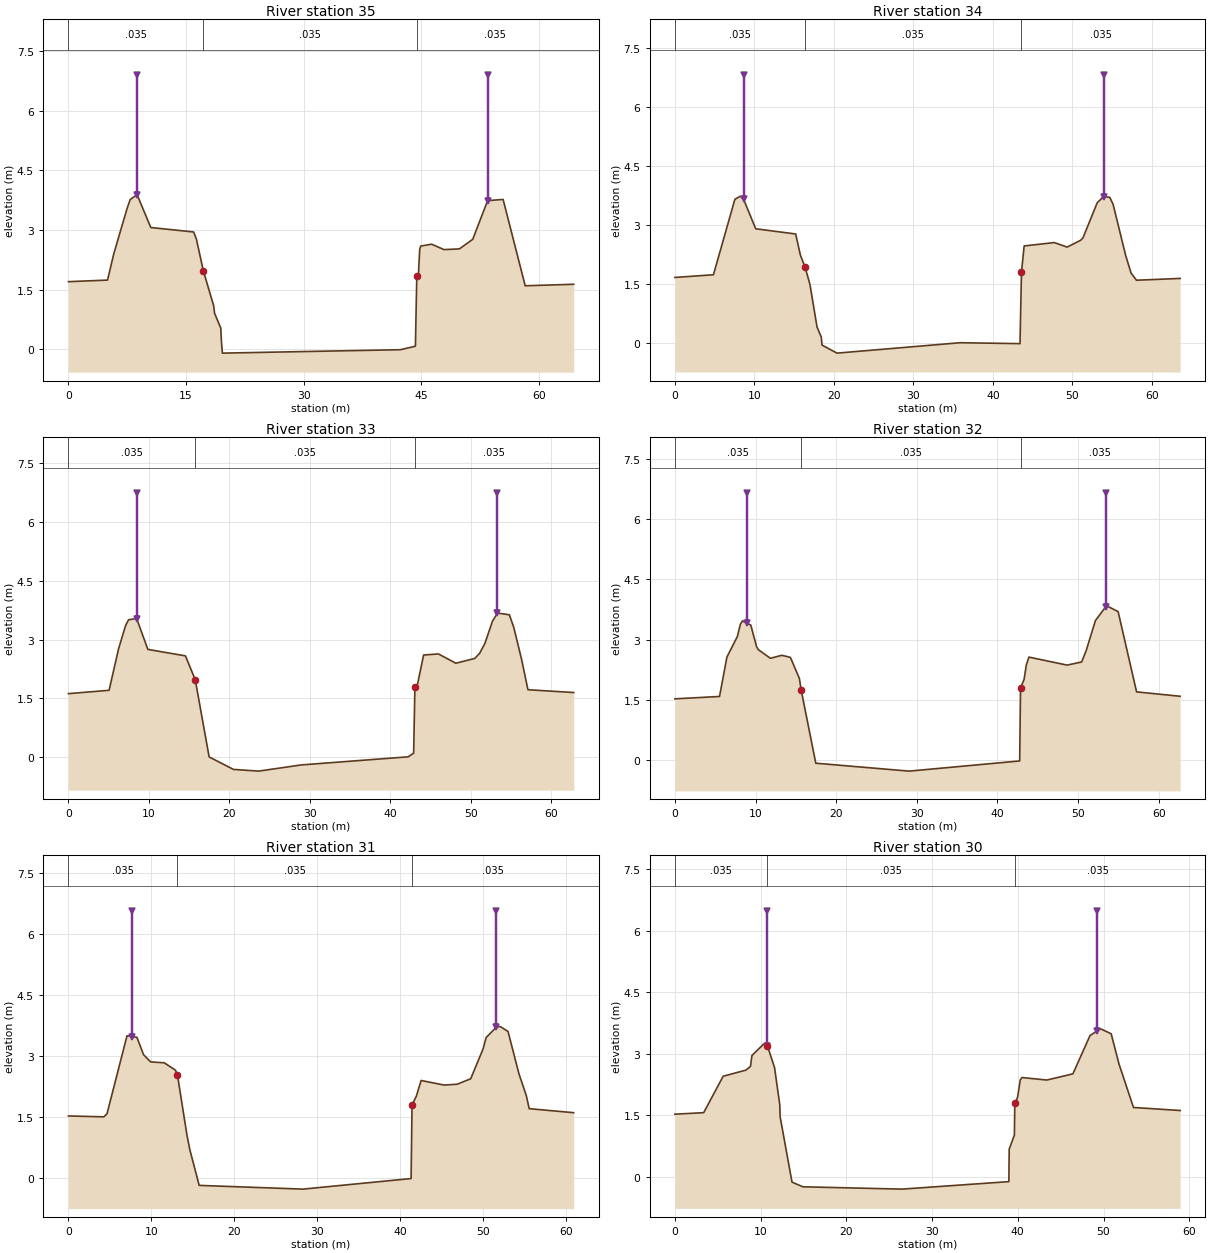
Type RM Length L Ch R = 1 ,35      ,20,20,20
XS GIS Cut Line= 6
      588849.818     4873300.631       588814.29     4873323.609
      588812.526      4873324.75      588812.214     4873324.953
      588812.098     4873325.027      588795.732     4873335.613
#Sta/Elev= 30
       0     1.7   4.986    1.74   5.782   2.401    7.49   3.548   7.876   3.764
   8.753   3.886  10.505   3.061  15.964   2.949  16.307   2.776  17.196   1.976
  18.514   1.097  18.634    .905  19.426    .532  19.502    .205  19.628   -.096
  42.311    -.01  44.207    .076  44.237    .092  44.412    1.84   44.61    1.84
  44.784   2.513  44.922   2.595  46.302   2.642  47.884   2.506  49.845   2.524
  51.542   2.764  53.442   3.737  55.417   3.767  58.232   1.597  64.413   1.635
#Mann= 3 ,0,0
       0    .035       0  17.196    .035       0  44.412    .035       0
Levee=-1,8.752622,6.899088,-1,53.44221,6.899088,,
Bank Sta=17.196,44.412
XS Rating Curve= 0 ,0
Exp/Cntr=0.3,0.1

Type RM Length L Ch R = 1 ,34      ,20,20,20
XS GIS Cut Line= 6
      588838.119     4873284.177      588831.421     4873288.562
      588828.947     4873290.183      588823.227     4873293.927
       588823.16     4873293.972      588784.947      4873318.99
#Sta/Elev= 30
       0   1.675   4.849   1.743   7.545   3.658   8.228   3.735   8.642   3.659
  10.165    2.91  15.191   2.778   15.79   2.238  16.369   1.941  16.985   1.501
  17.881    .415  18.416    .162  18.502   -.041   20.39   -.246  35.875    .018
   43.41   -.005  43.597   1.818  43.932   2.474   47.72    2.56  49.338   2.445
  51.054    2.62  51.332    2.68  53.126   3.571   53.93   3.728  54.709   3.707
  55.125   3.528  56.688   2.244  57.378   1.788  58.059   1.604  63.555    1.65
#Mann= 3 ,0,0
       0    .035       0  16.369    .035       0  43.597    .035       0
Levee=-1,8.641974,6.81743,-1,53.92955,6.81743,,
Bank Sta=16.369,43.597
XS Rating Curve= 0 ,0
Exp/Cntr=0.3,0.1

Type RM Length L Ch R = 1 ,33      ,20,20,20
XS GIS Cut Line= 6
      588826.779     4873267.697      588818.687     4873272.994
      588815.084     4873275.354      588812.153     4873277.272
       588789.86     4873291.869      588774.263      4873302.08
#Sta/Elev= 30
       0   1.621   5.051   1.707    6.23   2.763   7.108   3.359   7.473   3.503
   8.473   3.535    9.87   2.748   14.54   2.583  15.758   1.973  17.481     .01
  20.499   -.308   23.62   -.352  28.931   -.194  42.206    .012  42.888    .105
  43.046     1.8  43.374   1.866  44.128   2.605  45.959   2.633  48.134   2.396
   50.48   2.518  51.077   2.646  51.745   2.903   52.68   3.466  53.304   3.673
  54.781    3.63  55.334   3.305  56.304   2.488  57.089   1.721   62.77    1.65
#Mann= 3 ,0,0
       0    .035       0  15.758    .035       0  43.046    .035       0
Levee=-1,8.473063,6.735771,-1,53.3041,6.735771,,
Bank Sta=15.758,43.046
XS Rating Curve= 0 ,0
Exp/Cntr=0.3,0.1

Type RM Length L Ch R = 1 ,32      ,20,20,20
XS GIS Cut Line= 6
      588815.833     4873250.958      588805.924     4873257.445
       588803.85     4873258.804      588801.392     4873260.412
      588801.215     4873260.529      588763.409     4873285.281
#Sta/Elev= 30
       0    1.53   5.535   1.589    6.45   2.568   7.751   3.081   8.123   3.387
   8.383   3.468   9.416   3.363  10.129   2.828  10.339   2.755  11.844   2.539
  13.265   2.613  14.323   2.562  15.438   2.037  15.655   1.756  17.473   -.071
   29.05   -.268  42.759   -.015  42.865     1.8  43.306   2.012  43.576   2.366
  43.903   2.568  48.641   2.369  50.444   2.447  51.006   2.729  52.152   3.476
   53.41   3.814  53.766   3.822  54.968     3.7  57.258   1.703  62.661   1.594
#Mann= 3 ,0,0
       0    .035       0  15.655    .035       0  42.865    .035       0
Levee=-1,9.002547,6.654113,-1,53.41034,6.654113,,
Bank Sta=15.655,42.865
XS Rating Curve= 0 ,0
Exp/Cntr=0.3,0.1

Type RM Length L Ch R = 1 ,31      ,20,20,20
XS GIS Cut Line= 6
      588803.499     4873235.128      588779.868     4873250.599
      588769.203     4873257.583      588765.633     4873259.919
      588759.191     4873264.138      588752.573      4873268.47
#Sta/Elev= 30
       0    1.53   4.267   1.508   4.646   1.583   7.057     3.5   8.251   3.463
   9.055   3.034   9.903   2.859  11.547   2.836  12.892   2.656  13.128   2.545
  14.286   1.053  14.625    .702  15.753   -.177  28.245   -.269  41.284   -.009
  41.394     1.8  41.917   2.018  42.492   2.402   45.26   2.289   46.84    2.31
  48.463   2.444  49.951   3.176  50.328   3.459  51.564   3.715  52.037   3.726
   52.96   3.607  54.279   2.565  55.159   2.033  55.512   1.709   60.87    1.61
#Mann= 3 ,0,0
       0    .035       0  13.128    .035       0  41.394    .035       0
Levee=-1,7.713098,6.572454,-1,51.56395,6.572454,,
Bank Sta=13.128,41.394
XS Rating Curve= 0 ,0
Exp/Cntr=0.3,0.1

Type RM Length L Ch R = 1 ,30      ,20,20,20
XS GIS Cut Line= 6
      588790.919     4873219.459      588758.291     4873240.822
      588757.785     4873241.152      588757.472     4873241.358
      588755.604      4873242.58      588741.606     4873251.745
#Sta/Elev= 30
       0    1.53    3.36   1.567   5.628   2.456   8.271   2.604   8.816   2.694
   8.988   2.962  10.356   3.241  10.784   3.203  11.625   2.668  12.233   1.765
  12.279   1.464  13.661   -.127  14.931   -.241  26.494   -.298  38.958   -.115
      39    .678  39.604    1.02  39.654     1.8  39.702     1.8  39.978   1.947
  40.289   2.365  40.491   2.424  43.391   2.363   46.43   2.514   48.43   3.449
  49.657   3.614  50.898   3.491  51.802   2.759  53.495   1.694  58.942    1.62
#Mann= 3 ,0,0
       0    .035       0  10.784    .035       0  39.702    .035       0
Levee=-1,10.78374,6.490796,-1,49.20194,6.490796,,
Bank Sta=10.784,39.702
XS Rating Curve= 0 ,0
Exp/Cntr=0.3,0.1

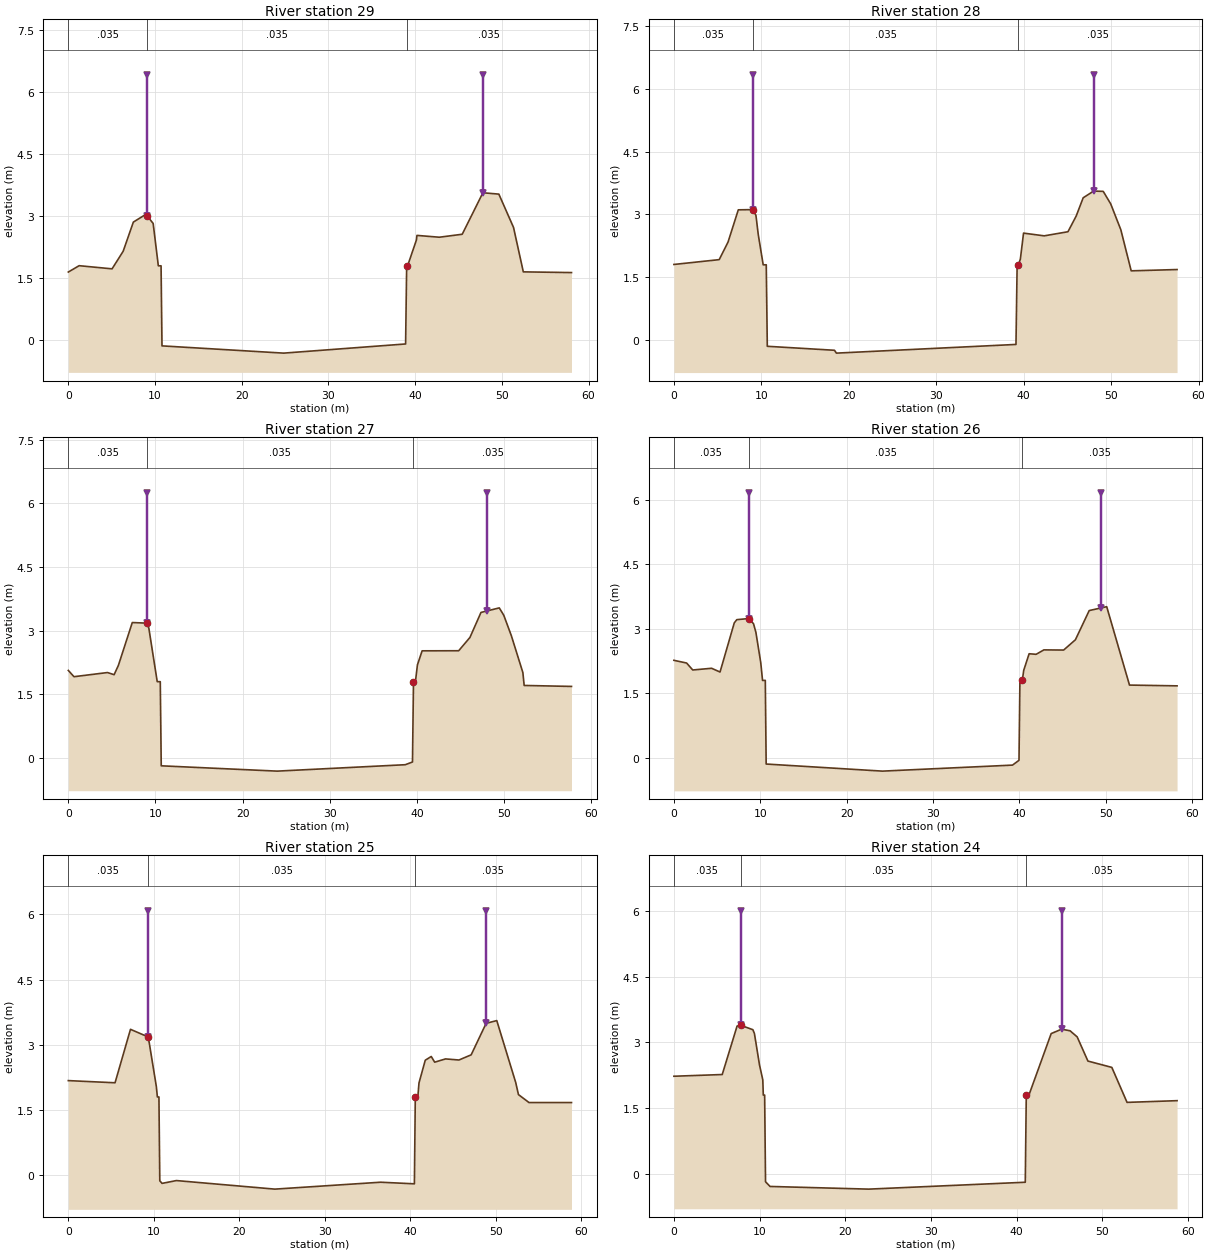
Type RM Length L Ch R = 1 ,29      ,20,20,20
XS GIS Cut Line= 6
      588779.228     4873203.208      588746.487     4873224.644
      588744.144     4873226.179      588739.824     4873229.006
      588739.221     4873229.402      588730.672     4873234.999
#Sta/Elev= 24
       0    1.65   1.248   1.803   5.046   1.727   6.326   2.151   7.501   2.855
   8.801   3.024    9.11   3.001   9.786   2.822  10.382     1.8  10.698     1.8
  10.804   -.132  24.839   -.307  38.904   -.086  39.026     1.8  39.134     1.8
   40.15   2.423  40.215   2.534  42.798    2.49  45.436   2.562  47.819   3.563
   49.66    3.53  51.352   2.727  52.481   1.654  58.038   1.637
#Mann= 3 ,0,0
       0    .035       0    9.11    .035       0  39.026    .035       0
Levee=-1,9.110163,6.409138,-1,47.81931,6.409138,,
Bank Sta=9.11,39.026
XS Rating Curve= 0 ,0
Exp/Cntr=0.3,0.1

Type RM Length L Ch R = 1 ,28      ,20,20,20
XS GIS Cut Line= 6
      588768.205      4873186.52       588734.75     4873208.423
      588729.713     4873211.722      588727.125     4873213.415
      588726.867     4873213.585      588720.061     4873218.041
#Sta/Elev= 27
       0   1.808   5.181   1.923   6.191   2.341   7.365    3.11   9.024   3.115
   9.383   2.978   9.646   2.525  10.212     1.8  10.563     1.8  10.682   -.142
  18.365   -.237  18.586   -.305  39.122   -.098  39.255     1.8  39.402     1.8
  39.625   1.937  39.987   2.555  42.349    2.49  45.067   2.588  46.008   2.962
  46.809   3.397  48.003   3.557  49.101    3.55  49.956   3.252  51.114   2.635
  52.299   1.656  57.545   1.687
#Mann= 3 ,0,0
       0    .035       0   9.024    .035       0  39.402    .035       0
Levee=-1,9.024178,6.327479,-1,48.00293,6.327479,,
Bank Sta=9.024,39.402
XS Rating Curve= 0 ,0
Exp/Cntr=0.3,0.1

Type RM Length L Ch R = 1 ,27      ,20,20,20
XS GIS Cut Line= 6
      588757.317     4873169.743      588752.921     4873172.621
      588752.021     4873173.211      588751.176     4873173.763
      588748.781     4873175.332      588709.008     4873201.372
#Sta/Elev= 27
       0   2.065    .648   1.917   4.497   2.015   5.254   1.964   5.743   2.182
    7.34   3.192   9.013   3.178   9.239   3.061  10.203     1.8  10.552     1.8
  10.663   -.181  23.974   -.306  38.668   -.155  39.495   -.091   39.61     1.8
  39.832     1.8  40.064   2.197    40.6   2.526  44.798   2.528  46.091   2.842
  47.356    3.43  49.454   3.537  49.972   3.363  50.839   2.883  52.161   2.015
  52.312   1.711  57.742   1.688
#Mann= 3 ,0,0
       0    .035       0   9.013    .035       0   39.61    .035       0
Levee=-1,9.01336,6.245821,-1,48.00431,6.245821,,
Bank Sta=9.013,39.61
XS Rating Curve= 0 ,0
Exp/Cntr=0.3,0.1

Type RM Length L Ch R = 1 ,26      ,20,20,20
XS GIS Cut Line= 6
      588746.485     4873152.929      588740.927     4873156.569
      588712.744      4873175.02      588712.083     4873175.454
       588708.11     4873178.054      588697.756     4873184.834
#Sta/Elev= 29
       0   2.267   1.473   2.204   2.181   2.042   4.359   2.082   5.341   1.995
   6.989   3.138   7.283   3.213   8.666   3.239   9.217   3.119   9.492   2.919
  10.055   2.212  10.261     1.8  10.581     1.8   10.68   -.146  24.148   -.311
  39.197   -.171  39.947   -.059  40.055     1.8  40.329     1.8  40.497   2.036
   41.12    2.42  41.929   2.407  42.828    2.51  45.117   2.506  46.476   2.745
  48.076   3.425  50.101   3.515  52.739   1.691  58.245   1.673
#Mann= 3 ,0,0
       0    .035       0   8.666    .035       0  40.329    .035       0
Levee=-1,8.665824,6.164163,-1,49.44464,6.164163,,
Bank Sta=8.666,40.329
XS Rating Curve= 0 ,0
Exp/Cntr=0.3,0.1

Type RM Length L Ch R = 1 ,25      ,20,20,20
XS GIS Cut Line= 6
      588735.681     4873136.098      588705.119     4873156.108
      588704.549      4873156.48      588701.722     4873158.332
      588698.765     4873160.267      588686.436      4873168.34
#Sta/Elev= 29
       0   2.176   5.466   2.126   7.272   3.356   9.287   3.185   9.448   3.067
  10.295   2.043  10.417     1.8    10.6     1.8    10.7   -.129  10.968   -.189
   12.64   -.124  24.162   -.321   36.53   -.162  40.483   -.199   40.59     1.8
  40.885     1.8  41.022   2.123  41.755   2.645  42.457   2.731  42.855     2.6
  44.124   2.675  45.699    2.65  47.126   2.769  48.875   3.494  50.121   3.557
  52.335   2.133  52.658   1.854  53.894   1.671  58.861   1.671
#Mann= 3 ,0,0
       0    .035       0   9.287    .035       0   40.59    .035       0
Levee=-1,9.287113,6.082504,-1,48.87467,6.082504,,
Bank Sta=9.287,40.59
XS Rating Curve= 0 ,0
Exp/Cntr=0.3,0.1

Type RM Length L Ch R = 1 ,24      ,20,20,20
XS GIS Cut Line= 6
      588724.849     4873119.285      588719.442     4873122.824
      588717.139     4873124.333      588690.552     4873141.739
      588686.853     4873144.162      588675.738     4873151.439
#Sta/Elev= 24
       0   2.229   5.638   2.268   7.372   3.373   7.776   3.392   9.216    3.29
   9.396   3.202   9.989   2.485  10.372   2.146   10.43     1.8  10.586     1.8
  10.691   -.177  11.215   -.284  22.727   -.345  40.993   -.188   41.11     1.8
  41.423   1.802  44.016   3.202  45.232   3.302  46.223   3.265  47.049   3.126
  48.301   2.575   51.09   2.431  52.866   1.633  58.701   1.672
#Mann= 3 ,0,0
       0    .035       0   7.776    .035       0   41.11    .035       0
Levee=-1,7.776061,6.000846,-1,45.2321,6.000846,,
Bank Sta=7.776,41.11
XS Rating Curve= 0 ,0
Exp/Cntr=0.3,0.1

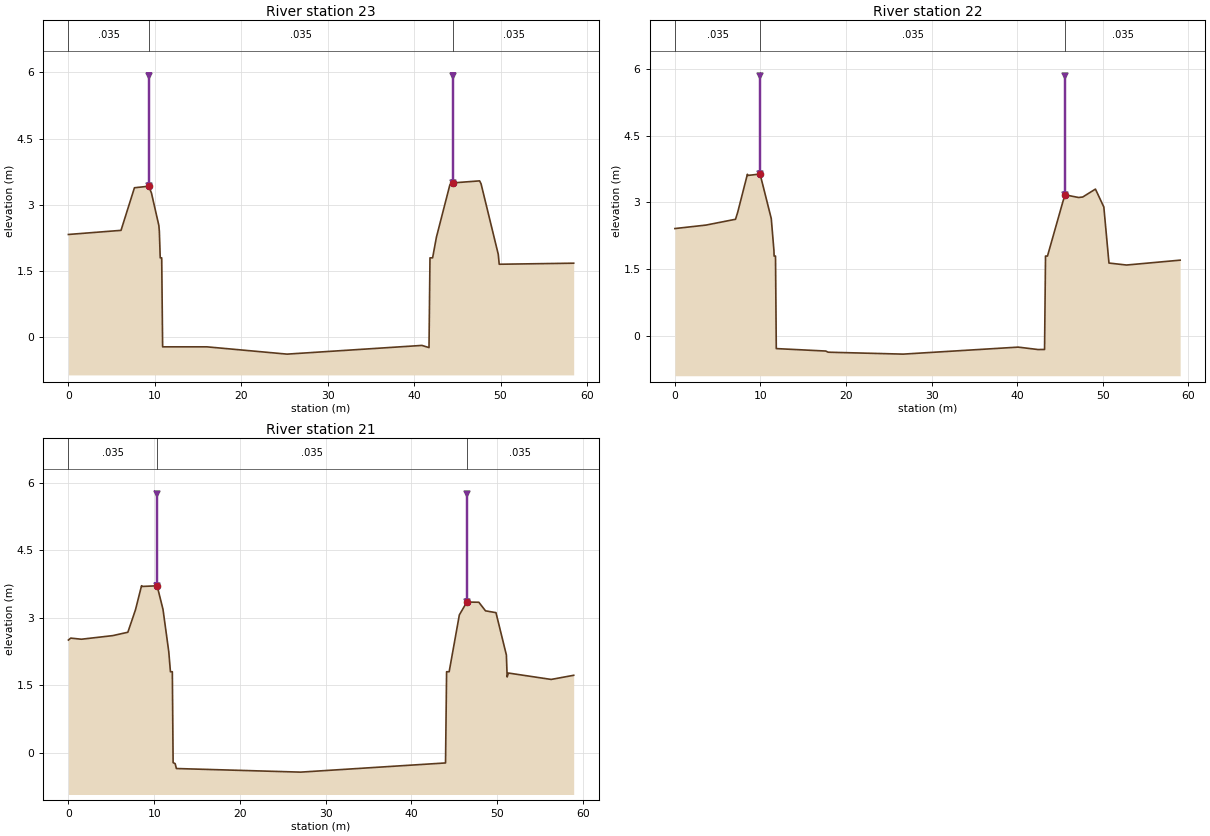
Type RM Length L Ch R = 1 ,23      ,20,20,20
XS GIS Cut Line= 6
      588714.192     4873102.356      588711.927      4873103.84
      588705.162     4873108.268      588705.072     4873108.328
      588677.525     4873126.363      588665.277     4873134.383
#Sta/Elev= 24
       0   2.329   6.086   2.422   7.639   3.386   9.294   3.421   9.606   3.268
  10.464   2.534  10.522   2.399  10.623     1.8  10.793     1.8  10.901   -.214
  16.025   -.214  25.303   -.379  40.905   -.182  41.725   -.231  41.838     1.8
  42.142     1.8  42.583   2.268  44.142   3.454  44.541   3.497   47.58   3.542
  47.746   3.478  49.743   1.877  49.849   1.655  58.467   1.679
#Mann= 3 ,0,0
       0    .035       0   9.294    .035       0  44.541    .035       0
Levee=-1,9.294325,5.919188,-1,44.54064,5.919188,,
Bank Sta=9.294,44.541
XS Rating Curve= 0 ,0
Exp/Cntr=0.3,0.1

Type RM Length L Ch R = 1 ,22      ,20,20,20
XS GIS Cut Line= 6
      588704.136     4873085.035      588697.048     4873089.676
       588697.01       4873089.7       588695.81     4873090.487
      588694.455     4873091.373      588654.747     4873117.371
#Sta/Elev= 29
       0   2.416   3.636   2.494   7.084   2.624   7.339   2.782   8.472   3.632
   8.517   3.606   9.952   3.637   11.26    2.64  11.571   1.927  11.592     1.8
  11.755     1.8  11.846   -.273  17.628   -.328  17.911   -.354  26.672   -.397
  40.109    -.24  42.419   -.294  43.191   -.293  43.303     1.8  43.532     1.8
  45.344   3.026  45.602   3.171  47.164   3.112  47.653   3.123  49.135     3.3
  50.115     2.9  50.717   1.643  52.766   1.599  59.033   1.708
#Mann= 3 ,0,0
       0    .035       0   9.952    .035       0  45.602    .035       0
Levee=-1,9.952222,5.837529,-1,45.60183,5.837529,,
Bank Sta=9.952,45.602
XS Rating Curve= 0 ,0
Exp/Cntr=0.3,0.1

Type RM Length L Ch R = 1 ,21      ,20,20,20
XS GIS Cut Line= 6
      588693.528     4873068.075       588692.26     4873068.906
      588683.734     4873074.487      588683.572     4873074.594
      588683.387     4873074.714      588644.217      4873100.36
#Sta/Elev= 30
       0   2.505     .27   2.548   1.516   2.523   5.167   2.603   6.933   2.678
   7.821   3.177   8.531   3.713   8.558   3.696  10.346   3.711  11.032   3.187
  11.706   2.245    11.9     1.8  12.121     1.8  12.212   -.221  12.449   -.243
  12.595   -.352  27.093   -.432  43.991   -.228  44.114     1.8  44.414     1.8
  45.603   3.064   46.48    3.35  47.878   3.345  48.654   3.154  49.874   3.114
   51.09   2.171  51.179   1.684  51.327   1.771  56.314   1.629   58.94   1.721
#Mann= 3 ,0,0
       0    .035       0  10.346    .035       0   46.48    .035       0
Levee=-1,10.34607,5.755871,-1,46.48022,5.755871,,
Bank Sta=10.346,46.48
XS Rating Curve= 0 ,0
Exp/Cntr=0.3,0.1