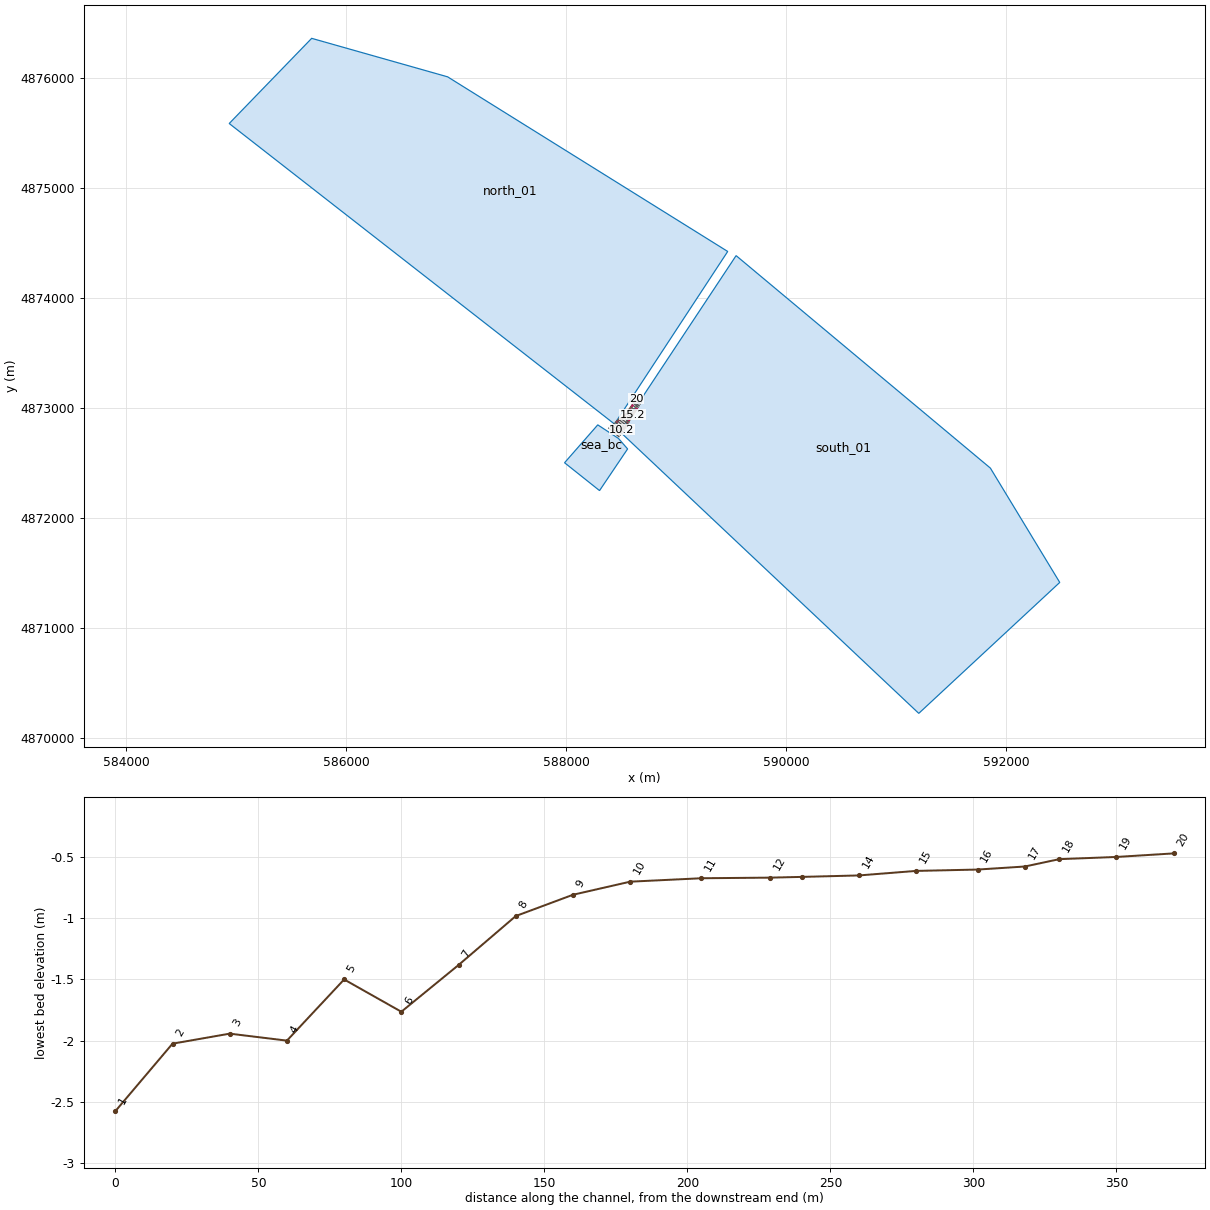
HEC-RAS study massa.prj: massa

--- massa.g05 (geometry) --- (continued)

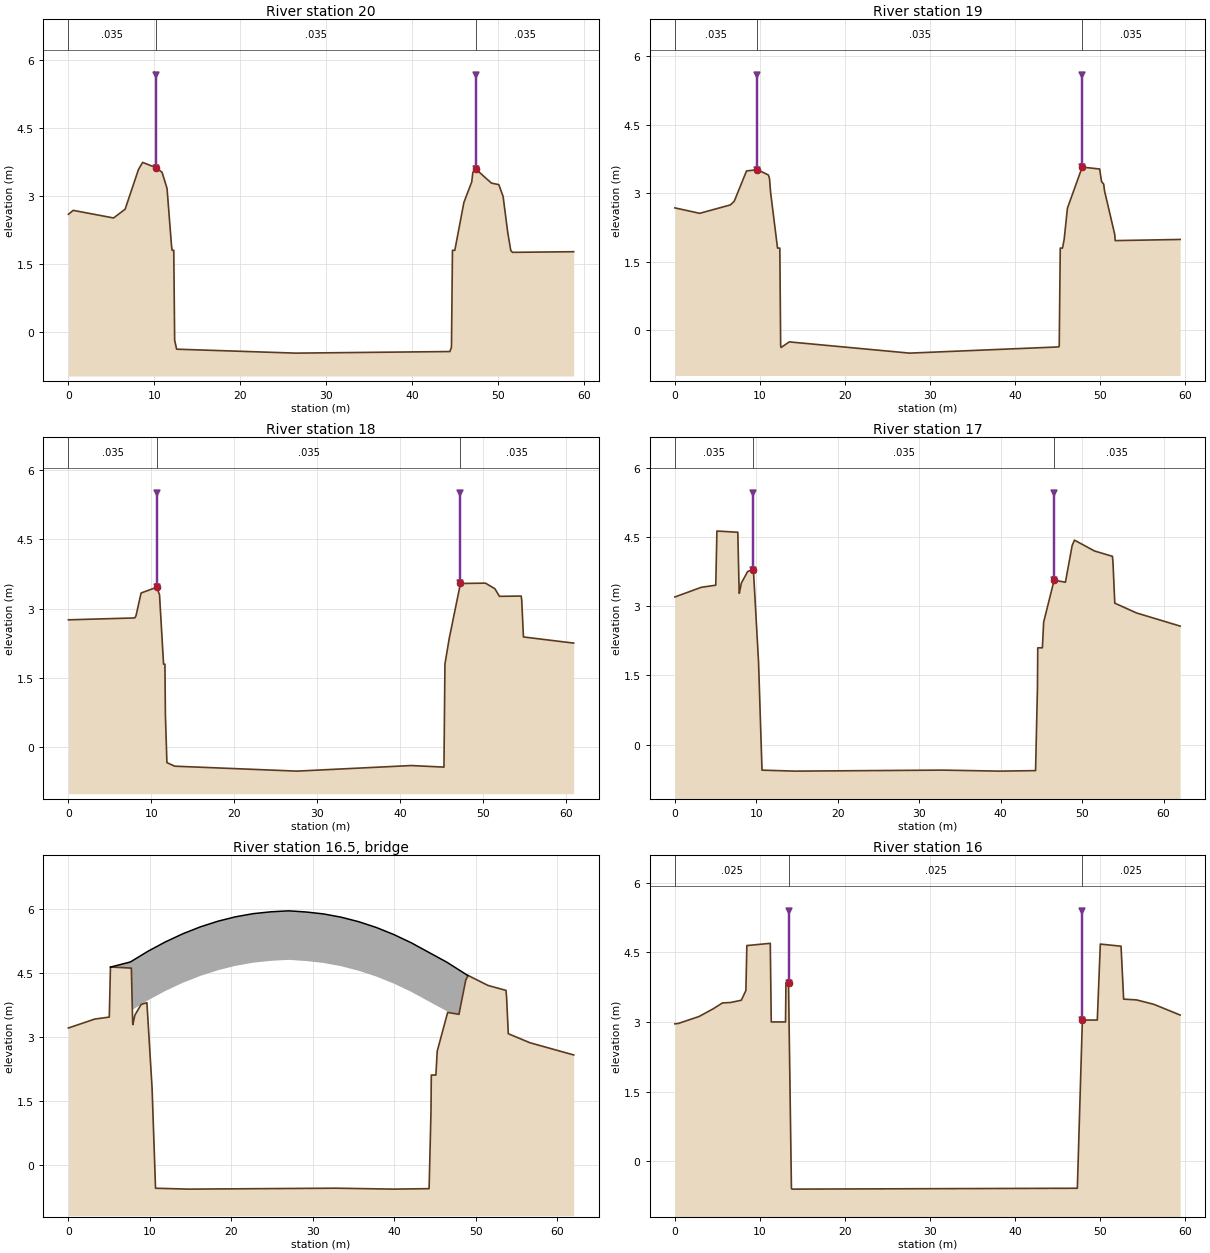
Type RM Length L Ch R = 1 ,20      ,20,20,20
XS GIS Cut Line= 6
      588682.724     4873051.243      588678.626     4873053.927
      588672.628     4873057.854      588672.023     4873058.249
      588668.756     4873060.389      588633.531     4873083.451
#Sta/Elev= 30
       0   2.595    .555   2.682   5.253   2.514   6.597   2.707   8.153   3.585
   8.637   3.741  10.152   3.628  10.898   3.522  11.477   3.166  11.991   1.915
  12.068     1.8  12.259     1.8  12.362   -.184  12.592   -.383  26.456    -.47
  44.394   -.435  44.577   -.338  44.692     1.8  44.967     1.8  46.024   2.858
  46.929   3.307  47.069   3.524  47.443   3.587  49.226   3.284  50.087    3.25
  50.585   2.989  51.128   2.191  51.478   1.795  51.673   1.755  58.799   1.769
#Mann= 3 ,0,0
       0    .035       0  10.152    .035       0  47.443    .035       0
Levee=-1,10.15164,5.674212,-1,47.44294,5.674212,,
Bank Sta=10.152,47.443
XS Rating Curve= 0 ,0
Exp/Cntr=0.3,0.1

Type RM Length L Ch R = 1 ,19      ,20,20,20
XS GIS Cut Line= 6
      588672.535      4873035.37      588663.099     4873041.014
      588662.982     4873041.085      588662.877     4873041.147
      588661.862     4873041.754      588621.544      4873065.87
#Sta/Elev= 29
       0    2.68   2.916   2.561   6.523   2.745   6.974   2.824   8.423   3.488
   9.697   3.517  10.995     3.4  11.132   3.315  11.254    3.02  12.071     1.8
  12.339     1.8  12.437   -.328  12.489   -.376  13.447   -.253    27.6   -.499
  45.152   -.363  45.197   -.338  45.318     1.8  45.581     1.8  45.779   1.992
   46.16   2.673  47.899   3.573   49.95   3.531  50.171   3.256  50.426   3.201
  50.527   3.052  51.733   2.092  51.775   1.964  59.417   1.989
#Mann= 3 ,0,0
       0    .035       0   9.697    .035       0  47.899    .035       0
Levee=-1,9.697226,5.592554,-1,47.89944,5.592554,,
Bank Sta=9.697,47.899
XS Rating Curve= 0 ,0
Exp/Cntr=0.3,0.1

Type RM Length L Ch R = 1 ,18      ,12,12,12
BEGIN DESCRIPTION:
231 pr. 2260.0
END DESCRIPTION:
XS GIS Cut Line= 6
      588661.916     4873018.417      588657.104     4873021.296
      588654.397     4873022.914      588653.899     4873023.213
      588651.931     4873024.389      588609.633      4873049.69
#Sta/Elev= 24
       0    2.76   8.001   2.801   8.144   2.846   8.761   3.341  10.642   3.465
  10.983   3.304  11.471     1.8  11.635     1.8  11.693    .697  11.875   -.333
  12.819    -.41  27.557   -.517  41.343   -.396   45.28    -.43  45.398     1.8
  45.912   2.354   47.27   3.547  50.281   3.555  51.421   3.434  51.973   3.269
  54.594   3.275  54.658   3.182  54.864   2.389  60.922   2.256
#Mann= 3 ,0,0
       0    .035       0  10.642    .035       0   47.27    .035       0
Levee=-1,10.64218,5.510896,-1,47.27021,5.510896,,
Bank Sta=10.642,47.27
XS Rating Curve= 0 ,0
Exp/Cntr=0.3,0.1

Type RM Length L Ch R = 1 ,17      ,16.55,16.55,16.55
XS GIS Cut Line= 6
      588653.022     4873004.946      588650.538     4873007.005
      588645.117     4873011.502      588618.758      4873033.36
      588618.172     4873033.847      588605.274     4873044.543
#Sta/Elev= 30
       0   3.202   3.226   3.411   5.017   3.458   5.159   4.633   7.725   4.606
   7.882   3.362   7.907   3.281   8.161   3.504    8.93   3.754   9.637   3.795
   10.27    1.79  10.695   -.556  14.758   -.577  32.854   -.555  39.831   -.577
   44.28   -.566  44.513   1.248   44.55   2.099  45.117   2.099  45.275   2.657
  46.558   3.567  47.946   3.522   48.77   4.317  49.058   4.435  51.515     4.2
  53.721   4.084   53.79    3.93  54.006   3.068  56.679   2.855  62.031    2.57
#Mann= 3 ,0,0
       0    .035       0   9.637    .035       0  46.558    .035       0
Levee=-1,9.637112,5.461901,-1,46.55793,5.461901,,
Bank Sta=9.637,46.558
XS Rating Curve= 0 ,0
Exp/Cntr=0.3,0.1

Type RM Length L Ch R = 3 ,16.5    ,,,
Bridge Culvert--1,0,-1,-1, 0
Deck Dist Width WeirC Skew NumUp NumDn MinLoCord MaxHiCord MaxSubmerge Is_Ogee
1,14.55,1.4,0, 21, 21, , , 0.98, 0, 0,0,,
    5.16   7.601   9.758  11.914  14.071  16.227  18.384   20.54  22.697  24.853
   27.01  29.166  31.323  33.479  35.636  37.792  39.949  42.105  44.262  46.417
   49.06
    4.63    4.75   5.001   5.222   5.414   5.576   5.708   5.811   5.884   5.927
    5.95   5.923   5.877   5.801   5.695    5.56   5.394   5.199   4.974    4.75
    4.43
    3.48     3.6   3.851   4.072   4.264   4.426   4.558   4.661   4.734   4.777
     4.8   4.773   4.727   4.651   4.545    4.41   4.244   4.049   3.824     3.6
    3.28
      10   11.31  13.467  15.623   17.78  19.937  22.093   24.25  26.406  28.563
  30.719  32.876  35.033  37.189  39.346  41.502  43.659  45.815  47.972  50.127
      52
   4.581    4.75   4.999    5.22   5.412   5.574   5.706   5.808    5.88   5.923
    5.95   5.919   5.872   5.796    5.69   5.554   5.388   5.193   4.968    4.75
   4.468
   3.431     3.6   3.849    4.07   4.262   4.424   4.556   4.658    4.73   4.773
     4.8   4.769   4.722   4.646    4.54   4.404   4.238   4.043   3.818     3.6
   3.318
BR Coef=-1 , 0 , 0 ,, 0 ,,,0.8,-1,,0,
WSPro=,,,, 1 ,,,, 0 ,,,, 0 ,,,,-1 ,-1 ,-1 , 0 , 0 , 0 , 0 , 0
BC Design=,, 0 ,, 0 ,,,,,,
BC Use User HTab Curves=0
BC User HTab FreeFlow(D)= 0

Type RM Length L Ch R = 1 ,16      ,21.45,21.45,21.45
XS GIS Cut Line= 6
      588645.296     4872989.844      588639.288     4872994.827
      588608.888     4873020.037       588606.81     4873021.761
      588601.959     4873025.783      588599.588      4873027.75
#Sta/Elev= 25
       0   2.959    .428   2.969   2.832   3.117   4.502   3.283   5.589    3.41
   6.541   3.419   7.806   3.468   8.343   3.677   8.458   4.646  11.209   4.694
  11.325       3  13.001       3  13.054    3.85  13.353    3.85  13.696   -.583
   13.76   -.602  47.299   -.583  47.889   3.041  49.644   3.041  49.999   4.678
  52.434   4.632  52.739   3.492  54.262   3.475    56.3   3.379  59.381   3.149
#Mann= 3 ,0,0
       0    .025       0  13.353    .025       0  47.889    .025       0
Levee=-1,13.35275,5.394328,-1,47.88875,5.394328,,
Bank Sta=13.353,47.889
XS Rating Curve= 0 ,0
Exp/Cntr=0.3,0.1

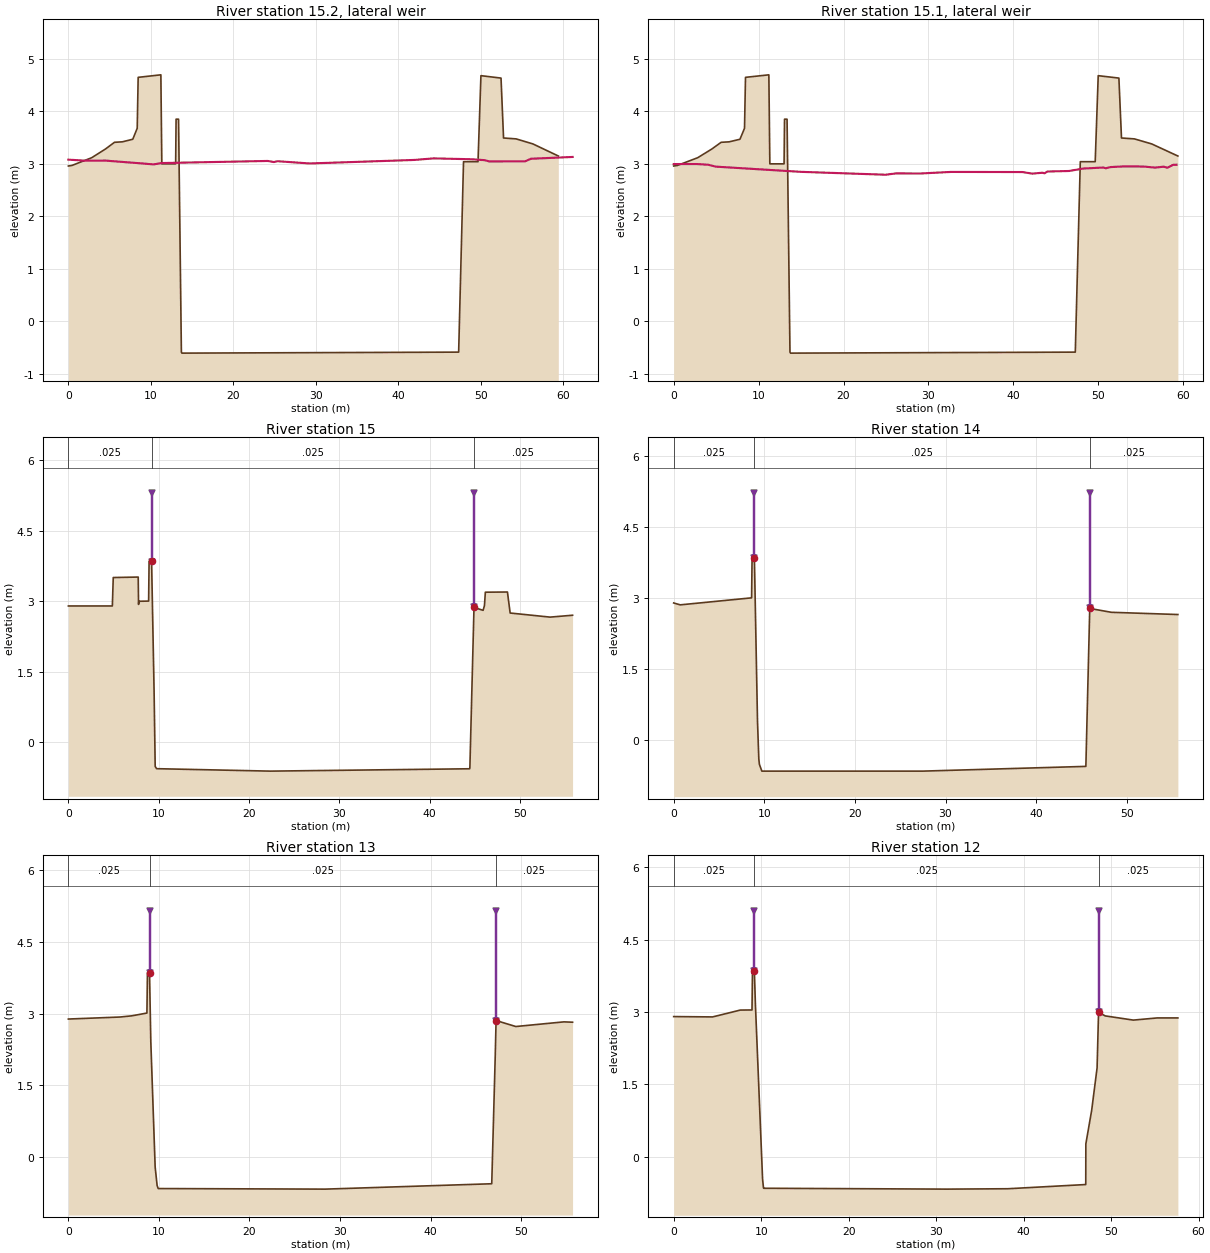
Type RM Length L Ch R = 6 ,15.2    ,,,
Lateral Weir Pos= 0
Lateral Weir End=                ,                ,        ,south_01
Lateral Weir TW Multiple XS=0
Lateral Weir WD=1
Lateral Weir Coef=1.1
LW OverFlow Method 2D=0
LW OverFlow Use Velocity Into 2D=0
Lateral Weir WSCriteria=-1
Lateral Weir Flap Gates= 0
Lateral Weir Hagers EQN= 0 ,,,,,
Lateral Weir SS=0.05,0.05,
Lateral Weir Type= 0
Lateral Weir Connection Pos and Dist= 3 ,
Lateral Weir SE= 17
       0    3.08   2.045    3.06   4.489   3.062  10.328    2.99  11.343   3.015
  24.147   3.055  24.898   3.034  25.369    3.05   29.25   3.007  41.896   3.074
  44.257   3.104  48.979   3.087  50.488   3.069  51.012   3.045  55.364   3.049
  56.063   3.097  61.105   3.131
Lateral Weir Centerline= 3
588636.0794905684872990.54657933 588625.741036074872973.08984469
 588604.047229914872938.51534112
LW Div RC= 0 ,False,,

Type RM Length L Ch R = 6 ,15.1    ,,,
Lateral Weir Pos= 3
Lateral Weir End=                ,                ,        ,north_01
Lateral Weir TW Multiple XS=0
Lateral Weir WD=1
Lateral Weir Coef=1.1
LW OverFlow Method 2D=0
LW OverFlow Use Velocity Into 2D=0
Lateral Weir WSCriteria=-1
Lateral Weir Flap Gates= 0
Lateral Weir Hagers EQN= 0 ,,,,,
Lateral Weir SS=0.05,0.05,
Lateral Weir Type= 0
Lateral Weir Connection Pos and Dist= 3 ,
Lateral Weir SE= 26
       0   2.996   2.789   2.996   4.064   2.983   4.949   2.947  14.954   2.848
  24.958   2.793  26.221   2.819  29.005   2.816  32.656   2.846  41.067   2.844
  42.227   2.814  43.446   2.831  43.674    2.82  44.028   2.854  46.568   2.864
  48.203    2.91  50.581    2.93  50.909   2.916  51.419   2.938   52.96   2.951
  55.338   2.949  56.697   2.928  57.717   2.946  58.144   2.926  58.809   2.981
  59.219   2.983
Lateral Weir Centerline= 3
588599.3565360674873018.04563709588579.8449492764872991.85903377
588565.4679905884872969.52340152
LW Div RC= 0 ,False,,

Type RM Length L Ch R = 1 ,15      ,20,20,20
XS GIS Cut Line= 6
      588632.591     4872976.718      588624.872     4872981.752
       588613.87     4872988.929      588595.352     4873001.006
      588591.867      4873003.28      588585.825      4873007.22
#Sta/Elev= 23
       0     2.9    4.87     2.9    4.97   3.505   7.734   3.515   7.772   2.933
   7.806       3   8.887   3.004   8.939    3.85   9.215    3.85   9.493   1.075
   9.613   -.513   9.767   -.561  22.351   -.613  44.426   -.563   44.46    -.55
  44.918   2.869  45.927   2.807  46.077   2.909  46.174   3.193  48.621   3.197
  48.921    2.75  53.346   2.663  55.834   2.703
#Mann= 3 ,0,0
       0    .025       0   9.215    .025       0  44.918    .025       0
Levee=-1,9.215429,5.30675,-1,44.91829,5.30675,,
Bank Sta=9.215,44.918
XS Rating Curve= 0 ,0
Exp/Cntr=0.3,0.1

Type RM Length L Ch R = 1 ,14      ,20,20,20
XS GIS Cut Line= 6
      588621.904      4872959.81      588614.702     4872964.508
      588614.156     4872964.863       588613.98     4872964.979
      588613.752     4872965.127        588575.3     4872990.207
#Sta/Elev= 14
       0     2.9    .721    2.86   8.599   3.008   8.652    3.85   8.907    3.85
    9.25    .401   9.395    -.39   9.461   -.508   9.733    -.65  27.483    -.65
  45.486    -.55  45.915   2.784    48.3   2.703  55.641   2.656
#Mann= 3 ,0,0
       0    .025       0   8.907    .025       0  45.915    .025       0
Levee=-1,8.906715,5.225091,-1,45.91542,5.225091,,
Bank Sta=8.907,45.915
XS Rating Curve= 0 ,0
Exp/Cntr=0.3,0.1

Type RM Length L Ch R = 1 ,13      ,11.09,11.09,11.09
XS GIS Cut Line= 6
      588611.524     4872942.702      588604.017     4872947.599
      588603.896     4872947.677      588603.212     4872948.123
      588572.034     4872968.459      588564.877     4872973.128
#Sta/Elev= 17
       0   2.886    5.69   2.928   7.007   2.953   8.676   3.011   8.733    3.85
   8.963    3.85   9.107    2.41   9.585   -.199   9.803   -.587   9.924    -.65
  28.366   -.662  46.764    -.55  47.147   2.092  47.244   2.855  49.424    2.73
  54.734   2.827  55.693    2.82
#Mann= 3 ,0,0
       0    .025       0   8.963    .025       0  47.244    .025       0
Levee=-1,8.963017,5.143433,-1,47.24427,5.143433,,
Bank Sta=8.963,47.244
XS Rating Curve= 0 ,0
Exp/Cntr=0.3,0.1

Type RM Length L Ch R = 1 ,12      ,24.04,24.04,24.04
XS GIS Cut Line= 6
      588604.141     4872930.291      588598.285     4872935.166
      588596.962     4872936.266      588567.935     4872960.428
      588567.927     4872960.436      588559.841     4872967.166
#Sta/Elev= 21
       0   2.907   4.452     2.9    7.62   3.042   8.954   3.044   9.007    3.85
   9.224    3.85    9.34   3.177  10.162   -.459  10.264   -.639  10.284    -.65
  31.265   -.668  38.197    -.66  47.107   -.573  47.119     .27  47.784    .965
  48.403   1.844   48.57   2.992  49.341   2.921  52.548   2.834  55.266   2.879
  57.639   2.879
#Mann= 3 ,0,0
       0    .025       0   9.224    .025       0   48.57    .025       0
Levee=-1,9.22442,5.098154,-1,48.57022,5.098154,,
Bank Sta=9.224,48.57
XS Rating Curve= 0 ,0
Exp/Cntr=0.3,0.1

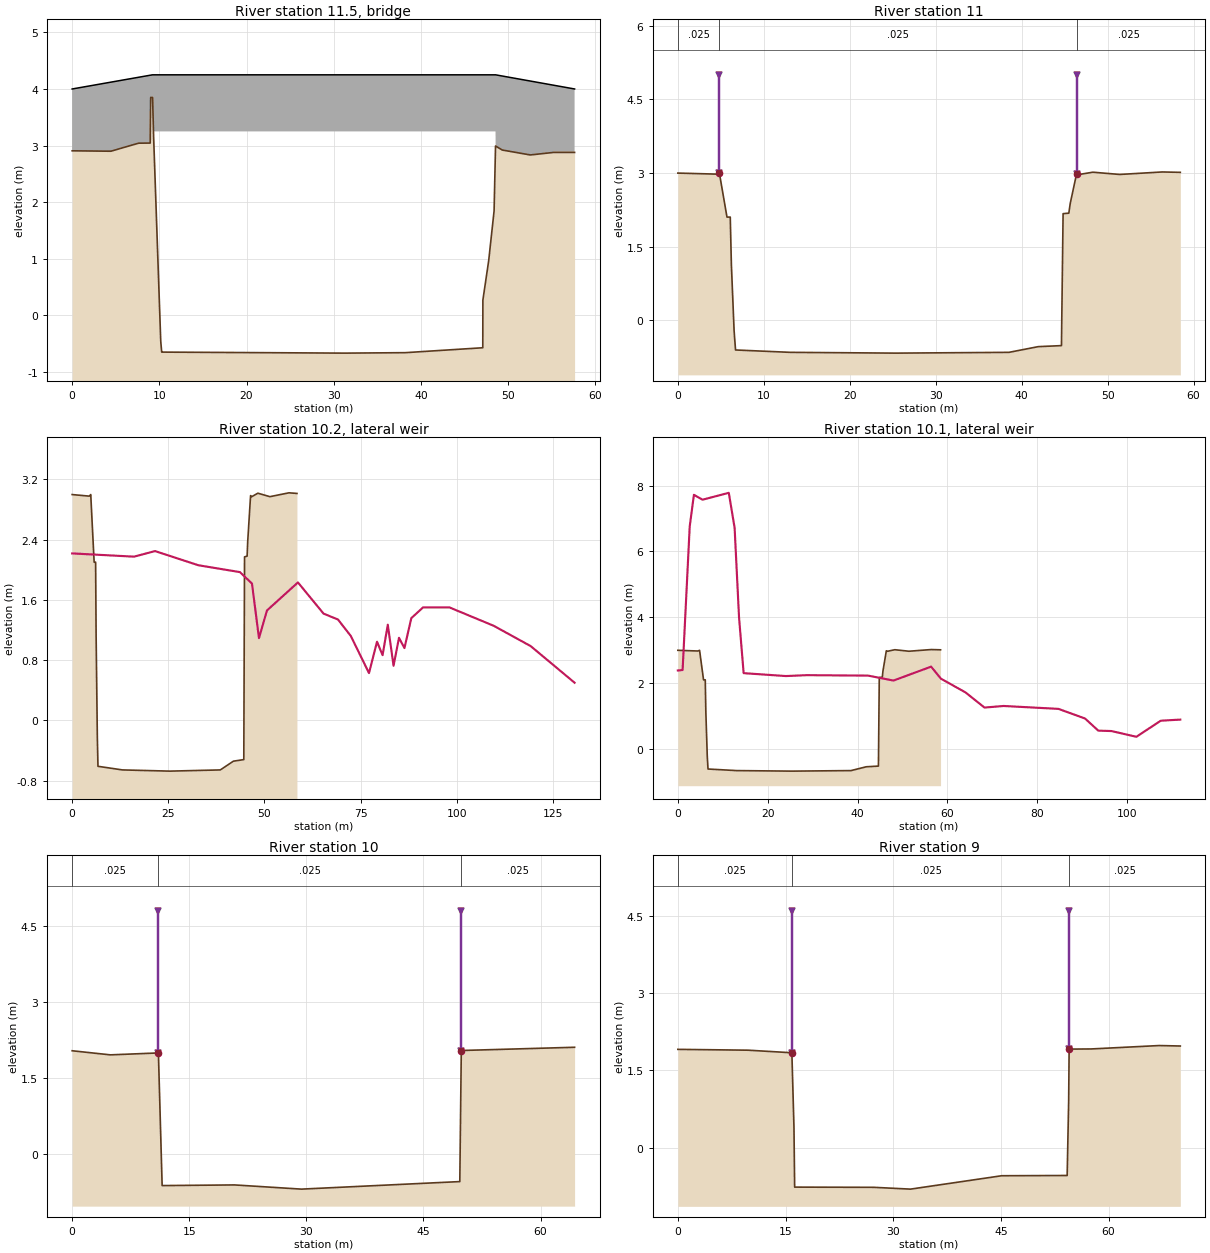
Type RM Length L Ch R = 3 ,11.5    ,,,
Bridge Culvert--1,0,-1,-1, 0
Deck Dist Width WeirC Skew NumUp NumDn MinLoCord MaxHiCord MaxSubmerge Is_Ogee
1,22,1.4,0, 6, 6, , , 0.98, 0, 0,0,,
       0    9.21    9.22   48.57   48.58   57.64
       4    4.25    4.25    4.25    4.25       4
     2.5     2.5    3.25    3.25     2.5     2.5
       0    4.82    4.83   46.39    46.4   58.45
       4    4.25    4.25    4.25    4.25       4
     2.5     2.5    3.25    3.25     2.5     2.5
BR Coef=-1 , 0 , 0 ,, 0 ,,,0.8,-1,,0,
WSPro=,,,, 1 ,,,, 0 ,,,, 0 ,,,,-1 ,-1 ,-1 , 0 , 0 , 0 , 0 , 0
BC Design=,, 0 ,, 0 ,,,,,,
BC Use User HTab Curves=0
BC User HTab FreeFlow(D)= 0

Type RM Length L Ch R = 1 ,11      ,24.87,24.87,24.87
XS GIS Cut Line= 6
      588588.261     4872912.421      588583.474     4872916.405
      588583.232     4872916.608      588556.039     4872939.242
      588544.945     4872948.478      588543.334     4872949.818
#Sta/Elev= 22
       0   2.997   4.463   2.976   4.832   2.997   5.716     2.1   6.097     2.1
   6.228   1.128   6.544   -.217   6.711   -.609  13.083   -.657  25.375   -.673
  38.523   -.657  41.924   -.541  44.629    -.52   44.82    2.17  45.488    2.18
  45.644   2.372   46.39   2.983  46.658   2.968  48.288   3.015  51.413   2.969
  56.359    3.02  58.455   3.012
#Mann= 3 ,0,0
       0    .025       0   4.832    .025       0   46.39    .025       0
Levee=-1,4.831985,5,-1,46.38957,5,,
Bank Sta=4.832,46.39
XS Rating Curve= 0 ,0
Exp/Cntr=0.3,0.1

Type RM Length L Ch R = 6 ,10.2    ,,,
Lateral Weir Pos= 0
Lateral Weir End=                ,                ,        ,south_01
Lateral Weir TW Multiple XS=0
Lateral Weir WD=1
Lateral Weir Coef=1.1
LW OverFlow Method 2D=0
LW OverFlow Use Velocity Into 2D=0
Lateral Weir WSCriteria=-1
Lateral Weir Flap Gates= 0
Lateral Weir Hagers EQN= 0 ,,,,,
Lateral Weir SS=0.05,0.05,
Lateral Weir Type= 0
Lateral Weir Connection Pos and Dist= 3 ,
Lateral Weir SE= 25
       0   2.216   16.09   2.173  21.552   2.247  32.807   2.059  43.619   1.968
  46.756   1.816  48.571   1.092  50.654   1.459  58.708   1.831  65.366   1.417
  69.113   1.339  72.456    1.12  77.183    .628  79.265   1.044  80.715    .866
  82.071    1.27  83.565    .725  84.983   1.096  86.401     .96  88.188   1.357
  91.246     1.5  98.074     1.5 109.596   1.256 119.224    .986 130.643      .5
Lateral Weir Centerline= 6
 588578.357225674872902.76752414588564.1382513014872877.80532469
588551.4991629734872863.90232753588553.0790490144872850.31530758
588542.3358239354872833.25253833588505.0505133664872801.02286309
LW Div RC= 0 ,False,,

Type RM Length L Ch R = 6 ,10.1    ,,,
Lateral Weir Pos= 3
Lateral Weir End=                ,                ,        ,north_01
Lateral Weir TW Multiple XS=0
Lateral Weir WD=1
Lateral Weir Coef=1.1
LW OverFlow Method 2D=0
LW OverFlow Use Velocity Into 2D=0
Lateral Weir WSCriteria=-1
Lateral Weir Flap Gates= 0
Lateral Weir Hagers EQN= 0 ,,,,,
Lateral Weir SS=0.05,0.05,
Lateral Weir Type= 0
Lateral Weir Connection Pos and Dist= 3 ,
Lateral Weir SE= 25
       0   2.384   1.058   2.398   2.638   6.759   3.569    7.72   5.493   7.572
  11.332   7.781   12.63   6.716  13.615   3.995  14.639   2.303  24.049   2.215
  28.684   2.242  42.362   2.228  47.981   2.078  56.353   2.501   58.54   2.135
  63.992   1.719  68.239   1.258  72.485   1.306  84.688   1.218  90.596    .926
   93.55    .557  96.504    .544 102.023     .37 107.458    .859 111.801    .892
Lateral Weir Centerline= 4
588538.5440974364872935.62915379588519.5854649444872910.66695434
588493.9913110794872902.76752414588454.4941600534872866.43014519
LW Div RC= 0 ,False,,

Type RM Length L Ch R = 1 ,10      ,20,20,20
XS GIS Cut Line= 6
      588579.721     4872891.756      588570.478     4872897.806
       588555.15     4872907.837      588538.172      4872918.95
      588538.012     4872919.054      588525.868     4872927.002
#Sta/Elev= 9
       0   2.034    4.89   1.953  11.047   1.991  11.526   -.631    20.8   -.618
  29.365   -.701  49.657   -.552  49.848   2.039  64.362   2.103
#Mann= 3 ,0,0
       0    .025       0  11.047    .025       0  49.848    .025       0
Levee=-1,11.04697,4.8,-1,49.84799,4.8,,
Bank Sta=11.047,49.848
XS Rating Curve= 0 ,0
Exp/Cntr=0.3,0.1

Type RM Length L Ch R = 1 ,9       ,20,20,20
XS GIS Cut Line= 6
      588570.407     4872870.433      588557.685     4872880.424
      588557.609     4872880.483      588527.749     4872903.931
      588527.533       4872904.1      588515.352     4872913.665
#Sta/Elev= 14
       0   1.908   9.754   1.892  15.885   1.842  16.176    .397  16.272   -.769
  27.305   -.773  32.415   -.808  45.112   -.548  54.239   -.543  54.449    .915
  54.513   1.913   57.61   1.916  67.056   1.982      70   1.973
#Mann= 3 ,0,0
       0    .025       0  15.885    .025       0  54.513    .025       0
Levee=-1,15.88492,4.6,-1,54.51281,4.6,,
Bank Sta=15.885,54.513
XS Rating Curve= 0 ,0
Exp/Cntr=0.3,0.1

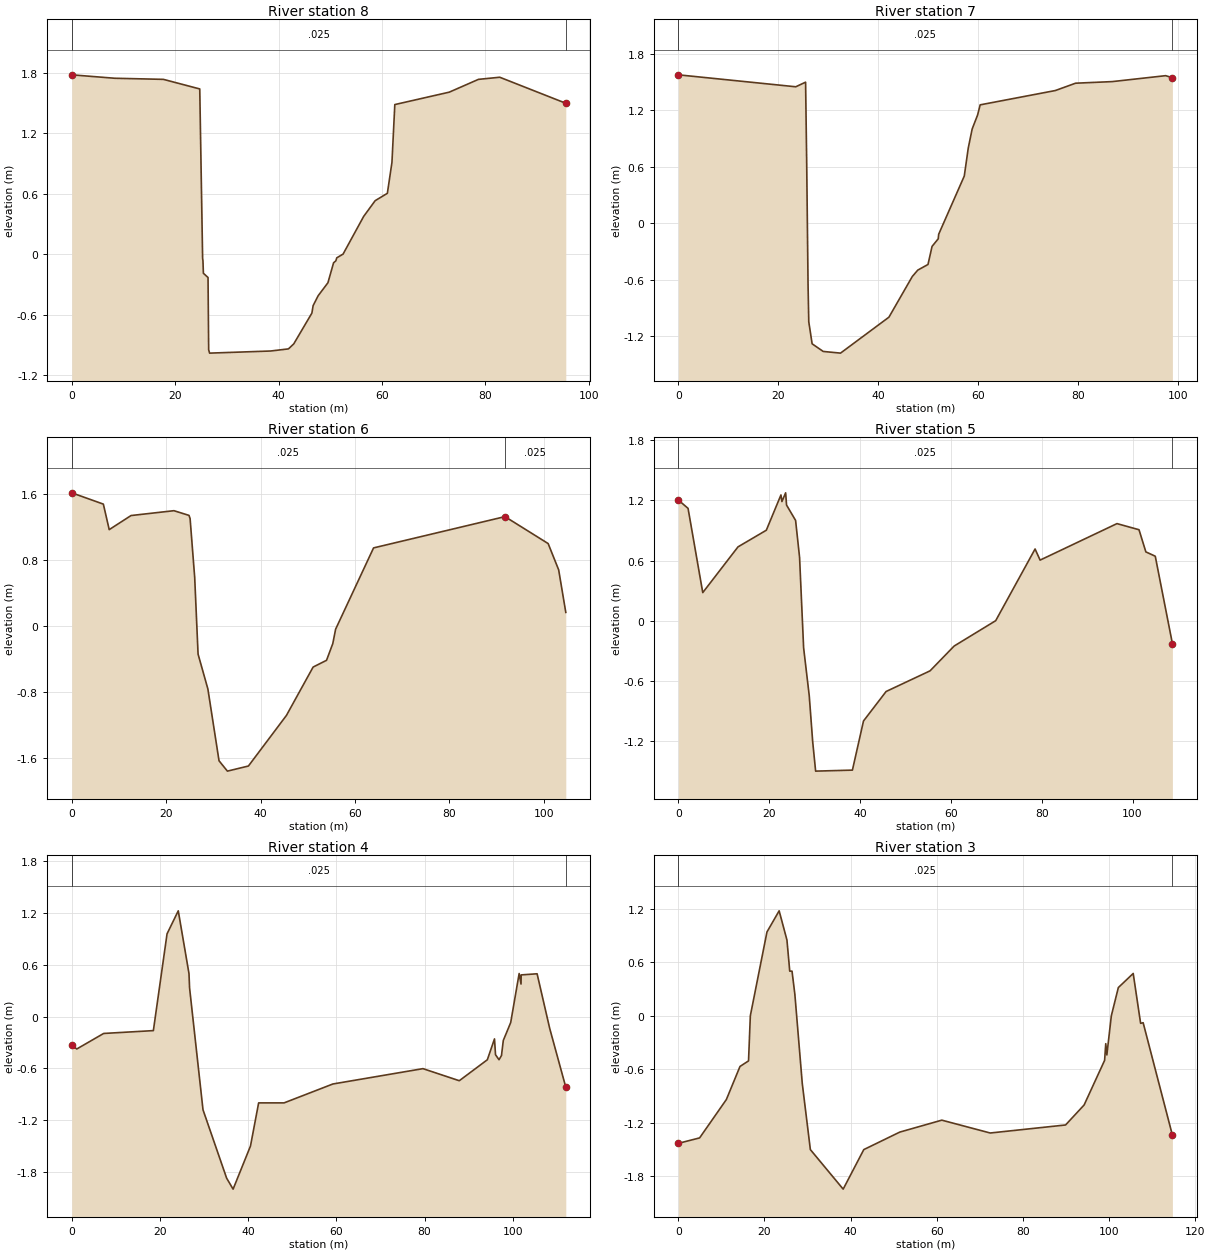
Type RM Length L Ch R = 1 ,8       ,20,20,20
XS GIS Cut Line= 6
      588565.631     4872848.754      588544.658     4872865.224
      588531.866     4872875.268      588528.913     4872877.588
      588516.486     4872887.345      588490.478     4872907.769
#Sta/Elev= 30
       0   1.778   8.313   1.744  17.728   1.733  24.758   1.638  25.314   -.043
  25.377   -.065  25.463    -.19   26.36   -.232  26.483   -.949  26.667   -.982
  38.471   -.961   41.91    -.94  42.931   -.891  46.447   -.585  46.686   -.511
  47.657   -.413  49.549   -.284  50.643   -.086  51.078   -.067  51.258   -.037
  52.477       0  56.464    .374  58.687     .53  61.046    .603  61.932     .91
  62.486   1.483  73.012   1.606  78.665   1.733  82.782   1.754  95.555   1.496
#Mann= 3 ,0,0
       0    .025       0       0    .025       0  95.555    .025       0
Bank Sta=0,95.555
XS Rating Curve= 0 ,0
Exp/Cntr=0.3,0.1

Type RM Length L Ch R = 1 ,7       ,20,20,20
XS GIS Cut Line= 6
      588552.993     4872831.016      588533.421     4872847.636
      588533.102     4872847.908      588532.588     4872848.343
      588530.903     4872849.775      588477.641     4872895.004
#Sta/Elev= 26
       0   1.575  23.496   1.448  25.459   1.497  25.677    .651  25.953   -.657
  26.096  -1.049  26.769  -1.283   28.98  -1.364  32.449  -1.382  42.137      -1
  46.811   -.568  47.906     -.5  49.953    -.44  50.764   -.248  52.004   -.167
   52.09   -.119  57.215      .5  58.008    .797  58.792       1  59.869   1.147
  60.392   1.256  75.427   1.408  79.484   1.486  86.833   1.503  97.502   1.566
  98.855   1.544
#Mann= 3 ,0,0
       0    .025       0       0    .025       0  98.855    .025       0
Bank Sta=0,98.855
XS Rating Curve= 0 ,0
Exp/Cntr=0.3,0.1

Type RM Length L Ch R = 1 ,6       ,20,20,20
XS GIS Cut Line= 6
      588541.347     4872814.668      588506.689     4872844.098
      588500.209     4872849.602      588495.437     4872853.653
      588464.431     4872879.984       588461.58     4872882.404
#Sta/Elev= 23
       0   1.616   6.696   1.479   7.937   1.169  12.556    1.34  21.646   1.399
  24.838   1.342  25.071   1.303  26.044    .587  26.759   -.343   28.84   -.767
  31.197  -1.638   32.97  -1.764  37.423  -1.702  45.468  -1.088  51.129     -.5
   53.97   -.418  55.294   -.215  55.894    -.04   63.93    .947  91.764   1.327
 100.907       1 103.141     .68 104.647    .164
#Mann= 3 ,0,0
       0    .025       0       0    .025       0  91.764    .025       0
Bank Sta=0,91.764
XS Rating Curve= 0 ,0
Exp/Cntr=0.3,0.1

Type RM Length L Ch R = 1 ,5       ,20,20,20
XS GIS Cut Line= 6
        588529.7      4872798.32      588469.835     4872849.157
      588468.993     4872849.871      588460.571     4872857.024
      588458.048     4872859.165       588446.79     4872868.726
#Sta/Elev= 28
       0   1.203   2.138    1.12   5.375     .28   13.13    .736  19.365    .902
   22.59   1.254  22.805   1.188  23.621   1.275   23.82   1.153  25.812       1
  26.688    .632   27.58   -.271  28.816   -.747  29.581  -1.209  30.225    -1.5
  38.322   -1.49  40.764      -1  45.741   -.706   55.42     -.5  60.712   -.253
  69.866       0  78.538    .715  79.642    .604  96.569    .968 101.421    .907
 102.927    .686 104.997    .643 108.771   -.228
#Mann= 3 ,0,0
       0    .025       0       0    .025       0 108.771    .025       0
Bank Sta=0,108.771
XS Rating Curve= 0 ,0
Exp/Cntr=0.3,0.1

Type RM Length L Ch R = 1 ,4       ,20,20,20
XS GIS Cut Line= 6
      588517.234     4872782.667      588472.104     4872820.992
      588464.235     4872827.673      588455.389     4872835.186
      588442.959      4872845.74      588431.844     4872855.179
#Sta/Elev= 30
       0   -.331   1.144   -.375   7.239   -.195  18.509   -.162   21.61     .96
  24.154   1.227  26.583      .5  26.719    .333  29.762   -1.08  35.122  -1.873
  36.588      -2   40.53    -1.5  42.378      -1  48.145      -1  59.207   -.781
  79.641   -.603  87.872   -.743  94.235     -.5  95.857   -.258  96.088   -.441
  96.881     -.5  97.442   -.451  97.854   -.276  99.529   -.069 101.449      .5
 101.874    .378  101.91    .484 105.517    .497 108.378   -.137 112.024   -.818
#Mann= 3 ,0,0
       0    .025       0       0    .025       0 112.024    .025       0
Bank Sta=0,112.024
XS Rating Curve= 0 ,0
Exp/Cntr=0.3,0.1

Type RM Length L Ch R = 1 ,3       ,20,20,20
XS GIS Cut Line= 6
      588504.288     4872767.422      588491.548     4872778.242
       588485.27     4872783.572      588484.573     4872784.165
      588484.169     4872784.507      588416.848     4872841.676
#Sta/Elev= 30
       0   -1.43   4.935  -1.369  11.149   -.939  14.316   -.568  16.295   -.506
  16.715       0  20.576    .939  23.403   1.176  25.214    .849  25.865      .5
  26.395      .5  27.056    .239  28.775    -.76  30.652    -1.5  38.273  -1.943
  43.059    -1.5  51.408  -1.304  61.174   -1.17  72.414  -1.314   89.91  -1.224
  94.216      -1  98.975     -.5   99.24   -.313  99.495   -.439 100.537       0
 102.163    .316 105.614    .474 107.335   -.085 107.922   -.078 114.715  -1.338
#Mann= 3 ,0,0
       0    .025       0       0    .025       0 114.715    .025       0
Bank Sta=0,114.715
XS Rating Curve= 0 ,0
Exp/Cntr=0.3,0.1

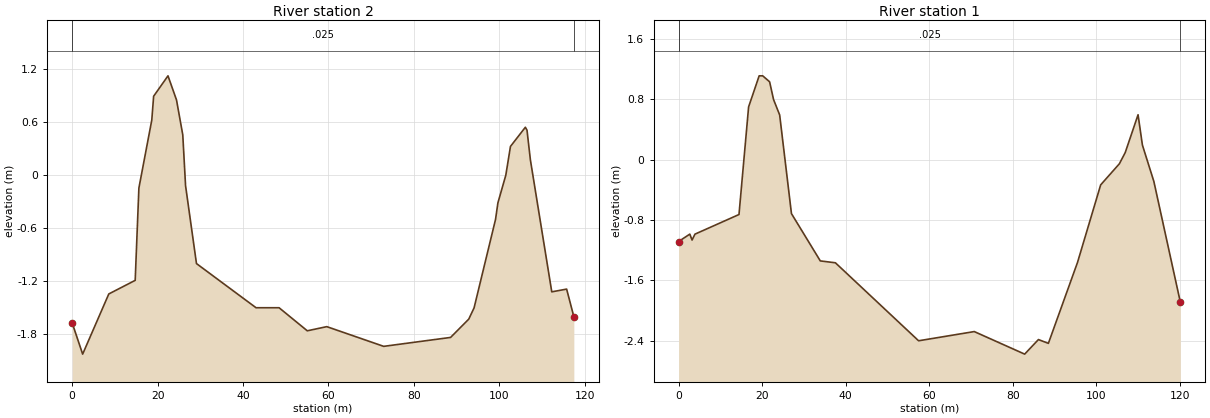
Type RM Length L Ch R = 1 ,2       ,20,20,20
XS GIS Cut Line= 6
      588491.343     4872752.177      588480.091     4872761.733
       588472.72     4872767.991      588471.816      4872768.76
      588454.419     4872783.532      588401.826     4872828.194
#Sta/Elev= 30
       0   -1.67   2.464  -2.025   8.584  -1.344  14.762   -1.19  15.628   -.145
  18.645    .624  19.079    .894  22.438   1.125  24.432    .852    25.9    .457
  26.549   -.118  29.106      -1  43.052    -1.5  48.441    -1.5  55.043  -1.761
  59.613  -1.714  72.927  -1.937  88.585  -1.836  92.836  -1.629  94.081  -1.502
  99.107     -.5  99.659   -.313 101.509       0 102.602    .326 106.088    .543
 106.474    .509 107.266    .173 112.267   -1.32 115.747  -1.289 117.439  -1.602
#Mann= 3 ,0,0
       0    .025       0       0    .025       0 117.439    .025       0
Bank Sta=0,117.439
XS Rating Curve= 0 ,0
Exp/Cntr=0.3,0.1

Type RM Length L Ch R = 1 ,1       ,20,20,20
XS GIS Cut Line= 6
      588478.397     4872736.933      588475.938      4872739.02
      588475.406     4872739.473      588459.081     4872753.335
      588456.991     4872755.111       588386.87     4872814.656
#Sta/Elev= 27
       0  -1.084   2.684   -.986   3.225  -1.064   3.924   -.986  14.454   -.726
  16.757    .701  19.282   1.113   20.13   1.113   21.78   1.034  22.731    .798
  24.189    .594  27.012   -.714  33.913  -1.341  37.531  -1.366   57.44    -2.4
  70.759  -2.278  82.822  -2.577  86.116  -2.384    88.5  -2.434  95.464  -1.362
  101.01   -.333  105.49   -.053 106.885    .095 109.959    .597 111.001    .195
  113.74   -.287 120.075  -1.887
#Mann= 3 ,0,0
       0    .025       0       0    .025       0 120.075    .025       0
Bank Sta=0,120.075
XS Rating Curve= 0 ,0
Exp/Cntr=0.3,0.1

Storage Area=north_01        ,587291.4354783,4874771.6442702
Storage Area Surface Line= 6
  589467.6999077 4874421.3102207
   588438.177965 4872851.7441194
  584934.3745526 4875584.9283853
  585684.3609349 4876359.4866045
  586920.5244638 4876009.4760195
  589467.6999077 4874421.3102207
Storage Area Type= 1
Storage Area Is2D=-1
Storage Area Point Generation Data=0,0,20,20
Storage Area 2D Points= 17271
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Storage Area Mannings=0.06
2D Cell Volume Filter Tolerance=0.003
2D Cell Minimum Area Fraction=0.01
2D Face Profile Filter Tolerance=0.003
2D Face Area Elevation Profile Filter Tolerance=0.003
2D Face Area Elevation Conveyance Ratio=0.02
2D Face Area Laminar Depth=0.06
2D Multiple Face Mann n=0

Storage Area=sea_bc          ,588280.6812962,4872551.8596926
Storage Area Surface Line= 6
588285.8894896644872844.45245437
588474.3301635314872720.85158227
588557.4061595374872625.61812343
588302.0994401044872246.71053189
587983.9791627164872499.99100752
588285.8894896644872844.45245437
Storage Area Type= 1
Storage Area Is2D=-1
Storage Area Point Generation Data=0,0,40,40
Storage Area 2D Points= 99
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Storage Area Mannings=0.06
2D Cell Volume Filter Tolerance=0.003
2D Cell Minimum Area Fraction=0.01
2D Face Profile Filter Tolerance=0.003
2D Face Area Elevation Profile Filter Tolerance=0.003
2D Face Area Elevation Conveyance Ratio=0.02
2D Face Area Laminar Depth=0.06
2D Multiple Face Mann n=0

Storage Area=south_01        ,590493.8253829,4872300.2469203
Storage Area Surface Line= 6
  589544.0093061 4874383.4925869
  591856.3592662 4872451.3182059
  592487.1593133  4871411.558689
  591205.1138015 4870220.8009434
  588485.2983951 4872784.6050905
  589544.0093061 4874383.4925869
Storage Area Type= 1
Storage Area Is2D=-1
Storage Area Point Generation Data=0,0,20,20
Storage Area 2D Points= 19654
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Storage Area Mannings=0.06
2D Cell Volume Filter Tolerance=0.003
2D Cell Minimum Area Fraction=0.01
2D Face Profile Filter Tolerance=0.003
2D Face Area Elevation Profile Filter Tolerance=0.003
2D Face Area Elevation Conveyance Ratio=0.02
2D Face Area Laminar Depth=0.06
2D Multiple Face Mann n=0

BreakLine Name=bl_coast_north_3
BreakLine CellSize Min=10
BreakLine CellSize Max=20
BreakLine Near Repeats=1
BreakLine Protection Radius=0
BreakLine Polyline= 6
587881.3368841124873457.22626946587954.4631605574873408.08541168
588015.8892327714873327.35400249588207.7725821644873185.78153129
588253.4033786664873127.28051013588491.2100296664872915.79931865

BreakLine Name=bl_coast_north_2
BreakLine CellSize Min=10
BreakLine CellSize Max=20
BreakLine Near Repeats=1
BreakLine Protection Radius=0
BreakLine Polyline= 6
586762.3063616964874410.98223713587014.3106572554874177.69826067
587240.7545171214874039.09589812587260.9148607664873955.57447445
587525.8793772384873806.53193393 587839.444722144873487.20649084

BreakLine Name=bl_coast_north_1
BreakLine CellSize Min=10
BreakLine CellSize Max=20
BreakLine Near Repeats=1
BreakLine Protection Radius=0
BreakLine Polyline= 6
584984.8419071444875643.39910842585024.442558556 4875680.8397243
585229.6459340564875523.87714234585389.4885633934875502.27678702
586214.9821423784874750.94442796586745.2708653814874434.49922258

BreakLine Name=bl_sea_north
BreakLine CellSize Min=10
BreakLine CellSize Max=20
BreakLine Near Repeats=1
BreakLine Protection Radius=0
BreakLine Polyline= 6
584944.5634242414875583.12372588585625.7205257234875210.88834532
586205.025218227 4874635.2540099 586499.571373924874552.97683868
586884.6530042594874280.45282547588439.6609539374872856.35427833

BreakLine Name=bl_sea_south
BreakLine CellSize Min=10
BreakLine CellSize Max=20
BreakLine Near Repeats=1
BreakLine Protection Radius=0
BreakLine Polyline= 6
588490.7275960984872785.42679873588964.2975241844872461.68265075
589405.8694841554872123.25708211 590776.51185948 4870729.2750124
 591097.620880674870387.08497692591206.7904189414870226.71868967

BreakLine Name=bl_coast_south_2
BreakLine CellSize Min=10
BreakLine CellSize Max=20
BreakLine Near Repeats=1
BreakLine Protection Radius=0
BreakLine Polyline= 6
589341.4130584844872227.71229883589463.7047245824872138.20897799
589719.8082861944871860.83730054 590180.174377054871415.53612507
590500.5253719384871057.96592746591245.7955979444870283.45204217

BreakLine Name=bl_coast_south_1
BreakLine CellSize Min=10
BreakLine CellSize Max=20
BreakLine Near Repeats=1
BreakLine Protection Radius=0
BreakLine Polyline= 6
588569.7988914394872849.75225244 588606.042781164872789.34576957
588671.8187291724872743.70531584588704.0355200354872699.40722841
589051.7083880994872469.86259351   589290.6495874872255.08398775

BreakLine Name=bl_19
BreakLine Near Repeats=1
BreakLine Protection Radius=0
BreakLine Polyline= 6
590094.3554620384873318.59906656589991.0964438764873174.03644113
589802.7519947484873102.16816449589660.2545496844872789.49985749
589559.4737479584872693.67548864589434.3238179454872392.57219168

BreakLine Name=bl_09
BreakLine Near Repeats=1
BreakLine Protection Radius=0
BreakLine Polyline= 6
589622.9432850064872680.92427326 589659.819584614872634.18570748
589792.3169866764872834.00379603589826.6383006414873107.56699204
590001.3556528024873164.93686887590162.3824661744873366.38336819

BreakLine Name=bl_08
BreakLine Near Repeats=1
BreakLine Protection Radius=0
BreakLine Polyline= 6
589466.6606816974872367.12687974589539.7583717034872494.25329715
589562.0054947484872562.05405309589567.3024288074872630.91419585
 589582.133844174872667.99273426589622.3905430144872713.54636716

BreakLine Name=bl_07
BreakLine Near Repeats=1
BreakLine Protection Radius=0
BreakLine Polyline= 6
 589328.992130034872241.91932079589440.5086094294872342.03488047
589536.7936994594872271.42581445589743.8066430234872088.48414339
589971.1876205774871996.51950061590087.717272339 4871909.6160315

BreakLine Name=bl_06
BreakLine Near Repeats=1
BreakLine Protection Radius=0
BreakLine Polyline= 6
589170.8248956254872518.05429698589230.2006967194872513.24004284
589381.0473265274872396.09319203589413.1423541464872370.41716993
589356.9760558134872311.04136884  589299.20500614872254.87507051

BreakLine Name=bl_01
BreakLine Near Repeats=1
BreakLine Protection Radius=0
BreakLine Polyline= 6
587849.5805810194873484.40492094587907.1512571724873535.20257636
587988.4275058584873582.61372143588241.2869462174873765.48528098
588237.9004358554873777.90248564588058.415386672 4873923.5224312

BreakLine Name=bl_02
BreakLine Near Repeats=1
BreakLine Protection Radius=0
BreakLine Polyline= 6
587878.0572546594873471.80251091588185.0832227344873699.83636098
588302.0809824134873775.84764434588357.9716319424873829.50266789
588367.2867401964873883.53029576588286.8042048764874059.39953961

BreakLine Name=bl_03
BreakLine Near Repeats=1
BreakLine Protection Radius=0
BreakLine Polyline= 6
588068.4580673854874177.88771661588265.1931537254874034.06244516
588341.949645743 4873871.6069572588254.7602324794873779.94629197
587932.0848825374874098.15038995588047.5922248954873927.49760672

BreakLine Name=bl_04
BreakLine Near Repeats=1
BreakLine Protection Radius=0
BreakLine Polyline= 2
 587983.309247464873574.70242522  587992.65637644873563.87943381

BreakLine Name=bl_05
BreakLine Near Repeats=1
BreakLine Protection Radius=0
BreakLine Polyline= 6
588080.224224788 4874189.6451295588238.633462603 4874074.5278573
588301.6035944054874113.39223552588303.5714110234874146.84511804
588141.7184941264874307.71412663 588223.13690673 4874401.4313931

BreakLine Name=bl_10
BreakLine Near Repeats=1
BreakLine Protection Radius=0
BreakLine Polyline= 6
 588290.144889134874065.18245476588322.1219127594874120.34282052
588346.9041060724874138.72960911588390.0730879724874151.52041856
588410.058727741 4874165.9100792 588452.428284054874217.87274259

BreakLine Name=bl_11
BreakLine Near Repeats=1
BreakLine Protection Radius=0
BreakLine Polyline= 6
588234.9845230384874390.54866195588158.2396663274874315.40265642
 588323.720763614874150.72098473588374.0845758264874163.51179418
588436.4397719044874223.46871348588239.7810765824874387.35095958

BreakLine Name=bl_12
BreakLine Near Repeats=1
BreakLine Protection Radius=0
BreakLine Polyline= 6
588561.1880083824874817.36154724588414.6613282414874641.77172393
588390.4420422684874616.34147366588395.2858994624874606.65375927
588478.8424360714874681.73354579588582.9853657584874811.30672575

BreakLine Name=bl_13
BreakLine Near Repeats=1
BreakLine Protection Radius=0
BreakLine Polyline= 6
588451.391151887 4874236.6479877588323.4330837364874339.27425556
588217.5591491744874431.50798997587955.7972128034874643.90539243
587859.9910450254874723.47322669587734.6311102374874820.90322782

BreakLine Name=bl_14
BreakLine Near Repeats=1
BreakLine Protection Radius=0
BreakLine Polyline= 6
588217.8839071534874403.90282924588108.7623058874874492.88889694
587950.925704055 4874624.0946318587899.9373367974874667.28859897
587788.2176021674874760.82140005587725.862401444  4874814.083134

BreakLine Name=bl_15
BreakLine Near Repeats=1
BreakLine Protection Radius=0
BreakLine Polyline= 6
586751.8003380384874436.87210882586773.6688087044874463.45730846
586879.5808136974874625.97006106586865.8594203384874643.97938984
 586805.828324394874683.85718929 586805.828324394874690.28909243

BreakLine Name=bl_16
BreakLine Near Repeats=1
BreakLine Protection Radius=0
BreakLine Polyline= 6
586762.0913830574874417.14760587586771.9536345344874440.30245716
586896.7325553964874622.96850626586951.1893352924874583.51950035
586978.2033284684874575.37242305587012.0780183244874611.39108061

BreakLine Name=bl_17
BreakLine Near Repeats=1
BreakLine Protection Radius=0
BreakLine Polyline= 6
587460.4883209344875555.47140206587439.9062255274875523.27889386
 587406.130479224875456.78289332587385.5483838134875425.64587719
 587231.974287324875225.10238349587160.7285724524875122.71965249

BreakLine Name=bl_18
BreakLine Near Repeats=1
BreakLine Protection Radius=0
BreakLine Polyline= 6
587481.598163354 4875558.1101298587454.1553694794875520.64016124
587416.1576548824875443.06149394 587325.385336684875320.09666754
587206.1147325314875165.99482501587169.1725100064875112.16472933

BreakLine Name=bl_24
BreakLine Near Repeats=1
BreakLine Protection Radius=0
BreakLine Polyline= 6
589908.0195863644873009.08593075590150.0613280364873295.40360078
 590243.53273234 4873193.0770108590304.5351225174873059.26531622
 590291.74429877 4872944.1479025590181.5464326434872810.33620791

BreakLine Name=bl_25
BreakLine Near Repeats=1
BreakLine Protection Radius=0
BreakLine Polyline= 6
590200.7820822564873354.17623785590857.125490123 4872690.5670358
591112.639252226 4872476.2261074591390.5558797264872174.09016596
 591397.821673914872140.18312643591334.8514576574872088.11160146

BreakLine Name=bl_26
BreakLine Near Repeats=1
BreakLine Protection Radius=0
BreakLine Polyline= 6
591026.834245725  4870778.148295591233.0863093774871025.17111542
591463.3211711294871308.16813299591556.8540837164871439.27409593
591745.9184753974871713.07770757 592005.332408174872075.61767217

BreakLine Name=bl_278
BreakLine Near Repeats=1
BreakLine Protection Radius=0
BreakLine Polyline= 6
591102.0147024014870704.04207876 591173.260475664870777.92658436
591116.7916035214870832.81221709591129.4575187674870873.44869518
 591498.880046784871331.00488344592021.3490506844872072.48867181

BreakLine Name=bl_28
BreakLine Near Repeats=1
BreakLine Protection Radius=0
BreakLine Polyline= 6
591925.1711543434871910.67659033592025.0994872024871823.53908408
592004.3143939674871737.20100449592176.1911264844871577.31567191
592226.5550062454871643.66808493592019.5035005624871933.06053689

BreakLine Name=bl_28(1)
BreakLine Near Repeats=1
BreakLine Protection Radius=0
BreakLine Polyline= 2
 590004.704746684872751.75289066590058.3598541784872815.84093573

BreakLine Name=bl_29
BreakLine Near Repeats=1
BreakLine Protection Radius=0
BreakLine Polyline= 4
590171.631747786  4872715.982819590275.9611234784872616.12470226
590375.8192402114872531.17078206 590489.091133824872426.84140637

BreakLine Name=bl_30
BreakLine Near Repeats=1
BreakLine Protection Radius=0
BreakLine Polyline= 5
590193.9880510554873371.76749666590310.2407839684873495.47232783
 590322.164141194873528.26156019590357.9342128564873575.95498908
590420.5318382714873640.04303415

BreakLine Name=bl_32
BreakLine Near Repeats=1
BreakLine Protection Radius=0
BreakLine Polyline= 2
586981.7614200384874555.83633019587069.6984479574874488.68441796

BreakLine Name=bl_33
BreakLine Near Repeats=1
BreakLine Protection Radius=0
BreakLine Polyline= 6
588080.174823691 4873320.7208145 588642.572088614873971.05510734
588844.0278252974874098.96351159589123.4277458224874378.36343211
589184.9836653654874488.68443077589244.1413023294874550.24035032

BreakLine Name=bl_22
BreakLine Near Repeats=1
BreakLine Protection Radius=0
BreakLine Polyline= 6
589755.0411145274874192.28608915589364.5507436414873609.53137535
589048.5814359014873150.48162637  588889.85157144872909.77859241
588863.023988667 4872857.6138482 588742.299866374872735.39930464

BC Line Name=down_sea_bc
BC Line Storage Area=sea_bc
BC Line Start Position= 587979.749704649 , 4872488.33741913
BC Line Middle Position= 588137.719407282 , 4872364.92358895
BC Line End Position= 588295.689109915 , 4872241.50975877
BC Line Arc= 2
587979.7497046494872488.33741913588295.6891099154872241.50975877

BC Line Name=bc_sea_north
BC Line Storage Area=north_01
BC Line Start Position= 584932.641197977 , 4875576.02179068
BC Line Middle Position= 586772.598460324 , 4874355.93685434
BC Line End Position= 588424.098412388 , 4872862.22263826
BC Line Arc= 6
584932.6411979774875576.02179068585520.7293098634875274.39493673
586193.4919994644874630.27837292586491.7487209654874547.71012799
586871.3098877354874280.20586506588424.0984123884872862.22263826

BC Line Name=bc_sea_south
BC Line Storage Area=south_01
BC Line Start Position= 588530.388716 , 4872745.45659057
BC Line Middle Position= 589935.875794947 , 4871565.81211322
BC Line End Position= 591194.95710432 , 4870223.71045483
BC Line Arc= 6
   588530.3887164872745.45659057588969.598913813 4872448.9095592
589396.7869346794872118.70043237590712.8975378394870778.73170396
591084.2940517354870381.63409612 591194.957104324870223.71045483
LCMann Table=0

Chan Stop Cuts=-1
Use User Specified Reach Order=0
Composite Channel Slope=5